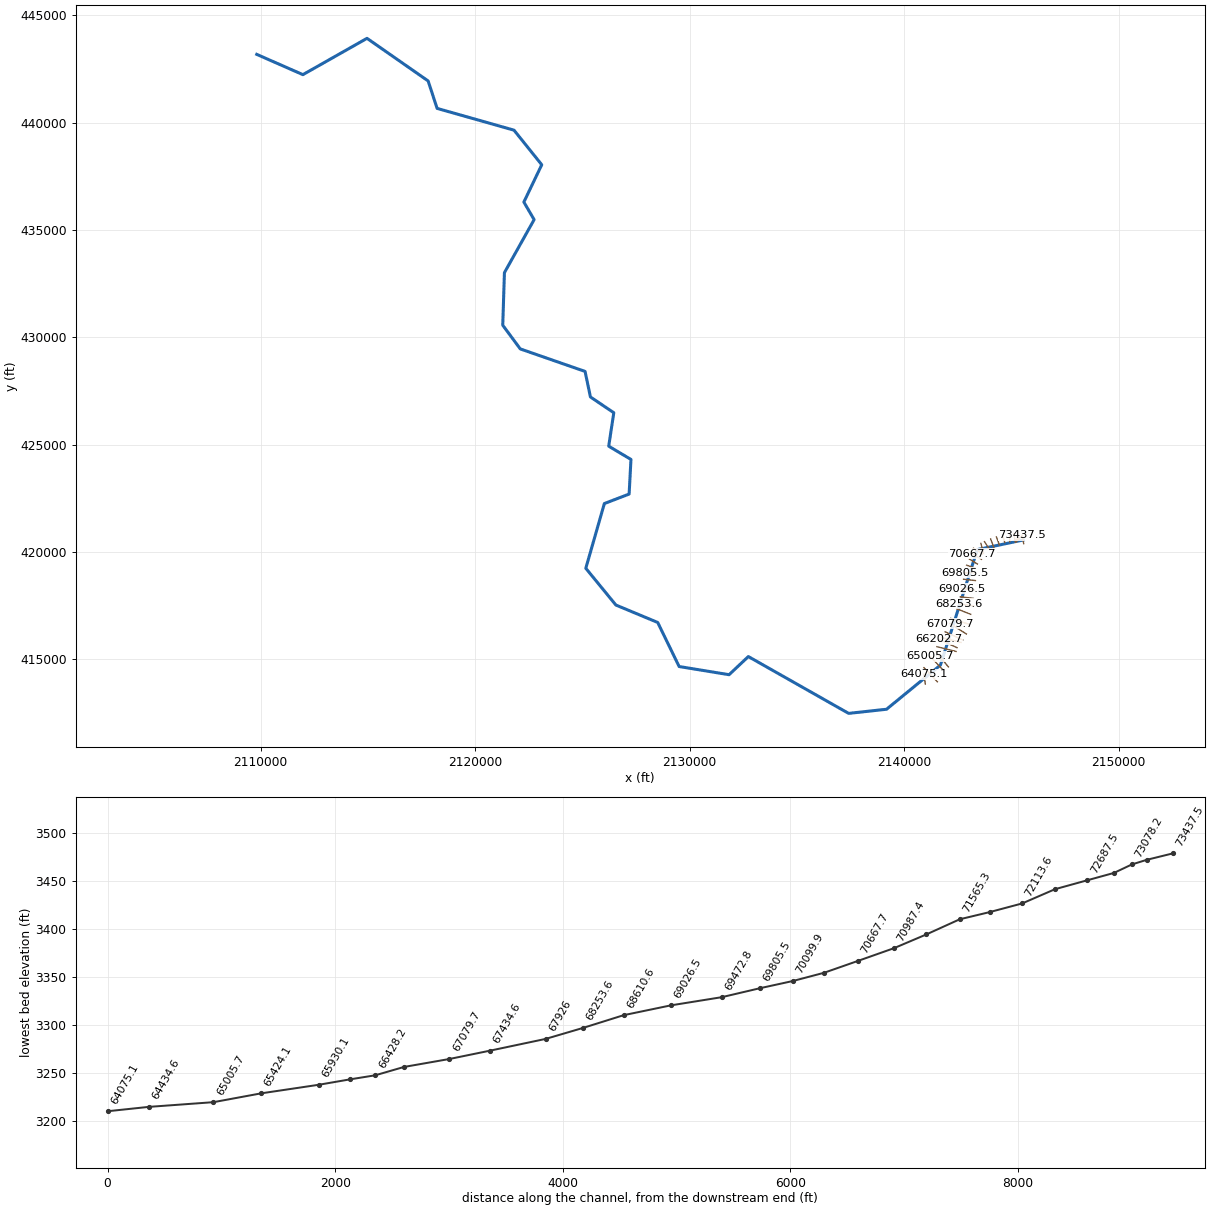
--- SFrkChryRv.prj (project) ---

Proj Title=SFrkChryRv
Current Plan=p01
Default Exp/Contr=0,0
English Units
Geom File=g01
Flow File=f01
Plan File=p01
BEGIN DESCRIPTION:
END DESCRIPTION:
DSS Export Rating Curves= 0
DSS Export Rating Curve Sorted= 0
DSS Export Volume Flow Curves= 0
DXF OffsetX= 0
DXF OffsetY= 0
DXF ScaleX= 0
DXF ScaleY= 0

--- SFrkChryRv.p01 (plan) ---

Plan Title=Floodplain
Program Version=4.00
Geom File=g01
Flow File=f01
K Sum by GR=0
Std Step Tol=0.01
Critical Tol=0.01
Num of Std Step Trials=20
Max Error Tol=0.3
Flow Tol Ratio=0.001
Split Flow NTrial=30
Split Flow Tol=0.02
Split Flow Ratio=0.02
Log Output Level=0
Friction Slope Method=1
Unsteady Friction Slope Method=2
Unsteady Bridges Friction Slope Method=1
Global Log Level=0
CheckData=False
Run HTab=0
Run UNet=0
Run PostProcess=0
UNET Theta=0
UNET Theta Warmup=0
UNET ZTol=0
UNET ZSATol=0
UNET MxIter=0
UNET MaxInSteps=0
UNET DtIC=0
UNET DtMin=0
UNET MaxCRTS=0
UNET WFStab=0
UNET SFStab=0
UNET WFX=0
UNET SFX=0
UNET DSS MLevel=0
UNET DZMax Abort=0
UNET Convert EG Bridges=0
UNET Use Existing IB Tables=0
UNET Froude Limit=0
UNET Froude Power=0
Write IC File=0
Echo Input=False
Echo Output=False
Write Detailed=0

--- SFrkChryRv.f01 (steady flow) ---

Flow Title=NFF Regression Equation
Program Version=4.00
Number of Profiles=1
Profile Names=P100yr
River Rch & RM=SFrkChryRv,Main      ,73437.5
515.0376
River Rch & RM=SFrkChryRv,Main      ,72113.6
566.1804
River Rch & RM=SFrkChryRv,Main      ,70667.7
628.0419
River Rch & RM=SFrkChryRv,Main      ,69472.8
694.1842
River Rch & RM=SFrkChryRv,Main      ,67926
753.1412
River Rch & RM=SFrkChryRv,Main      ,65424.1
833.0705
River Rch & RM=SFrkChryRv,Main      ,65005.7
994.5692
River Rch & RM=SFrkChryRv,Main      ,63644.8
1027.803
River Rch & RM=SFrkChryRv,Main      ,58645.9
1132.761
River Rch & RM=SFrkChryRv,Main      ,58325.5
1361.866
River Rch & RM=SFrkChryRv,Main      ,57639.8
1379.698
River Rch & RM=SFrkChryRv,Main      ,53527.3
1531.416
River Rch & RM=SFrkChryRv,Main      ,52825.2
1716.338
River Rch & RM=SFrkChryRv,Main      ,49776.9
1803.145
River Rch & RM=SFrkChryRv,Main      ,49255.6
3069.423
River Rch & RM=SFrkChryRv,Main      ,42662
3207.795
River Rch & RM=SFrkChryRv,Main      ,42144.6
3618.214
River Rch & RM=SFrkChryRv,Main      ,32644.4
4007.368
River Rch & RM=SFrkChryRv,Main      ,32258.5
5064.296
River Rch & RM=SFrkChryRv,Main      ,27096
5330.328
River Rch & RM=SFrkChryRv,Main      ,15900
5833.603
River Rch & RM=SFrkChryRv,Main      ,39.8
6437.694
Boundary for River Rch & Prof#=SFrkChryRv,Main      ,1
Up Type=0
Dn Type=3
Dn Slope=0.013992

--- SFrkChryRv.g01 (geometry) ---

Geom Title=USGS 10m DEM
Program Version=4.00

River Reach=SFrkChryRv      ,Main
Reach XY= 30
     2145548.802       420563.53     2143404.802      420114.606
      2141686.06      414735.885     2139176.078      412681.415
     2137408.646      412489.377     2132735.106       415134.54
     2131836.318       414290.07     2129509.411      414670.998
     2128510.993      416722.212     2126561.322      417534.426
     2125159.491      419245.645     2126024.662      422259.307
     2127179.175      422702.016     2127264.245      424313.127
     2126227.786      424931.182     2126463.898      426488.474
     2125375.317        427223.2     2125125.317      428412.436
     2122104.994      429460.601     2121289.022      430563.031
     2121367.147      433010.948     2122750.828      435479.698
     2122273.397      436299.143      2123106.73      438035.254
     2121813.327      439646.365     2118229.994      440660.254
     2117811.591      441938.032     2114962.633      443922.407
     2111974.786      442231.434     2109823.931      443175.883

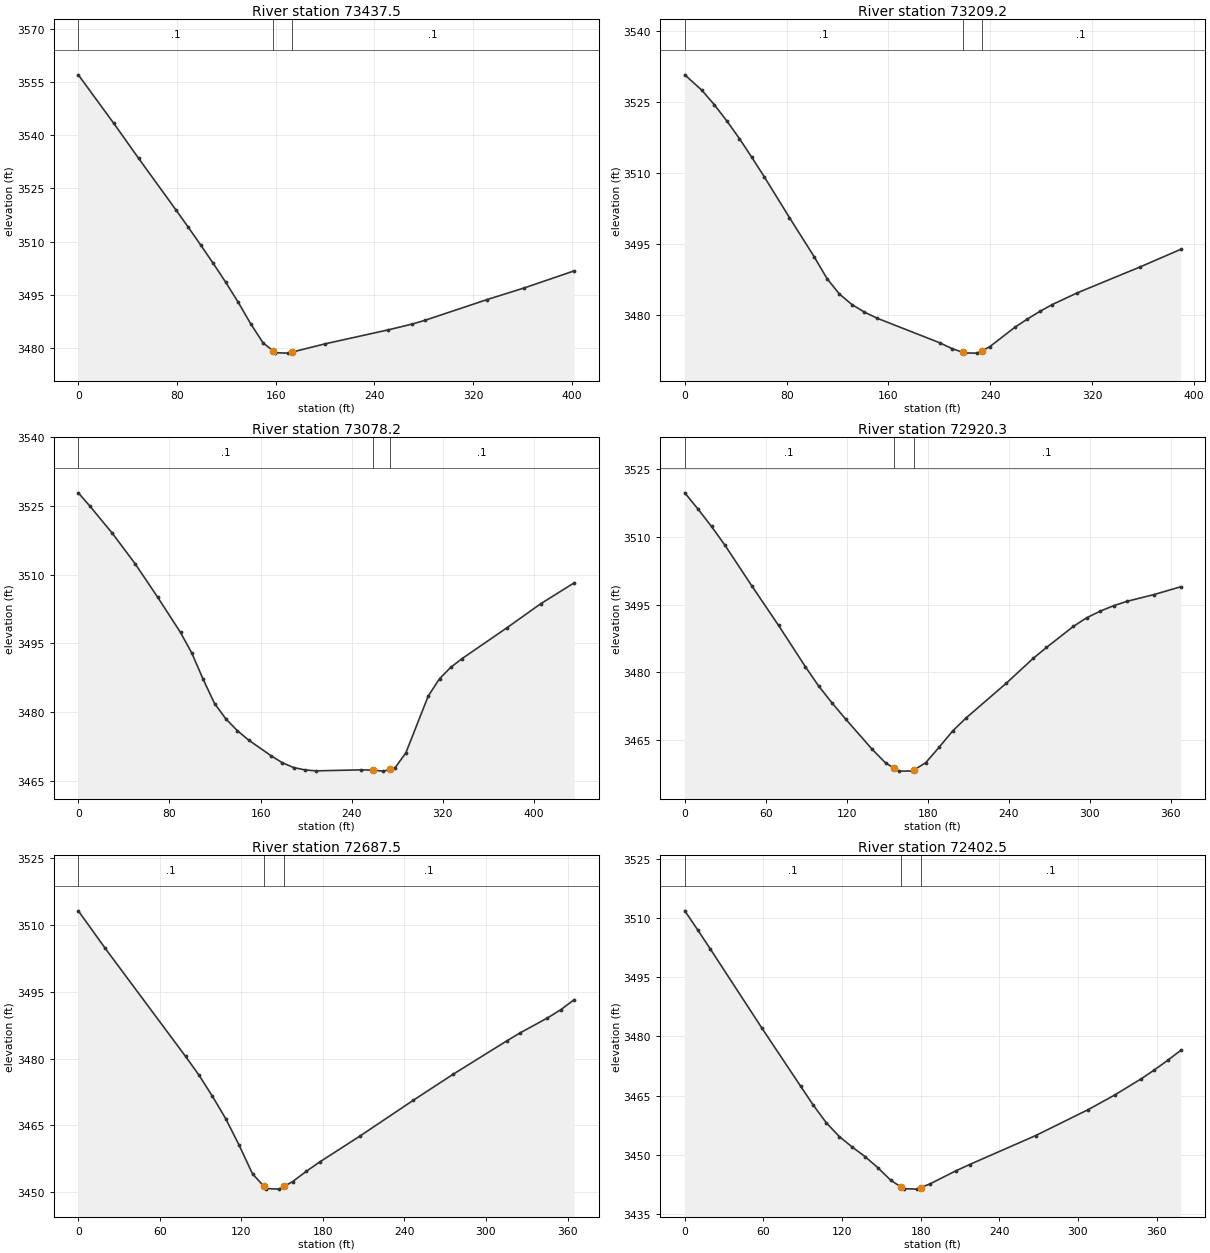
Type RM Length L Ch R = 1 ,73437.5 ,251.8,228.3,210.3
XS GIS Cut Line= 3
     2145565.261      420394.503     2145563.815      420402.858
     2145496.705       420790.65
#Sta/Elev= 22
       0 3556.97    28.7 3543.32    48.8 3533.49    79.1 3518.94    89.2 3514.02
    99.3    3509   109.4 3503.85   119.5 3498.55   129.6 3492.93   139.7 3486.89
   149.8 3481.46   158.2 3479.15   159.8  3478.7   169.9 3478.59   173.2 3478.87
   200.2 3481.22   250.7  3485.1   270.8 3486.78   280.9 3487.82   331.4 3493.67
   361.7 3496.97     402 3501.76
#Mann= 3 , 0 , 0
       0      .1       0   158.2    .045       0   173.2      .1       0
Bank Sta=158.2,173.2
XS Rating Curve= 0 ,0
Exp/Cntr=0.3,0.1

Type RM Length L Ch R = 1 ,73209.2 ,111.4,131.1,148.6
XS GIS Cut Line= 5
     2145196.551      420466.194     2145199.132      420468.737
       2145332.1        420599.7     2145451.861      420716.507
     2145474.732      420738.814
#Sta/Elev= 28
       0 3530.67    13.4 3527.42    23.3 3524.32    33.1 3520.91    42.9 3517.22
    52.7 3513.23    62.6 3509.08    82.2 3500.54   101.8  3492.2   111.7 3487.67
   121.5 3484.38   131.3 3482.18   141.1 3480.58     151  3479.3   200.1 3474.12
   209.9 3472.88   218.3  3472.1   219.8 3471.96   229.6 3471.92   233.3 3472.42
   239.5 3473.26   259.1 3477.34     269  3479.1   278.8 3480.71   288.7 3482.18
   308.3 3484.64   357.6 3490.11   389.5 3493.82
#Mann= 3 , 0 , 0
       0      .1       0   218.3    .045       0   233.3      .1       0
Bank Sta=218.3,233.3
XS Rating Curve= 0 ,0
Exp/Cntr=0.3,0.1

Type RM Length L Ch R = 1 ,73078.2 ,154.4,157.9,163
XS GIS Cut Line= 3
     2145194.182      420474.124     2145267.817      420615.529
     2145279.546       420891.17
#Sta/Elev= 30
       0 3527.91      10 3525.05    29.9 3519.06    49.8 3512.44    69.8 3505.05
    89.7  3497.4    99.6  3492.9   109.6 3487.16   119.6 3481.87   129.5 3478.53
   139.5 3475.97   149.5 3473.89   169.3 3470.45   179.1 3468.93     189 3467.89
   198.8 3467.37   208.7 3467.16   248.1 3467.38   258.8 3467.31   267.8  3467.1
   273.8 3467.47   277.7 3467.71   287.5 3471.07   307.2 3483.51   317.1 3487.29
   326.9 3489.77   336.8 3491.67   376.2 3498.41   405.8 3503.65   435.3 3508.24
#Mann= 3 , 0 , 0
       0      .1       0   258.8    .045       0   273.8      .1       0
Bank Sta=258.8,273.8
XS Rating Curve= 0 ,0
Exp/Cntr=0.3,0.1

Type RM Length L Ch R = 1 ,72920.3 ,237.7,232.9,228.7
XS GIS Cut Line= 3
     2145178.105      420495.701     2145145.022       420661.12
      2145107.01      420856.139
#Sta/Elev= 30
       0 3519.64     9.9 3516.01    19.8 3512.22    29.8 3508.06    49.6 3499.14
    69.5 3490.38    89.3  3481.3    99.2 3477.01   109.2 3473.25   119.1 3469.75
   138.9 3463.04   148.8 3460.04   154.7 3458.97   158.8 3458.24   168.7 3458.27
   169.7 3458.46   178.6 3460.13   188.6 3463.56   198.5 3467.11   208.4 3469.96
   238.2 3477.63   258.1  3483.1     268 3485.52   287.9 3490.16   297.8 3492.08
   307.8 3493.53   317.7 3494.73   327.6  3495.7   347.5 3497.18   367.4 3498.91
#Mann= 3 , 0 , 0
       0      .1       0   154.7    .045       0   169.7      .1       0
Bank Sta=154.7,169.7
XS Rating Curve= 0 ,0
Exp/Cntr=0.3,0.1

Type RM Length L Ch R = 1 ,72687.5 ,277.9,285,292
XS GIS Cut Line= 2
     2144914.131      420479.772      2144922.05      420844.563
#Sta/Elev= 23
       0 3513.22    19.7 3504.82    78.9 3480.49    88.8 3476.27    98.6 3471.56
   108.5 3466.47   118.3 3460.54   128.2 3454.07   136.5  3451.3   138.1 3450.77
   147.9 3450.64   151.5 3451.26   157.8 3452.35   167.6 3454.61   177.5 3456.72
   207.1 3462.54   246.5 3470.62   276.1 3476.52   315.6 3484.03   325.4 3485.82
   345.2 3489.12     355 3490.97   364.9 3493.25
#Mann= 3 , 0 , 0
       0      .1       0   136.5    .045       0   151.5      .1       0
Bank Sta=136.5,151.5
XS Rating Curve= 0 ,0
Exp/Cntr=0.3,0.1

Type RM Length L Ch R = 1 ,72402.5 ,293.4,288.9,290.9
XS GIS Cut Line= 3
      2144687.35      420445.676     2144639.201      420605.552
     2144579.216      420808.316
#Sta/Elev= 26
       0 3511.76     9.8 3506.96    19.6 3502.04    58.9 3482.04    88.4 3467.36
    98.2  3462.5     108  3458.1   117.9 3454.62   127.7 3451.98   137.5 3449.56
   147.3 3446.74   157.2 3443.54   165.2  3441.8     167 3441.42     177  3441.3
   180.2 3441.71   187.1 3442.62   207.2 3445.99   217.3 3447.52   267.7 3454.85
   307.9 3461.44   328.1 3465.13   348.2 3469.21   358.3 3471.46   368.4 3473.88
   378.4 3476.41
#Mann= 3 , 0 , 0
       0      .1       0   165.2    .045       0   180.2      .1       0
Bank Sta=165.2,180.2
XS Rating Curve= 0 ,0
Exp/Cntr=0.3,0.1

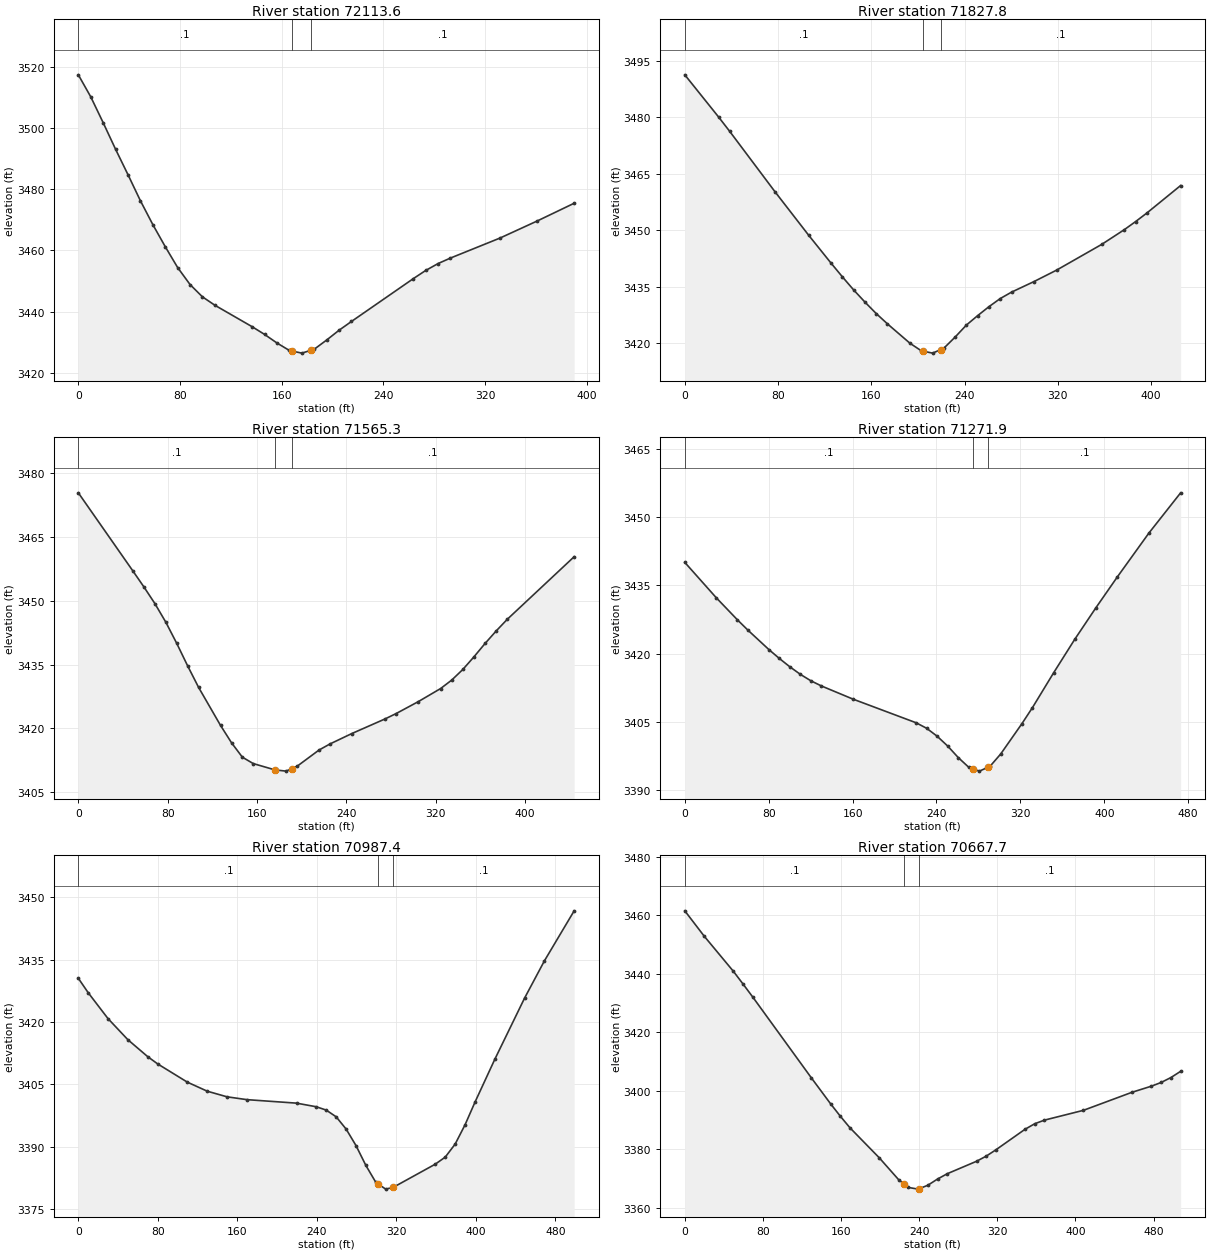
Type RM Length L Ch R = 1 ,72113.6 ,285.6,285.9,286.1
XS GIS Cut Line= 3
     2144433.631       420342.44     2144356.975      420543.127
     2144295.273      420707.065
#Sta/Elev= 30
       0 3517.34     9.8 3510.13    19.5 3501.74    29.3 3493.03    39.1 3484.69
    48.8 3476.24    58.6 3468.42    68.4 3461.19    78.1 3454.41    87.9 3448.84
    97.6 3444.84   107.4 3442.09   136.7 3435.08   146.5 3432.56   156.2 3429.77
     166 3427.32     168 3427.14   175.8 3426.45     183 3427.38   185.5 3427.71
   195.3 3430.72   205.1 3433.93   214.8 3436.78   263.5 3450.78   273.2 3453.44
     283 3455.71   292.7  3457.5   331.6 3464.02   360.8 3469.58     390  3475.4
#Mann= 3 , 0 , 0
       0      .1       0     168    .045       0     183      .1       0
Bank Sta=168,183
XS Rating Curve= 0 ,0
Exp/Cntr=0.3,0.1

Type RM Length L Ch R = 1 ,71827.8 ,257.8,262.5,267.1
XS GIS Cut Line= 3
     2144179.314      420210.012     2144100.023      420417.595
     2144028.454       420607.75
#Sta/Elev= 30
       0 3491.31      29 3480.11    38.6 3476.27    77.3  3460.3   106.3 3448.71
   125.6 3441.27   135.3 3437.64   144.9 3434.19   154.6 3430.96   164.2 3427.94
   173.9 3425.18   193.2 3420.04   202.9 3418.04   204.6 3417.93   212.6 3417.42
   219.6 3418.36   222.2 3418.71   231.9 3421.67   241.6 3424.87   251.2 3427.36
   260.9 3429.74   270.6  3431.9   280.3 3433.61   299.6 3436.42     319 3439.46
   357.7 3446.29     377 3450.18   386.7 3452.33   396.4 3454.61   425.4 3461.92
#Mann= 3 , 0 , 0
       0      .1       0   204.6    .045       0   219.6      .1       0
Bank Sta=204.6,219.6
XS Rating Curve= 0 ,0
Exp/Cntr=0.3,0.1

Type RM Length L Ch R = 1 ,71565.3 ,311.1,293.4,287.3
XS GIS Cut Line= 3
     2143985.951      420114.288     2143844.612      420325.977
     2143740.297      420483.881
#Sta/Elev= 30
       0 3475.35      49 3456.93    58.7 3453.24    68.5 3449.34    78.3 3444.96
    88.1 3439.97    97.9 3434.66   107.7 3429.61   127.3 3420.69   137.1 3416.63
   146.8 3413.24   156.6 3411.73     176 3410.25     186 3409.96     191 3410.54
   195.8  3411.1   215.4 3414.91   225.2 3416.34   244.8 3418.79   274.5 3422.22
   284.4 3423.48   304.3 3426.29   324.3 3429.37   334.2 3431.35   344.2 3433.86
   354.1 3436.81   364.1 3439.97   374.1 3442.92     384 3445.65   443.8 3460.34
#Mann= 3 , 0 , 0
       0      .1       0     176    .045       0     191      .1       0
Bank Sta=176,191
XS Rating Curve= 0 ,0
Exp/Cntr=0.3,0.1

Type RM Length L Ch R = 1 ,71271.9 ,267.7,284.5,301.3
XS GIS Cut Line= 3
     2143694.787      419949.563     2143631.521      420181.698
     2143571.565      420406.004
#Sta/Elev= 30
       0 3440.07    30.1 3432.27    50.1 3427.46    60.2 3425.17    80.2  3420.9
    90.2 3418.94   100.2 3417.11   110.3 3415.44   120.3 3414.03   130.3  3412.9
   160.4 3410.01   220.6 3404.81   230.6  3403.6   240.6 3401.86   250.7 3399.69
   260.8 3397.15   270.9    3395   274.4 3394.71     281 3394.18   289.4 3395.07
   291.1 3395.25   301.2 3397.94   321.4 3404.59   331.5 3408.14   351.6 3415.76
   371.8 3423.14     392 3430.09   412.2 3436.79   442.5  3446.5   472.8 3455.36
#Mann= 3 , 0 , 0
       0      .1       0   274.4    .045       0   289.4      .1       0
Bank Sta=274.4,289.4
XS Rating Curve= 0 ,0
Exp/Cntr=0.3,0.1

Type RM Length L Ch R = 1 ,70987.4 ,320.4,319.8,319.2
XS GIS Cut Line= 2
     2143647.378      419917.447     2143223.686      420180.659
#Sta/Elev= 30
       0 3430.51      10 3427.02    29.9 3420.81    49.9 3415.74    69.8 3411.68
    79.8 3409.94   109.7 3405.55   129.7 3403.38   149.6 3402.03   169.6 3401.35
   219.5 3400.51   239.4 3399.64   249.4 3398.84   259.4 3397.22   269.4 3394.28
   279.3 3390.33   289.3 3385.53   299.3 3381.47   301.8 3381.06   309.2 3379.85
   316.8 3380.28   359.1 3385.85   369.1 3387.54   379.1 3390.68   389.1 3395.34
     399 3400.73     419 3411.06   448.9 3425.74   468.9 3434.71   498.8 3446.72
#Mann= 3 , 0 , 0
       0      .1       0   301.8    .045       0   316.8      .1       0
Bank Sta=301.8,316.8
XS Rating Curve= 0 ,0
Exp/Cntr=0.3,0.1

Type RM Length L Ch R = 1 ,70667.7 ,294.8,295,295.2
XS GIS Cut Line= 2
     2143600.368      419661.706     2143169.097      419929.627
#Sta/Elev= 30
       0 3461.52    19.9 3452.85    49.8 3440.84    59.7 3436.49    69.7 3432.02
   129.4 3404.55   149.3  3395.6   159.3 3391.34   169.2 3387.38   199.1 3377.17
     219 3369.67   224.4 3368.24     229 3367.03   238.9 3366.46   239.4 3366.52
   248.9 3367.79   258.8 3369.91   268.8 3371.73   298.7 3375.97   308.6 3377.72
   318.6  3379.9   348.4 3386.91   358.4 3388.81   368.3 3390.03   408.2 3393.38
   457.9 3399.54   477.8 3401.63   487.8  3402.9   497.8 3404.58   507.7  3406.7
#Mann= 3 , 0 , 0
       0      .1       0   224.4    .045       0   239.4      .1       0
Bank Sta=224.4,239.4
XS Rating Curve= 0 ,0
Exp/Cntr=0.3,0.1

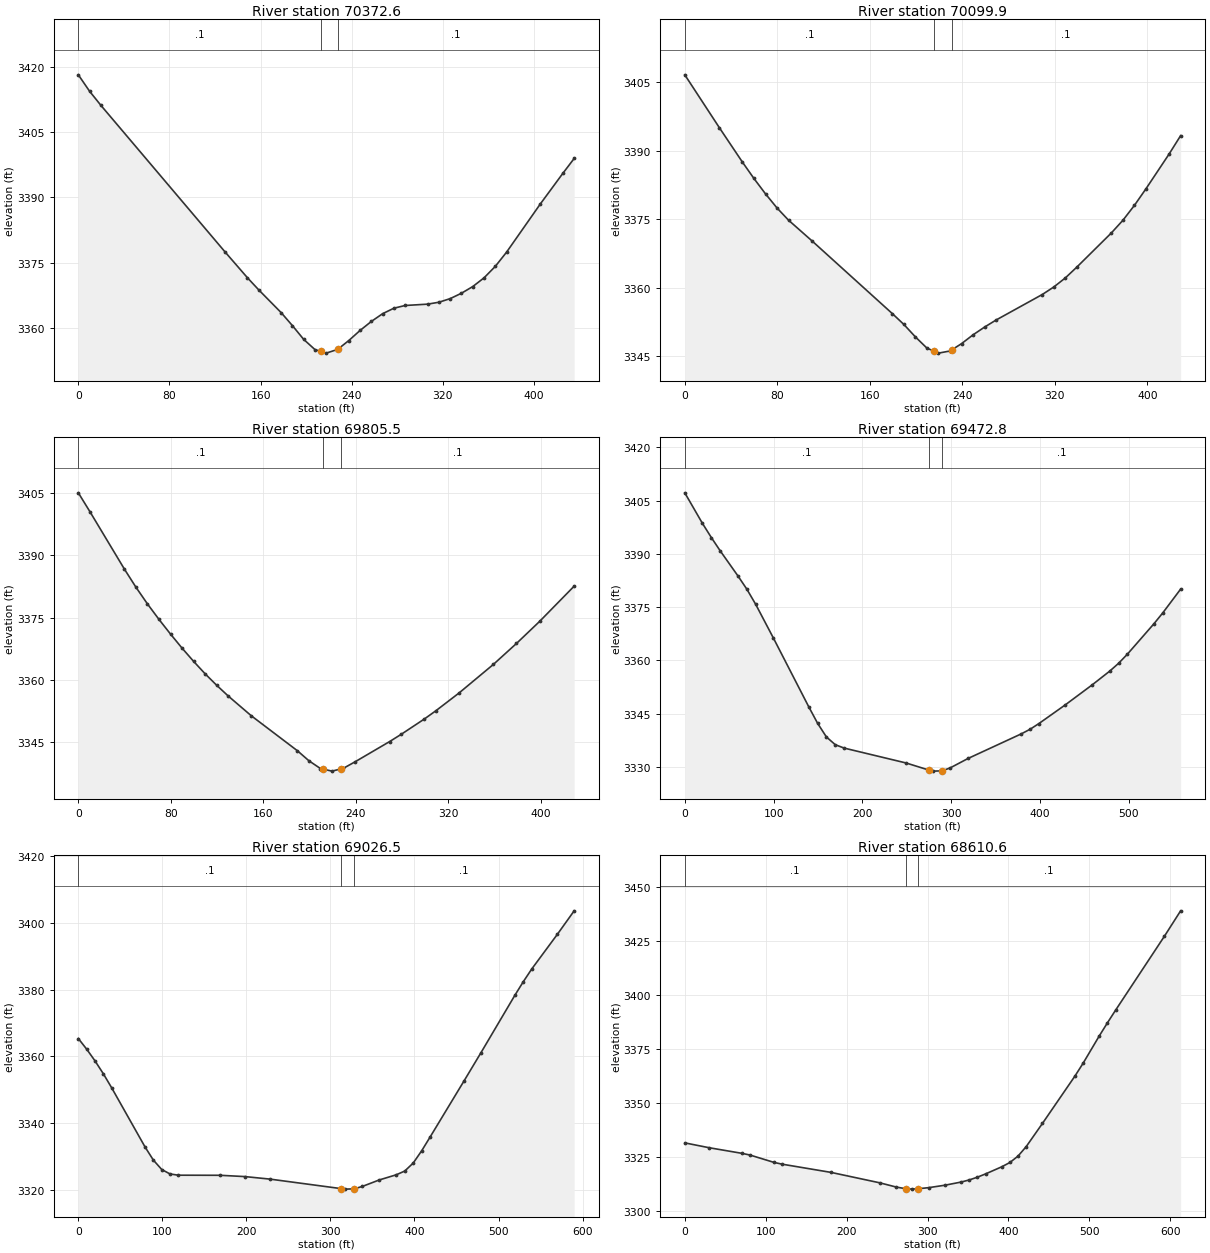
Type RM Length L Ch R = 1 ,70372.6 ,268.1,272.8,277.4
XS GIS Cut Line= 2
     2143409.192      419444.322     2143039.505      419673.985
#Sta/Elev= 30
       0 3418.14     9.9 3414.36    19.8 3411.13   128.6 3377.52   148.4 3371.54
   158.3 3368.76     178 3363.53   187.9 3360.54   197.8 3357.38   207.7 3355.03
   212.6 3354.63   217.6 3354.22   227.6 3355.08   237.4 3357.11   247.3 3359.43
   257.2  3361.5   267.1 3363.28     277 3364.54   286.8 3365.16   306.6 3365.47
   316.5 3365.91   326.4 3366.74   336.3 3367.98   346.2 3369.51   356.1 3371.51
     366 3374.15   375.9 3377.42   405.5 3388.48   425.3 3395.52   435.2 3398.93
#Mann= 3 , 0 , 0
       0      .1       0   212.6    .045       0   227.6      .1       0
Bank Sta=212.6,227.6
XS Rating Curve= 0 ,0
Exp/Cntr=0.3,0.1

Type RM Length L Ch R = 1 ,70099.9 ,285.8,294.4,303
XS GIS Cut Line= 2
     2143309.461      419245.911     2142906.142      419391.433
#Sta/Elev= 30
       0 3406.63    29.9 3395.05    49.9 3387.49    59.8 3383.93    69.8 3380.56
    79.8 3377.46    89.7  3374.8   109.7 3370.33   179.5 3354.33   189.5 3351.95
   199.4 3349.24   209.4 3346.78   215.8 3346.07   219.4 3345.68   229.3 3346.15
   230.8 3346.38   239.3 3347.75   249.3 3349.69   259.3 3351.39   269.2 3352.93
   309.1 3358.51   319.1 3360.16   329.1 3362.15     339 3364.51   368.9    3372
   378.9 3374.78   388.9 3378.06   398.9  3381.7   418.8 3389.27   428.8 3393.31
#Mann= 3 , 0 , 0
       0      .1       0   215.8    .045       0   230.8      .1       0
Bank Sta=215.8,230.8
XS Rating Curve= 0 ,0
Exp/Cntr=0.3,0.1

Type RM Length L Ch R = 1 ,69805.5 ,335.9,332.7,329.5
XS GIS Cut Line= 2
     2143267.937      419042.904     2142839.323      419031.372
#Sta/Elev= 30
       0 3405.07      10 3400.54    39.9 3386.67    49.9  3382.3    59.8  3378.3
    69.8 3374.56    79.8 3371.02    89.7 3367.66    99.7 3364.47   109.7 3361.46
   119.7  3358.7   129.6 3356.13   149.6 3351.36   189.5 3342.93   199.4 3340.53
   209.4 3338.65   211.9 3338.49   219.4 3338.03   226.9 3338.55   229.3 3338.72
   239.3 3340.27   269.2 3345.15   279.2 3346.89   299.1 3350.56   309.1 3352.55
   329.1 3356.82     359 3363.75   378.9 3368.78   398.9 3374.09   428.8 3382.59
#Mann= 3 , 0 , 0
       0      .1       0   211.9    .045       0   226.9      .1       0
Bank Sta=211.9,226.9
XS Rating Curve= 0 ,0
Exp/Cntr=0.3,0.1

Type RM Length L Ch R = 1 ,69472.8 ,446.2,446.3,446.3
XS GIS Cut Line= 2
     2143318.345      418673.207     2142763.642      418737.031
#Sta/Elev= 30
       0 3407.17    19.9 3398.55    29.9 3394.57    39.9 3390.82    59.8 3383.78
    69.8 3380.06    79.8 3375.78    99.7  3366.3   139.6 3346.89   149.6 3342.23
   159.5 3338.39   169.5 3336.21   179.5 3335.26   249.3 3331.06     275 3329.06
   279.2 3328.77     290 3328.85   299.1 3329.71   319.1 3332.35   378.9 3339.26
   388.9 3340.57   398.8 3342.17   428.7 3347.47   458.7 3353.05   478.6 3356.95
   488.6 3359.16   498.5 3361.73   528.4  3370.3   538.4 3373.38   558.4 3380.04
#Mann= 3 , 0 , 0
       0      .1       0     275    .045       0     290      .1       0
Bank Sta=275,290
XS Rating Curve= 0 ,0
Exp/Cntr=0.3,0.1

Type RM Length L Ch R = 1 ,69026.5 ,414.7,415.9,430
XS GIS Cut Line= 3
     2143260.984      418235.384     2142955.272      418270.559
     2142674.826      418302.827
#Sta/Elev= 30
       0 3365.34     9.9 3362.17    19.8 3358.67    29.8 3354.78    39.7 3350.58
    79.4 3332.88    89.3 3328.95    99.3 3326.13   109.2  3324.8   119.1 3324.44
   168.8 3324.41   198.5 3324.02   228.3 3323.26   313.1 3320.41   317.8 3320.27
   328.1 3320.35     338 3321.08   358.1 3323.02   378.3 3324.56   388.4 3325.68
   398.5 3328.08   408.6 3331.76   418.6 3335.87     459 3352.67   479.1  3361.1
   519.4 3378.26   529.5 3382.36   539.6 3386.18   569.9 3396.49     590 3403.56
#Mann= 3 , 0 , 0
       0      .1       0   313.1    .045       0   328.1      .1       0
Bank Sta=313.1,328.1
XS Rating Curve= 0 ,0
Exp/Cntr=0.3,0.1

Type RM Length L Ch R = 1 ,68610.6 ,358.2,357,355.9
XS GIS Cut Line= 2
     2143218.854      417847.431     2142610.173      417917.466
#Sta/Elev= 30
       0 3331.46    30.1 3329.21    70.3 3326.63    80.4 3325.84   110.5 3322.38
   120.5 3321.57   180.8 3317.77   241.1 3312.93   261.2 3310.99   272.8 3310.22
   281.2 3310.02   287.8 3310.17   301.3  3310.7   321.4 3311.83   341.5  3313.3
   351.6 3314.29   361.6 3315.56   371.6 3317.06   391.7 3320.38   401.8 3322.38
   411.8 3325.34   421.9 3329.74     442  3340.5   482.1 3362.42   492.2 3368.38
   512.3 3381.11   522.3 3387.13   532.3 3392.95   592.6  3427.2   612.7 3439.02
#Mann= 3 , 0 , 0
       0      .1       0   272.8    .045       0   287.8      .1       0
Bank Sta=272.8,287.8
XS Rating Curve= 0 ,0
Exp/Cntr=0.3,0.1

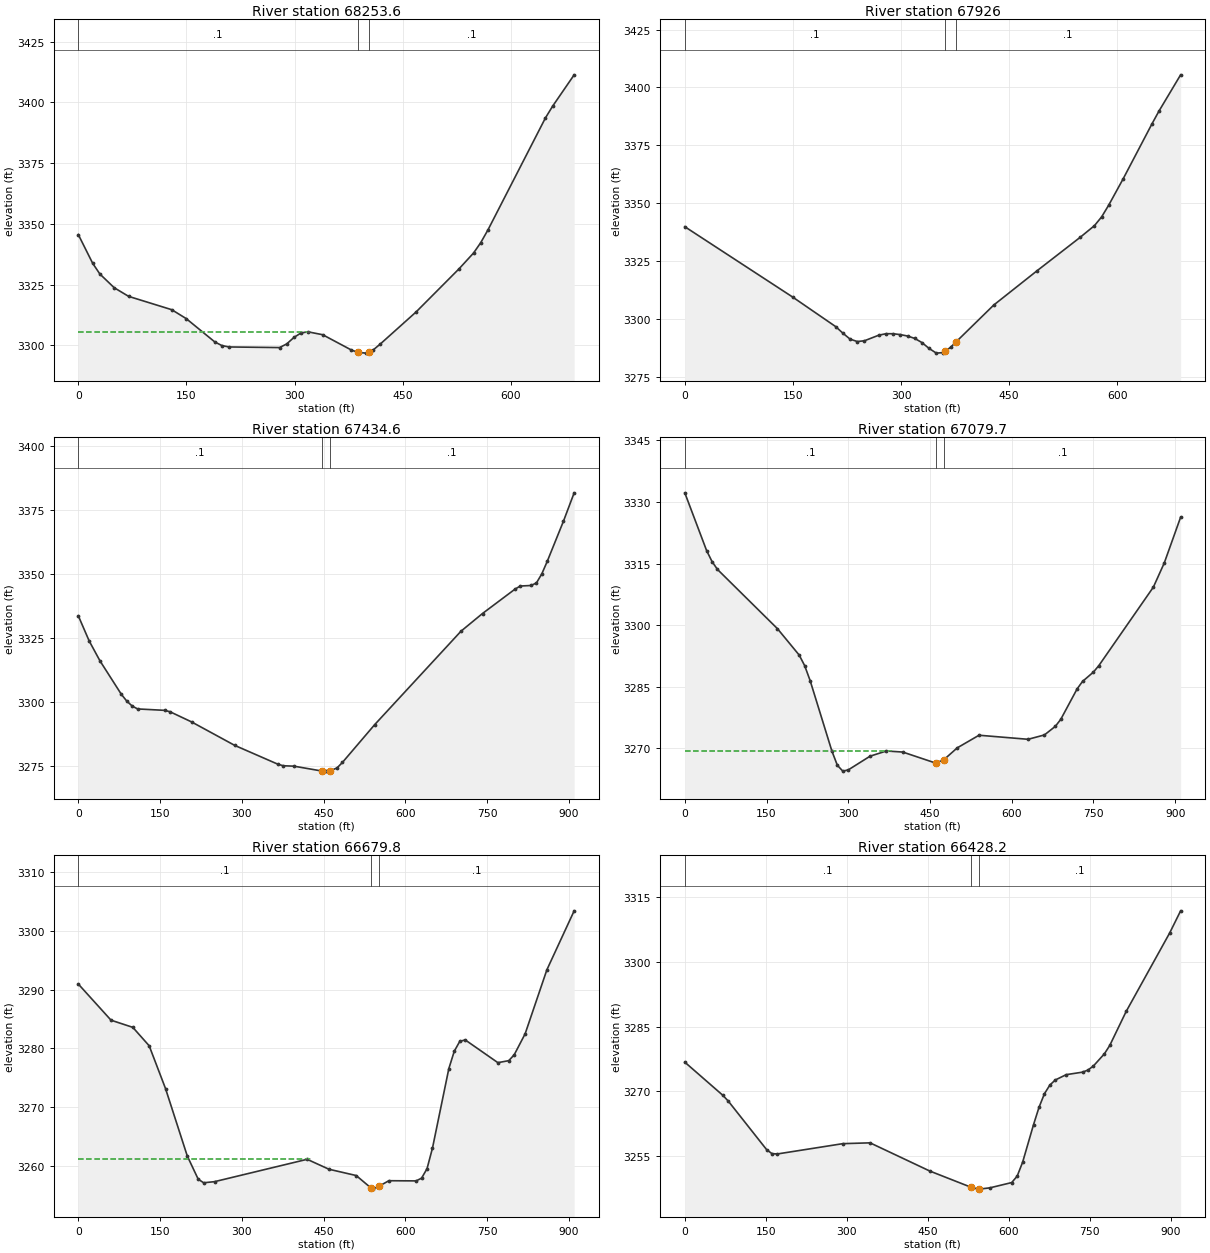
Type RM Length L Ch R = 1 ,68253.6 ,332.7,327.6,322.4
XS GIS Cut Line= 2
     2143245.926      417488.092     2142565.827      417591.634
#Sta/Elev= 30
       0 3345.54    19.9 3333.74    29.9 3329.32    49.8 3323.67    69.8 3320.12
   129.6 3314.63   149.6 3310.98   189.4 3301.34   199.4 3299.83   209.4 3299.29
   279.2 3299.04   289.1 3300.54   299.1  3303.2   309.1 3305.09     319  3305.5
     339 3304.33   378.9 3298.02   387.6  3297.1   398.8 3296.75   402.6 3297.23
   408.8 3297.99   418.7 3300.44   468.6  3313.7   528.4 3331.53   548.4    3338
   558.3 3342.24   568.3 3347.48   648.1 3393.62     658 3398.42   687.9 3411.34
#Mann= 3 , 0 , 0
       0      .1       0   387.6    .045       0   402.6      .1       0
#XS Ineff= 2 , 0
          323.65 3305.58
Permanent Ineff=
       F       F
Bank Sta=387.6,402.6
XS Rating Curve= 0 ,0
Exp/Cntr=0.3,0.1

Type RM Length L Ch R = 1 ,67926   ,490,491.4,492.9
XS GIS Cut Line= 2
     2143099.593      417101.353     2142460.037      417354.778
#Sta/Elev= 30
       0  3339.9   149.6 3309.54   209.4 3296.76   219.3 3293.95   229.3 3291.38
   239.3 3290.33   249.2 3290.66   269.2 3293.08   279.2 3293.71   289.1  3293.7
   299.1 3293.32   309.1 3292.71     319 3291.68     329 3289.89     339 3287.34
     349 3285.33   358.9 3285.58   360.9 3286.04   368.9  3287.9   375.9 3290.04
   428.7  3306.1   488.5 3320.83   548.4 3335.28   568.3 3340.34   578.3 3344.13
   588.2 3349.24   608.2 3360.58   648.1 3384.26     658 3389.88   687.9 3405.45
#Mann= 3 , 0 , 0
       0      .1       0   360.9    .045       0   375.9      .1       0
Bank Sta=360.9,375.9
XS Rating Curve= 0 ,0
Exp/Cntr=0.3,0.1

Type RM Length L Ch R = 1 ,67434.6 ,360.7,354.9,349.2
XS GIS Cut Line= 3
     2143028.433      416636.523     2142595.221      416775.634
     2142162.008      416914.745
#Sta/Elev= 30
       0 3333.61    19.8 3323.87    39.6 3316.09    79.1 3302.94      89 3300.33
    98.9 3298.41   108.8 3297.29   158.3 3296.74   168.2  3296.2   207.7 3292.24
   286.8 3283.09     366 3275.74   375.9 3275.12   395.6 3274.96   447.5 3273.04
     455 3273.02   462.5 3273.17   474.8 3274.27   484.7 3276.41     544 3291.18
   702.3 3327.62   741.8 3334.53   801.2    3344   811.1 3345.25   830.9 3345.46
   840.8 3346.47   850.6 3349.98   860.5 3354.83   890.2 3370.46     910 3381.62
#Mann= 3 , 0 , 0
       0      .1       0   447.5    .045       0   462.5      .1       0
Bank Sta=447.5,462.5
XS Rating Curve= 0 ,0
Exp/Cntr=0.3,0.1

Type RM Length L Ch R = 1 ,67079.7 ,396.7,399.8,403
XS GIS Cut Line= 2
       2142894.5       416188.18     2142124.839      416673.692
#Sta/Elev= 30
       0 3332.23      40 3318.16      50 3315.47      60 3313.55     170 3299.12
     210 3292.67     220  3290.1     230 3286.47     270 3269.27     280 3265.81
     290 3264.39     300 3264.69     340 3268.03     370  3269.3     400 3269.04
   460.7 3266.34   475.7  3267.2     500 3270.06     540 3273.14     630 3272.15
     660 3273.21     680  3275.3     690 3277.01     720 3284.43     730 3286.26
     750 3288.54     760 3290.13     860 3309.25     880 3315.14     910 3326.29
#Mann= 3 , 0 , 0
       0      .1       0   460.7    .045       0   475.7      .1       0
#XS Ineff= 2 , 0
          379.98 3269.24
Permanent Ineff=
       F       F
Bank Sta=460.7,475.7
XS Rating Curve= 0 ,0
Exp/Cntr=0.3,0.1

Type RM Length L Ch R = 1 ,66679.8 ,247.2,251.6,256.1
XS GIS Cut Line= 2
     2142734.437      415905.612     2141908.376       416287.35
#Sta/Elev= 30
       0 3290.94      60  3284.8     100 3283.58     130 3280.45     160 3273.18
     200  3261.7     220 3257.77     230 3257.16     250 3257.35     420 3261.15
     460 3259.46     510 3258.39   537.5 3256.25     540 3256.08   552.5 3256.61
     570 3257.51     620 3257.48     630 3257.95     640 3259.56     650 3263.07
     680 3276.57     690 3279.53     700 3281.19     710 3281.45     770 3277.58
     790 3277.92     800 3278.92     820 3282.48     860 3293.38     910 3303.39
#Mann= 3 , 0 , 0
       0      .1       0   537.5    .045       0   552.5      .1       0
#XS Ineff= 2 , 0
          427.81 3261.12
Permanent Ineff=
       F       F
Bank Sta=537.5,552.5
XS Rating Curve= 0 ,0
Exp/Cntr=0.3,0.1

Type RM Length L Ch R = 1 ,66428.2 ,230.5,225.5,220.5
XS GIS Cut Line= 2
     2142645.862        415793.9     2141754.595      416014.739
#Sta/Elev= 30
       0 3276.77    70.6 3269.09    80.7 3267.74   151.4 3256.57   161.4 3255.62
   171.5 3255.55   292.6 3257.93   343.1 3258.12   454.1 3251.58   530.4 3247.84
   544.9 3247.42   545.4 3247.42   565.1 3247.72   605.4 3248.94   615.5 3250.42
   625.6 3253.64   645.8 3262.32   655.9 3266.31     666 3269.47     676 3271.47
   686.1 3272.65   706.3 3273.88   736.6 3274.46   746.7 3274.95   756.8  3275.9
     777 3278.69     787 3280.64   817.3 3288.48     898 3306.65   918.2 3311.75
#Mann= 3 , 0 , 0
       0      .1       0   530.4    .045       0   545.4      .1       0
Bank Sta=530.4,545.4
XS Rating Curve= 0 ,0
Exp/Cntr=0.3,0.1

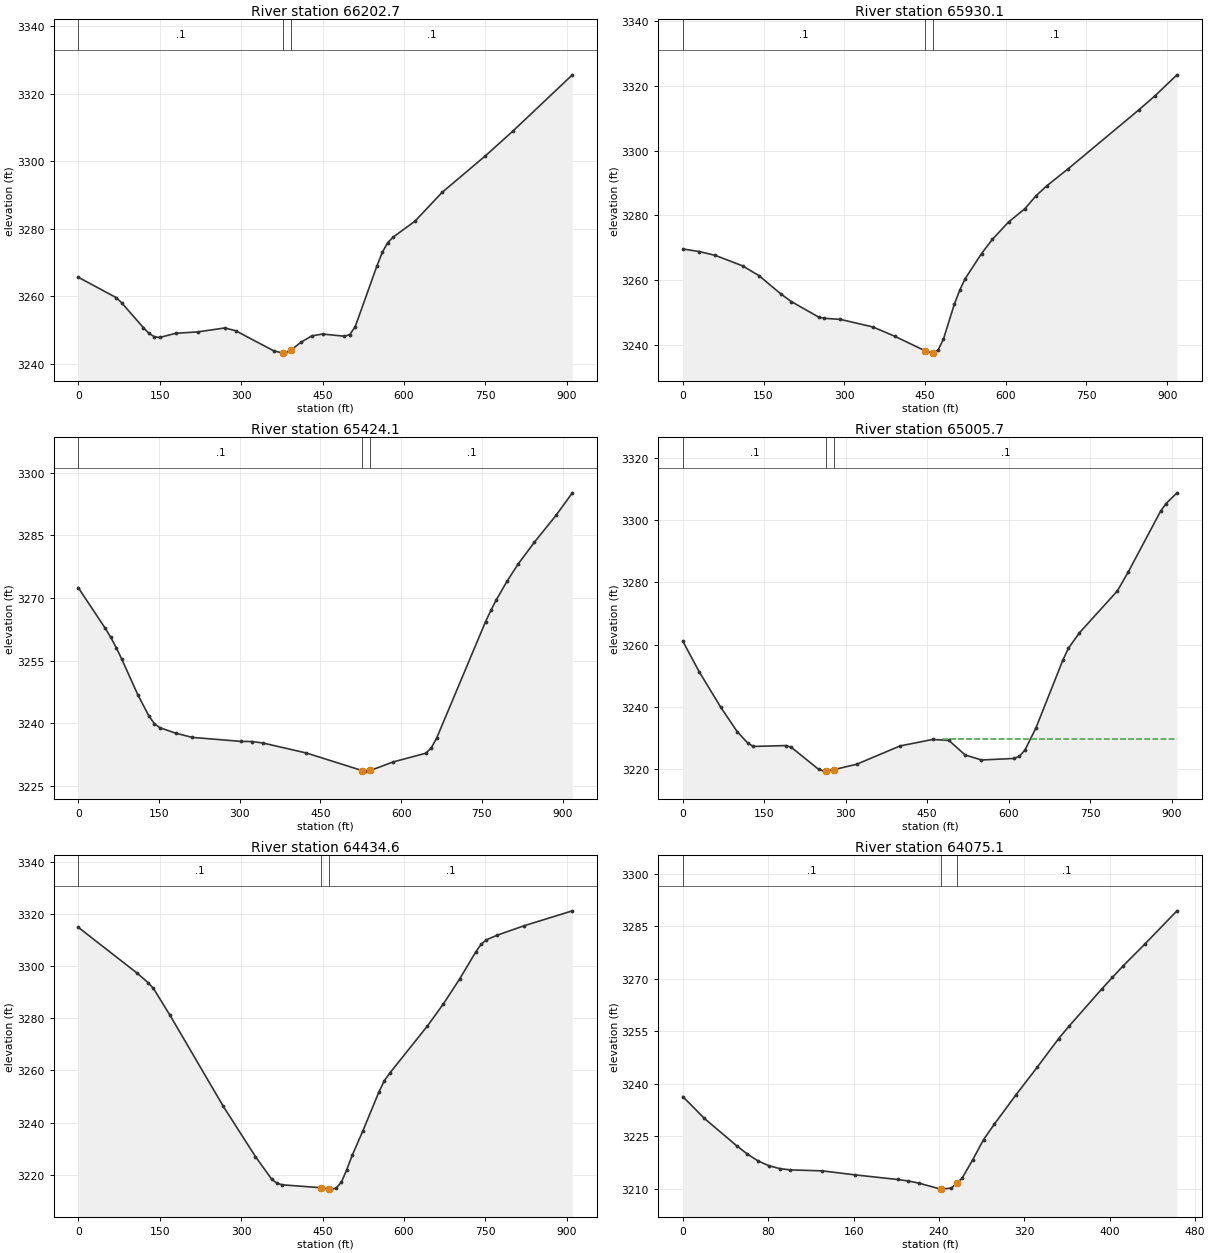
Type RM Length L Ch R = 1 ,66202.7 ,268.1,272.6,277.1
XS GIS Cut Line= 2
     2142457.297      415549.956     2141631.236      415931.693
#Sta/Elev= 30
       0  3265.6      70 3259.54      80 3258.01     120 3250.64     130 3249.01
     140 3247.96     150 3247.74     180 3248.99     220 3249.39     270 3250.56
     290 3249.73     360 3243.78   376.9 3243.13     380  3243.1   391.9 3244.01
     410  3246.3     430 3248.21     450 3248.76     490 3248.11     500 3248.59
     510 3250.91     550 3268.91     560 3272.98     570 3275.86     580 3277.49
     620 3282.18     670 3290.72     750 3301.59     800 3308.83     910 3325.57
#Mann= 3 , 0 , 0
       0      .1       0   376.9    .045       0   391.9      .1       0
Bank Sta=376.9,391.9
XS Rating Curve= 0 ,0
Exp/Cntr=0.3,0.1

Type RM Length L Ch R = 1 ,65930.1 ,520.4,506,491.5
XS GIS Cut Line= 2
     2142411.992      415373.499     2141520.725      415594.338
#Sta/Elev= 30
       0 3269.64    30.3 3268.85    60.5 3267.66     111 3264.43   141.3 3261.44
   181.6 3255.84   201.8  3253.4   252.3 3248.64   262.4 3248.26   292.6 3247.92
   353.2 3245.58   393.5 3242.74     450 3238.24   464.2 3237.51     465 3237.59
   474.2 3238.41   484.3 3241.84   504.5  3252.6   514.6 3256.95   524.7 3260.49
     555 3268.21   575.2  3272.6   605.4 3277.98   635.7 3282.07   655.9 3285.98
     676 3289.08   716.4 3294.42   847.6 3312.58   877.9 3316.96   918.2 3323.36
#Mann= 3 , 0 , 0
       0      .1       0     450    .045       0     465      .1       0
Bank Sta=450,465
XS Rating Curve= 0 ,0
Exp/Cntr=0.3,0.1

Type RM Length L Ch R = 1 ,65424.1 ,417.1,418.5,419.8
XS GIS Cut Line= 2
     2142058.564       414654.47     2141469.821      415359.103
#Sta/Elev= 30
       0 3272.48    50.4  3262.7    60.5 3260.55    70.6 3258.14    80.7 3255.42
     111 3246.77   131.2 3241.81   141.3 3239.97   151.4 3238.97   181.6 3237.64
   211.9 3236.65   302.7 3235.69   322.9 3235.66   343.1 3235.31   423.8 3232.92
   527.9  3228.7   534.8 3228.58   542.9 3228.74   585.2 3230.78   645.8 3232.86
   655.9 3234.12     666 3236.48   756.8  3264.3   766.9 3267.08     777 3269.58
   797.1 3274.07   817.3  3278.1   847.6 3283.33     888 3289.79   918.2 3295.15
#Mann= 3 , 0 , 0
       0      .1       0   527.9    .045       0   542.9      .1       0
Bank Sta=527.9,542.9
XS Rating Curve= 0 ,0
Exp/Cntr=0.3,0.1

Type RM Length L Ch R = 1 ,65005.7 ,571.1,571.1,571.1
XS GIS Cut Line= 2
     2141833.061      414484.685     2141206.233      415144.372
#Sta/Elev= 30
       0 3261.13      30 3251.33      70 3239.87     100 3232.11     120 3228.33
     130 3227.32     190 3227.61     200 3227.01     250 3219.99     260  3219.4
   263.2 3219.45   278.2 3219.88     320  3221.6     400 3227.48     460 3229.57
     490 3229.26     520 3224.58     550 3222.98     610 3223.47     620  3224.2
     630 3226.17     650 3233.14     700 3255.08     710  3258.8     730 3263.73
     800  3277.2     820 3283.23     880  3302.9     890  3305.3     910 3308.74
#Mann= 3 , 0 , 0
       0      .1       0   263.2    .045       0   278.2      .1       0
#XS Ineff= 2 , 0
                          479.19          3229.7
Permanent Ineff=
       F       F
Bank Sta=263.2,278.2
XS Rating Curve= 0 ,0
Exp/Cntr=0.3,0.1

Type RM Length L Ch R = 1 ,64434.6 ,373.8,359.5,345.2
XS GIS Cut Line= 3
     2141545.257       413958.49     2141231.843      414288.333
     2140918.429      414618.176
#Sta/Elev= 30
       0  3314.9   108.8 3297.25   128.6 3293.67   138.5 3291.44   168.2 3281.43
   267.1 3246.23   326.4 3226.94   356.1 3218.32     366 3216.72   375.9 3216.11
   447.5 3214.99   462.5 3214.52   464.9 3214.46   474.8 3214.81   484.7 3217.16
   494.6 3221.98   504.5  3227.4   524.2 3236.83   553.9 3251.81   563.8 3256.08
   573.7 3258.96   642.9    3277   672.6 3285.55   702.3 3295.04     732  3305.4
   741.8 3308.34   751.7 3310.09   771.5 3311.86     821 3315.48     910 3321.21
#Mann= 3 , 0 , 0
       0      .1       0   447.5    .045       0   462.5      .1       0
Bank Sta=447.5,462.5
XS Rating Curve= 0 ,0
Exp/Cntr=0.3,0.1

Type RM Length L Ch R = 1 ,64075.1 ,400.6,430.3,459
XS GIS Cut Line= 2
     2140981.895      413858.148     2140917.069      414316.538
#Sta/Elev= 30
       0 3236.36    20.1 3230.16    50.3 3222.36    60.4 3219.97    70.4 3218.02
    80.5 3216.64    90.6 3215.82   100.6 3215.44   130.8 3215.16     161 3214.03
   201.3  3212.7   211.4 3212.27   221.4 3211.65   241.5 3209.95   241.7 3209.95
   251.6 3210.23   256.7 3211.67   261.7 3213.07   271.7 3218.38   281.8 3224.09
   291.9 3228.49     312 3236.79   332.1 3244.76   352.2 3252.92   362.3  3256.6
   392.5 3267.04   402.6  3270.4   412.6 3273.66   432.8 3279.84     463 3289.36
#Mann= 3 , 0 , 0
       0      .1       0   241.7    .045       0   256.7      .1       0
Bank Sta=241.7,256.7
XS Rating Curve= 0 ,0
Exp/Cntr=0.3,0.1