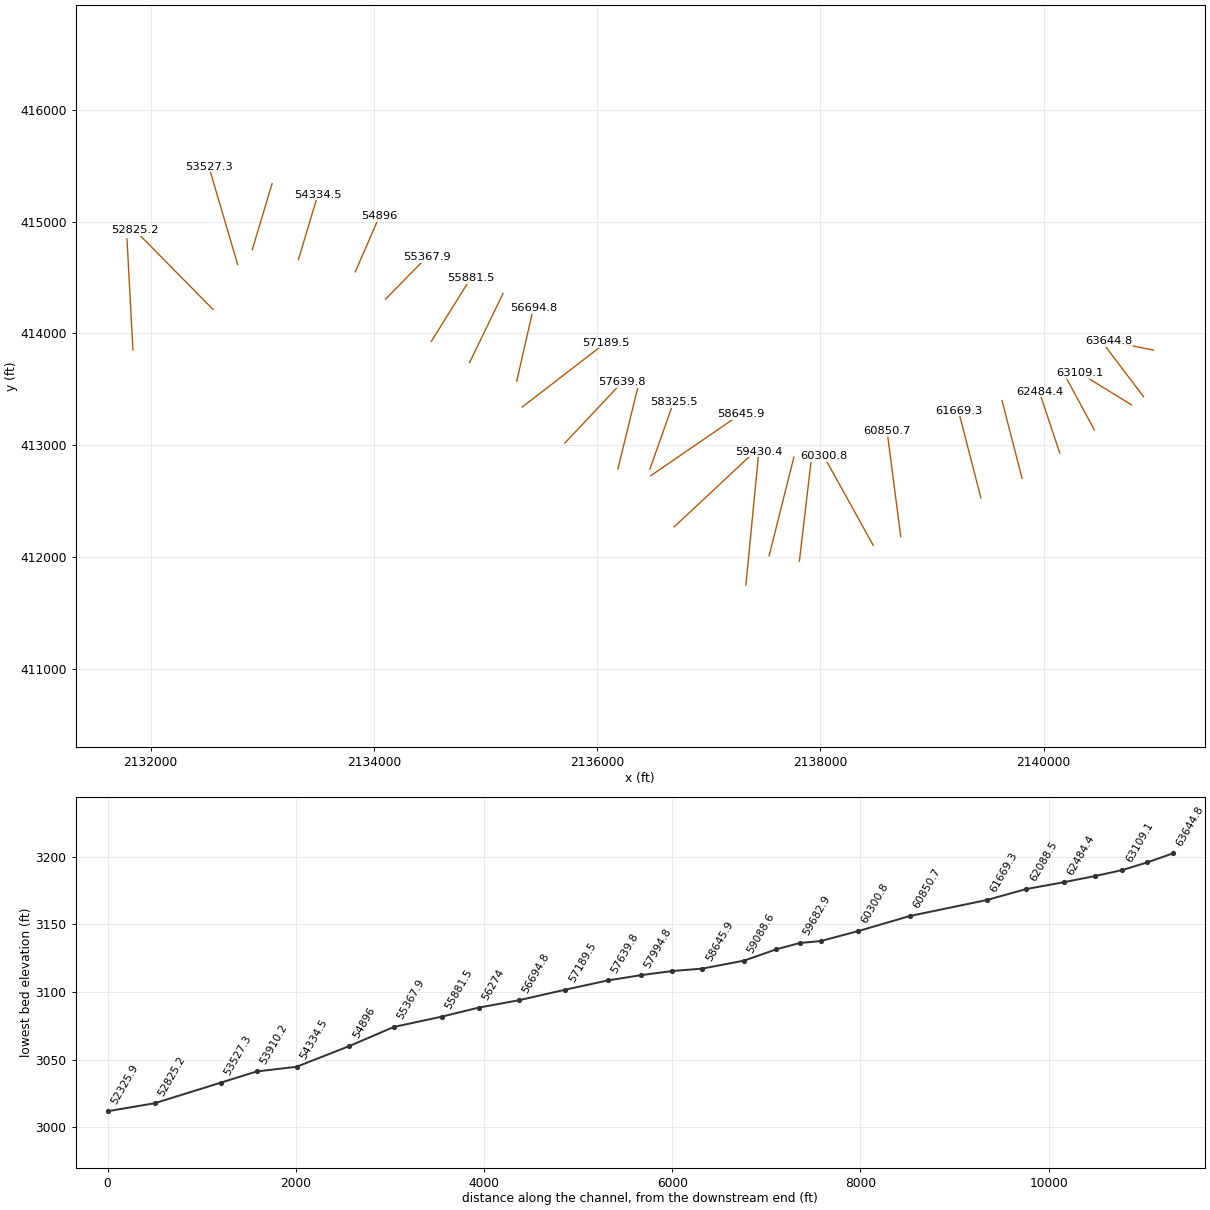
HEC-RAS study SFrkChryRv.prj: SFrkChryRv

--- SFrkChryRv.g01 (geometry) --- (continued)

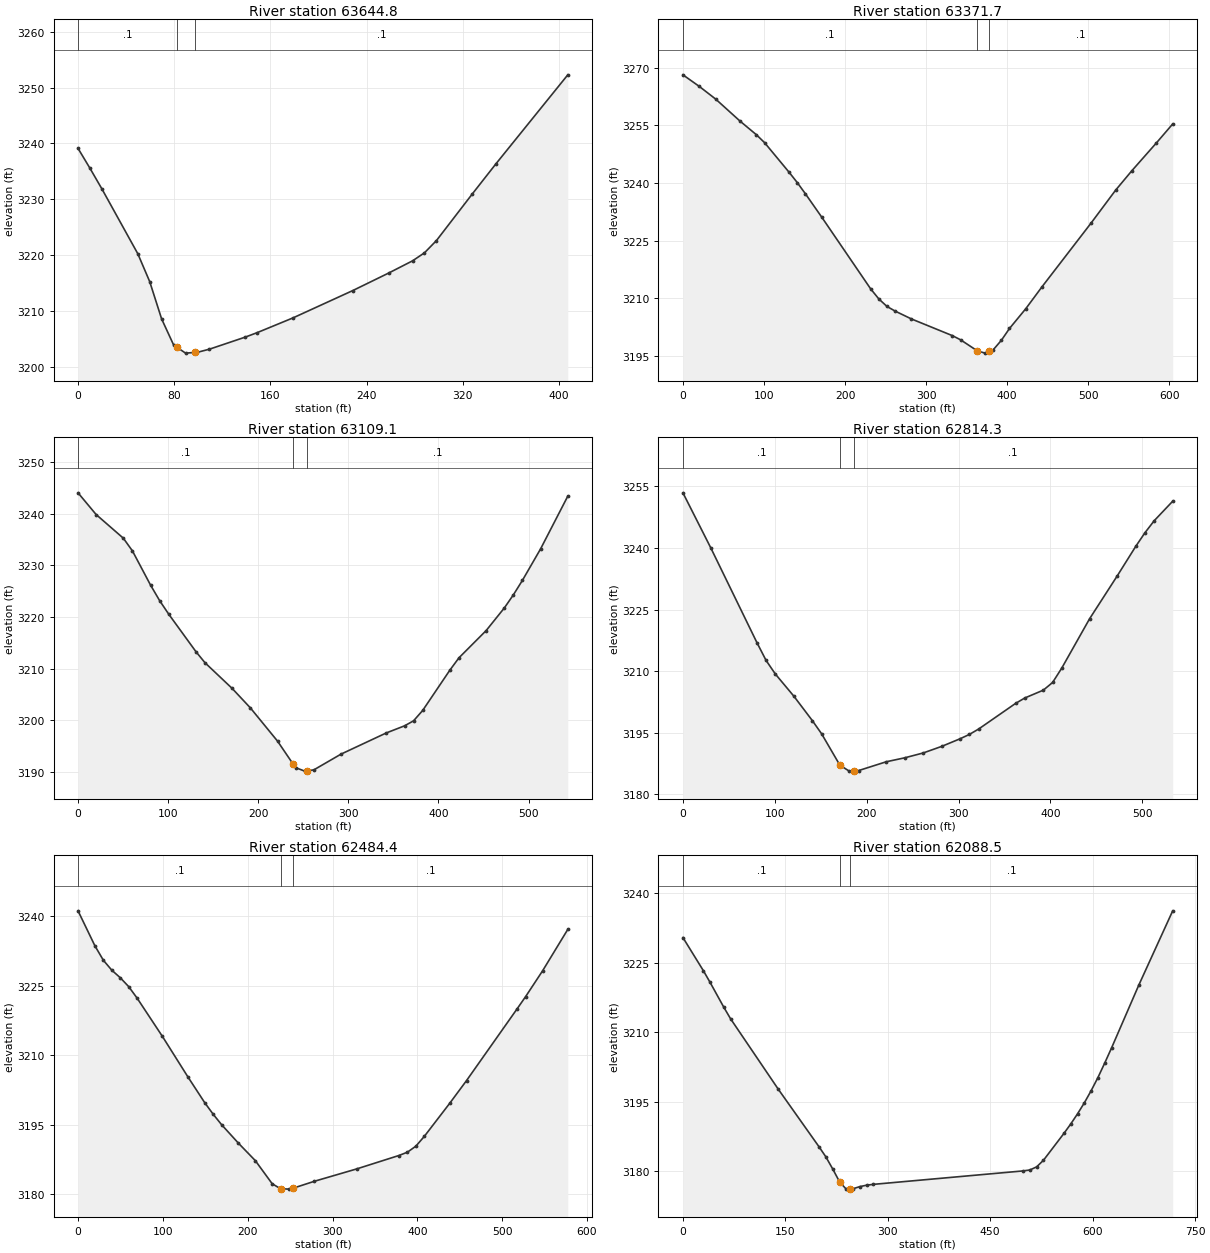
Type RM Length L Ch R = 1 ,63644.8 ,289.7,273.1,256.5
XS GIS Cut Line= 2
     2140984.392      413850.937     2140584.847      413929.775
#Sta/Elev= 23
       0 3239.11     9.9 3235.56    19.9 3231.84    49.7 3220.26    59.6 3215.27
    69.5  3208.6    79.5 3203.93      82 3203.56    89.4 3202.48      97  3202.6
    99.3 3202.63   109.3 3203.19   139.1 3205.35     149 3206.15   178.8 3208.79
   228.5 3213.68   258.3 3216.81   278.1 3218.99     288 3220.42     298 3222.62
   327.8 3230.96   347.6 3236.39   407.2 3252.27
#Mann= 3 , 0 , 0
       0      .1       0      82    .045       0      97      .1       0
Bank Sta=82,97
XS Rating Curve= 0 ,0
Exp/Cntr=0.3,0.1

Type RM Length L Ch R = 1 ,63371.7 ,254.1,262.6,271.2
XS GIS Cut Line= 2
     2140896.071      413433.553     2140530.882      413914.824
#Sta/Elev= 30
       0 3268.13    20.1 3265.13    40.3 3261.84    70.5 3256.09    90.6 3252.56
   100.7  3250.5   130.9 3242.82     141 3240.13     151 3237.23   171.2 3231.14
   231.6 3212.48   241.7 3209.86   251.7 3207.92   261.8 3206.71   281.9 3204.67
   332.3 3200.34   342.4 3199.26   362.9 3196.41   372.6 3195.79   377.9 3196.24
   382.6 3196.63   392.7  3199.1   402.8  3202.2   422.9 3207.34     443 3213.06
   503.4 3229.59   533.7 3238.15   553.8 3243.22     584 3250.43   604.1 3255.36
#Mann= 3 , 0 , 0
       0      .1       0   362.9    .045       0   377.9      .1       0
Bank Sta=362.9,377.9
XS Rating Curve= 0 ,0
Exp/Cntr=0.3,0.1

Type RM Length L Ch R = 1 ,63109.1 ,306.7,294.8,282.8
XS GIS Cut Line= 2
     2140788.093      413359.874     2140325.543      413645.378
#Sta/Elev= 30
       0    3244    20.1  3239.8    50.3 3235.22    60.4 3232.76    80.5 3226.15
    90.6 3223.14   100.7 3220.52   130.9 3213.27   140.9 3211.14   171.1 3206.16
   191.3  3202.4   221.4 3195.98   238.8 3191.51   241.6 3190.84   251.6 3190.17
   253.8 3190.22   261.7 3190.41   291.9 3193.46   342.2 3197.56   362.4 3198.93
   372.4  3199.9   382.5  3201.9   412.7  3209.7   422.8 3212.09     453 3217.36
   473.1 3221.72   483.2 3224.27   493.2 3227.06   513.4 3233.16   543.6 3243.36
#Mann= 3 , 0 , 0
       0      .1       0   238.8    .045       0   253.8      .1       0
Bank Sta=238.8,253.8
XS Rating Curve= 0 ,0
Exp/Cntr=0.3,0.1

Type RM Length L Ch R = 1 ,62814.3 ,333.7,329.9,326
XS GIS Cut Line= 2
     2140454.994      413136.287     2140202.011      413605.454
#Sta/Elev= 30
       0 3253.39    30.2 3240.05    80.5 3216.96    90.5 3212.61   100.6  3209.3
   120.7 3203.92   140.8 3197.98   150.9 3194.77   170.8 3187.13     181 3185.68
   185.8 3185.74   191.1 3185.81   221.3 3187.96   241.4 3188.92   261.5  3190.1
   281.6  3191.7   301.7 3193.56   311.8 3194.62   321.8 3195.92   362.1 3202.17
   372.1 3203.48   392.2 3205.38   402.3 3207.25   412.3 3210.76   442.5 3222.73
   472.7  3233.2   492.8 3240.37   502.9 3243.71   512.9 3246.61     533 3251.35
#Mann= 3 , 0 , 0
       0      .1       0   170.8    .045       0   185.8      .1       0
Bank Sta=170.8,185.8
XS Rating Curve= 0 ,0
Exp/Cntr=0.3,0.1

Type RM Length L Ch R = 1 ,62484.4 ,397.6,396,394.2
XS GIS Cut Line= 2
     2140145.639      412928.845     2139962.781      413476.442
#Sta/Elev= 30
       0 3241.15    19.9  3233.6    29.9 3230.48    39.8 3228.35    49.8 3226.72
    59.7 3224.81    69.7 3222.31    99.5 3214.06   129.4 3205.37   149.3 3199.79
   159.3 3197.29   169.2 3195.04   189.1 3191.04     209 3187.28   228.9 3182.29
   238.7 3181.23   248.8 3181.14   253.7 3181.35   278.7 3182.84   328.5  3185.5
   378.2 3188.39   388.2  3189.1   398.2  3190.4   408.1  3192.5     438 3199.62
   457.9 3204.54   517.6 3220.03   527.6 3222.66   547.5 3228.19   577.3 3237.15
#Mann= 3 , 0 , 0
       0      .1       0   238.7    .045       0   253.7      .1       0
Bank Sta=238.7,253.7
XS Rating Curve= 0 ,0
Exp/Cntr=0.3,0.1

Type RM Length L Ch R = 1 ,62088.5 ,419.2,419.2,419.2
XS GIS Cut Line= 2
     2139807.429      412703.372     2139628.295      413397.896
#Sta/Elev= 30
       0 3230.41    29.9 3223.27    39.8 3220.73    59.8 3215.39    69.7  3212.9
   139.5 3197.71   199.2 3185.28   209.2 3183.11   219.2 3180.51   229.5 3177.66
   239.1 3176.12   244.5 3176.17     249  3176.2     259 3176.66     269 3176.97
   278.9 3177.15   498.1 3180.05     508 3180.25     518 3180.93     528 3182.36
   557.9 3188.14   567.8 3190.16   577.8 3192.36   587.8 3194.74   597.7 3197.34
   607.7  3200.2   617.6 3203.31   627.6 3206.57   667.4  3220.1   717.2 3236.18
#Mann= 3 , 0 , 0
       0      .1       0   229.5    .045       0   244.5      .1       0
Bank Sta=229.5,244.5
XS Rating Curve= 0 ,0
Exp/Cntr=0.3,0.1

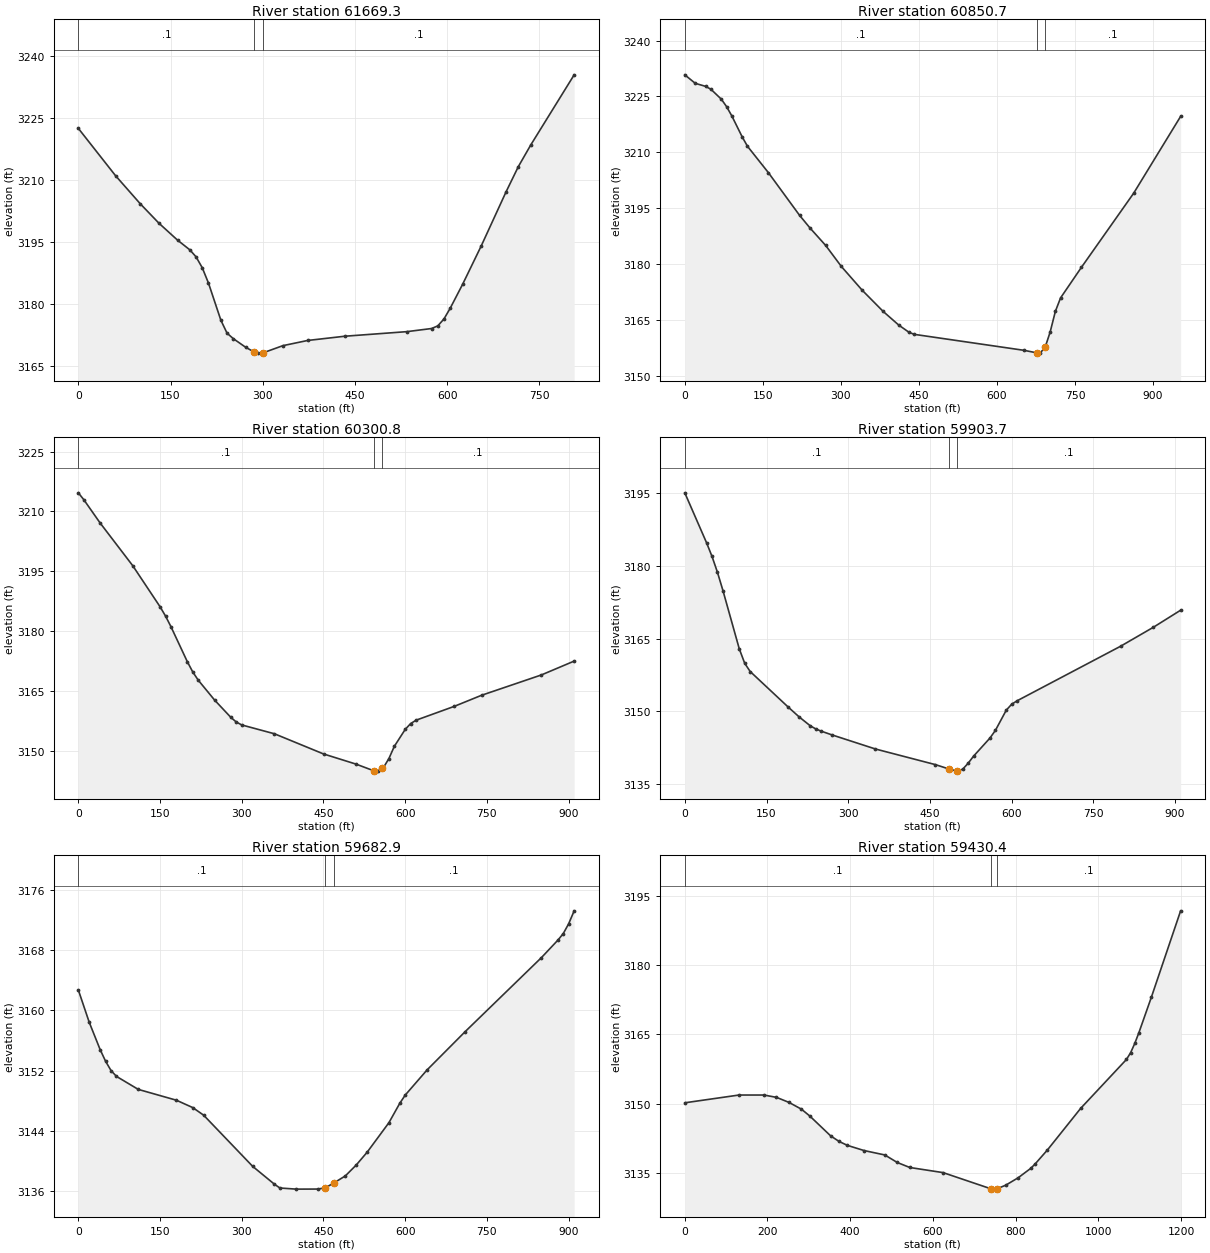
Type RM Length L Ch R = 1 ,61669.3 ,820.9,818.6,816.4
XS GIS Cut Line= 2
     2139439.347      412525.867     2139237.849      413307.097
#Sta/Elev= 30
       0 3222.55    60.5 3211.08   100.8 3204.25   131.1 3199.55   161.4 3195.44
   181.5 3193.07   191.6 3191.37   201.7 3188.72   211.8    3185     232 3175.98
     242 3172.86   252.1 3171.54   272.3 3169.44   286.3 3168.27   292.5 3168.02
   301.3 3168.13   332.8 3169.83   373.1 3171.09   433.6 3172.12   534.5 3173.23
   574.8 3173.99   584.9 3174.63     595 3176.32   605.1 3178.91   625.3 3184.72
   655.5    3194   695.9 3207.12     716 3213.28   736.2 3218.53   806.8 3235.54
#Mann= 3 , 0 , 0
       0      .1       0   286.3    .045       0   301.3      .1       0
Bank Sta=286.3,301.3
XS Rating Curve= 0 ,0
Exp/Cntr=0.3,0.1

Type RM Length L Ch R = 1 ,60850.7 ,540.9,549.8,558.5
XS GIS Cut Line= 2
     2138720.834      412180.215     2138598.586      413125.231
#Sta/Elev= 30
       0 3230.81    20.1 3228.53    40.1 3227.71    50.2 3226.94    70.2 3224.28
    80.2  3222.3    90.3 3219.81   110.3 3214.16   120.4 3211.66   160.5  3204.6
   220.7  3193.1   240.7 3189.72   270.8 3185.04   300.9 3179.41     341 3173.03
   381.2 3167.36   411.2 3163.69   431.3 3161.72   441.3  3161.2     652 3156.92
   677.8 3156.21   682.1 3156.17   692.1 3157.55   692.8 3157.85   702.1  3161.8
   712.2 3167.38   722.2 3170.99   762.3 3179.19   862.6 3199.05   952.9 3219.66
#Mann= 3 , 0 , 0
       0      .1       0   677.8    .045       0   692.8      .1       0
Bank Sta=677.8,692.8
XS Rating Curve= 0 ,0
Exp/Cntr=0.3,0.1

Type RM Length L Ch R = 1 ,60300.8 ,411.5,397.1,383
XS GIS Cut Line= 2
     2138473.452      412104.633     2138032.057      412900.552
#Sta/Elev= 30
       0 3214.67      10 3212.96      40 3207.12     100  3196.4     150 3186.15
     160 3183.83     170 3181.16     200  3172.4     210 3169.83     220 3167.78
     250  3162.8     280 3158.44     290 3157.28     300 3156.55     360 3154.34
   450.1 3149.29   510.1 3146.73     543 3145.04   550.1 3144.99     558 3145.71
   560.1 3145.89   570.1 3148.15   580.1 3151.22   600.1 3155.46   610.1 3156.91
   620.1 3157.75   690.1 3161.21   740.1 3163.98   850.1 3169.08   910.1 3172.54
#Mann= 3 , 0 , 0
       0      .1       0     543    .045       0     558      .1       0
Bank Sta=543,558
XS Rating Curve= 0 ,0
Exp/Cntr=0.3,0.1

Type RM Length L Ch R = 1 ,59903.7 ,223.7,220.8,217.8
XS GIS Cut Line= 2
     2137812.684      411961.845      2137918.85       412865.75
#Sta/Elev= 30
       0 3195.13      40  3184.8      50 3181.98      60 3178.69      70 3174.95
     100  3162.9     110 3159.91     120 3158.22     190 3150.85     210 3148.83
     230 3147.03     240 3146.38     250 3145.91     270 3145.13     350 3142.21
   460.1 3138.98   485.2 3138.07   500.1 3137.64   500.2 3137.65   510.1 3138.04
   520.1 3139.27   530.1 3140.74   560.1 3144.47   570.1 3146.05   590.1 3150.24
   600.1 3151.47   610.1 3152.18   800.1 3163.45   860.1 3167.36   910.1 3170.88
#Mann= 3 , 0 , 0
       0      .1       0   485.2    .045       0   500.2      .1       0
Bank Sta=485.2,500.2
XS Rating Curve= 0 ,0
Exp/Cntr=0.3,0.1

Type RM Length L Ch R = 1 ,59682.9 ,249.1,252.6,256.1
XS GIS Cut Line= 2
     2137541.415      412008.745     2137763.134      412891.443
#Sta/Elev= 30
       0 3162.72      20 3158.42      40 3154.79      50 3153.24      60    3152
      70 3151.22     110 3149.49     180 3148.05     210 3147.07     230 3146.06
     320 3139.25     360 3136.87     370 3136.37     400 3136.22   440.1 3136.23
   453.6 3136.41   468.6 3137.02   490.1 3137.98   510.1 3139.43   530.1 3141.13
   570.1 3145.06   590.1 3147.65   600.1 3148.74   640.1 3152.08   710.1 3157.18
   850.1 3167.03   880.1 3169.34   890.1 3170.22   900.1 3171.54   910.1 3173.25
#Mann= 3 , 0 , 0
       0      .1       0   453.6    .045       0   468.6      .1       0
Bank Sta=453.6,468.6
XS Rating Curve= 0 ,0
Exp/Cntr=0.3,0.1

Type RM Length L Ch R = 1 ,59430.4 ,358.4,341.8,325.1
XS GIS Cut Line= 2
     2137333.386       411747.26     2137449.318      412940.736
#Sta/Elev= 30
       0  3150.2     131 3151.88   191.4 3151.88   221.7 3151.38   251.9 3150.29
   282.1 3148.82   302.3 3147.34   352.7 3143.05   372.8 3141.86     393    3141
   433.3 3139.88   483.7 3138.92   513.9 3137.29   544.1 3136.21   624.7  3135.1
   739.4 3131.63   745.6 3131.53   754.4 3131.59   775.9 3132.37   806.1 3133.98
   836.3    3136   846.4 3136.89   876.6 3139.96   957.3 3148.99  1068.1 3159.58
  1078.2 3161.04  1088.2 3163.04  1098.3  3165.4  1128.6  3173.1  1199.1 3191.72
#Mann= 3 , 0 , 0
       0      .1       0   739.4    .045       0   754.4      .1       0
Bank Sta=739.4,754.4
XS Rating Curve= 0 ,0
Exp/Cntr=0.3,0.1

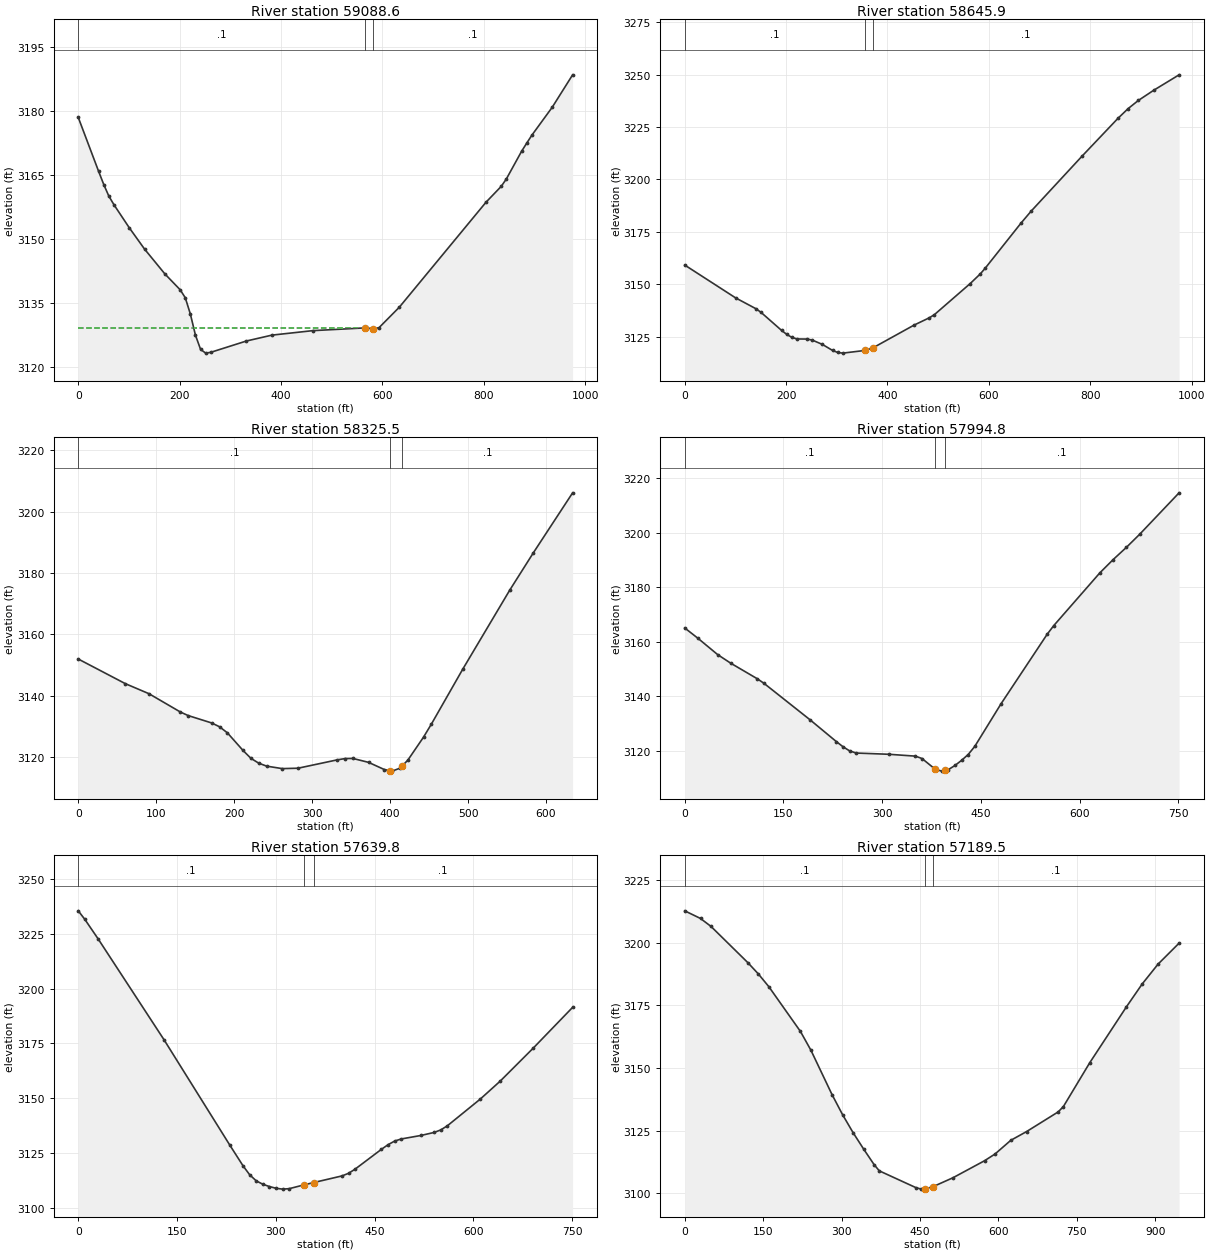
Type RM Length L Ch R = 1 ,59088.6 ,446.5,442.7,438.9
XS GIS Cut Line= 2
     2136691.347      412268.647     2137404.132      412934.274
#Sta/Elev= 30
       0 3178.54    40.2 3165.86    50.3 3162.78    60.3 3160.06    70.4 3158.03
   100.5 3152.64   130.7 3147.62   170.9 3141.77   201.1 3138.04   211.1 3136.18
   221.2 3132.33   231.2 3127.38   241.3 3124.05   251.4 3123.16   261.4 3123.35
   331.8 3126.01   382.1 3127.39   462.5 3128.44   565.8 3129.09   580.8 3128.92
   593.2 3129.12   633.4 3133.95   804.3  3158.6   834.5 3162.35   844.6 3164.09
   874.7  3170.6   884.8 3172.51   894.8 3174.35     935 3180.92   975.3 3188.55
#Mann= 3 , 0 , 0
       0      .1       0   565.8    .045       0   580.8      .1       0
#XS Ineff= 2 , 0
          550.93 3129.15
Permanent Ineff=
       F       F
Bank Sta=565.8,580.8
XS Rating Curve= 0 ,0
Exp/Cntr=0.3,0.1

Type RM Length L Ch R = 1 ,58645.9 ,306.5,320.4,334.2
XS GIS Cut Line= 2
     2136481.802      412726.362      2137285.95      413278.149
#Sta/Elev= 30
       0 3159.24   100.5 3143.58   140.8 3138.39   150.8 3136.64     191 3128.11
   201.1 3126.23   211.1 3124.81   221.2 3124.02   241.3 3123.97   251.4 3123.51
   271.5 3121.43   291.6 3118.56   301.6  3117.6   311.7 3117.27   355.7 3118.55
   370.7  3119.7   452.4 3130.62   482.6 3134.11   492.6 3135.61     563 3150.37
   583.1 3155.01   593.2 3157.85   663.6 3179.27   683.7 3184.99   784.2 3211.21
   854.6 3229.11   874.7 3233.76   894.8 3237.64     925 3242.48   975.3 3249.87
#Mann= 3 , 0 , 0
       0      .1       0   355.7    .045       0   370.7      .1       0
Bank Sta=355.7,370.7
XS Rating Curve= 0 ,0
Exp/Cntr=0.3,0.1

Type RM Length L Ch R = 1 ,58325.5 ,328.3,330.8,333.1
XS GIS Cut Line= 2
     2136473.128      412784.257     2136684.942      413382.019
#Sta/Elev= 30
       0 3151.99    60.4 3143.96    90.6  3140.7   130.9 3134.74   140.9 3133.57
   171.1 3131.16   181.2 3129.92   191.3 3127.94   211.4 3122.19   221.5 3119.63
   231.5 3118.06   241.6 3117.09   261.7 3116.28   281.9 3116.41   332.2 3119.13
   342.3 3119.55   352.3 3119.59   372.4 3118.32   392.6 3115.98   400.4 3115.58
   402.6 3115.46   412.7 3116.42   415.4 3117.12   422.8 3119.04   442.9 3126.52
     453 3130.78   493.2 3148.66   553.6 3174.46   583.8 3186.59   634.2 3206.14
#Mann= 3 , 0 , 0
       0      .1       0   400.4    .045       0   415.4      .1       0
Bank Sta=400.4,415.4
XS Rating Curve= 0 ,0
Exp/Cntr=0.3,0.1

Type RM Length L Ch R = 1 ,57994.8 ,366.6,354.9,343.2
XS GIS Cut Line= 2
     2136186.846      412786.302     2136364.851       413515.77
#Sta/Elev= 30
       0 3164.98      20  3161.2    50.1 3155.18    70.1 3152.01   110.1 3146.35
   120.1 3144.71   190.2  3131.3   230.3 3123.27   240.3  3121.4   250.3 3119.88
   260.3 3119.07   310.4 3118.61   350.4 3117.93   360.4 3117.06   380.3 3113.16
   390.4 3112.43   395.3  3112.7   400.5 3112.99   410.5 3114.51   420.5 3116.38
   430.5 3118.52   440.5 3121.48   480.6  3137.2   550.6 3162.69   560.6 3165.86
   630.7 3185.24   650.8 3190.08   670.8 3194.54   690.8  3199.3   750.9 3214.57
#Mann= 3 , 0 , 0
       0      .1       0   380.3    .045       0   395.3      .1       0
Bank Sta=380.3,395.3
XS Rating Curve= 0 ,0
Exp/Cntr=0.3,0.1

Type RM Length L Ch R = 1 ,57639.8 ,454.2,450.3,446.5
XS GIS Cut Line= 2
     2135710.735      413017.368      2136225.66      413563.868
#Sta/Elev= 30
       0 3235.48      10 3231.58      30 3222.76   130.2 3176.69   230.3 3128.53
   250.3 3119.13   260.3 3115.08   270.3 3112.28   280.3 3110.74   290.3 3109.68
   300.4 3108.89   310.4  3108.5   320.4 3108.71   342.6 3110.42   357.6  3111.5
   400.5 3114.52   410.5 3115.71   420.5 3117.62   460.5 3126.67   470.6 3128.78
   480.6 3130.43   490.6 3131.39   520.6 3132.99   540.6 3134.37   550.6 3135.51
   560.6 3137.39   610.7  3149.6   640.7 3157.72   690.8 3172.75   750.9 3191.44
#Mann= 3 , 0 , 0
       0      .1       0   342.6    .045       0   357.6      .1       0
Bank Sta=342.6,357.6
XS Rating Curve= 0 ,0
Exp/Cntr=0.3,0.1

Type RM Length L Ch R = 1 ,57189.5 ,479,494.7,510.4
XS GIS Cut Line= 2
     2135329.855      413341.349     2136079.137      413918.251
#Sta/Elev= 30
       0 3212.73    30.2 3209.68    50.3  3206.5   120.7 3192.06   140.8 3187.55
     161 3182.43   221.3 3164.61   241.4 3157.09   281.7 3139.42   301.8 3131.43
   321.9 3124.25     342 3117.73   362.2 3111.46   372.2 3108.96   442.6 3102.23
   452.7 3101.67   459.9 3101.72   474.9 3102.65   513.1 3106.21   573.4 3112.99
   593.5 3115.68   623.7 3121.15   653.9 3124.64   714.3 3132.48   724.3 3134.62
   774.6 3152.07     845 3174.46   875.2 3183.59   905.4 3191.46   945.6 3199.83
#Mann= 3 , 0 , 0
       0      .1       0   459.9    .045       0   474.9      .1       0
Bank Sta=459.9,474.9
XS Rating Curve= 0 ,0
Exp/Cntr=0.3,0.1

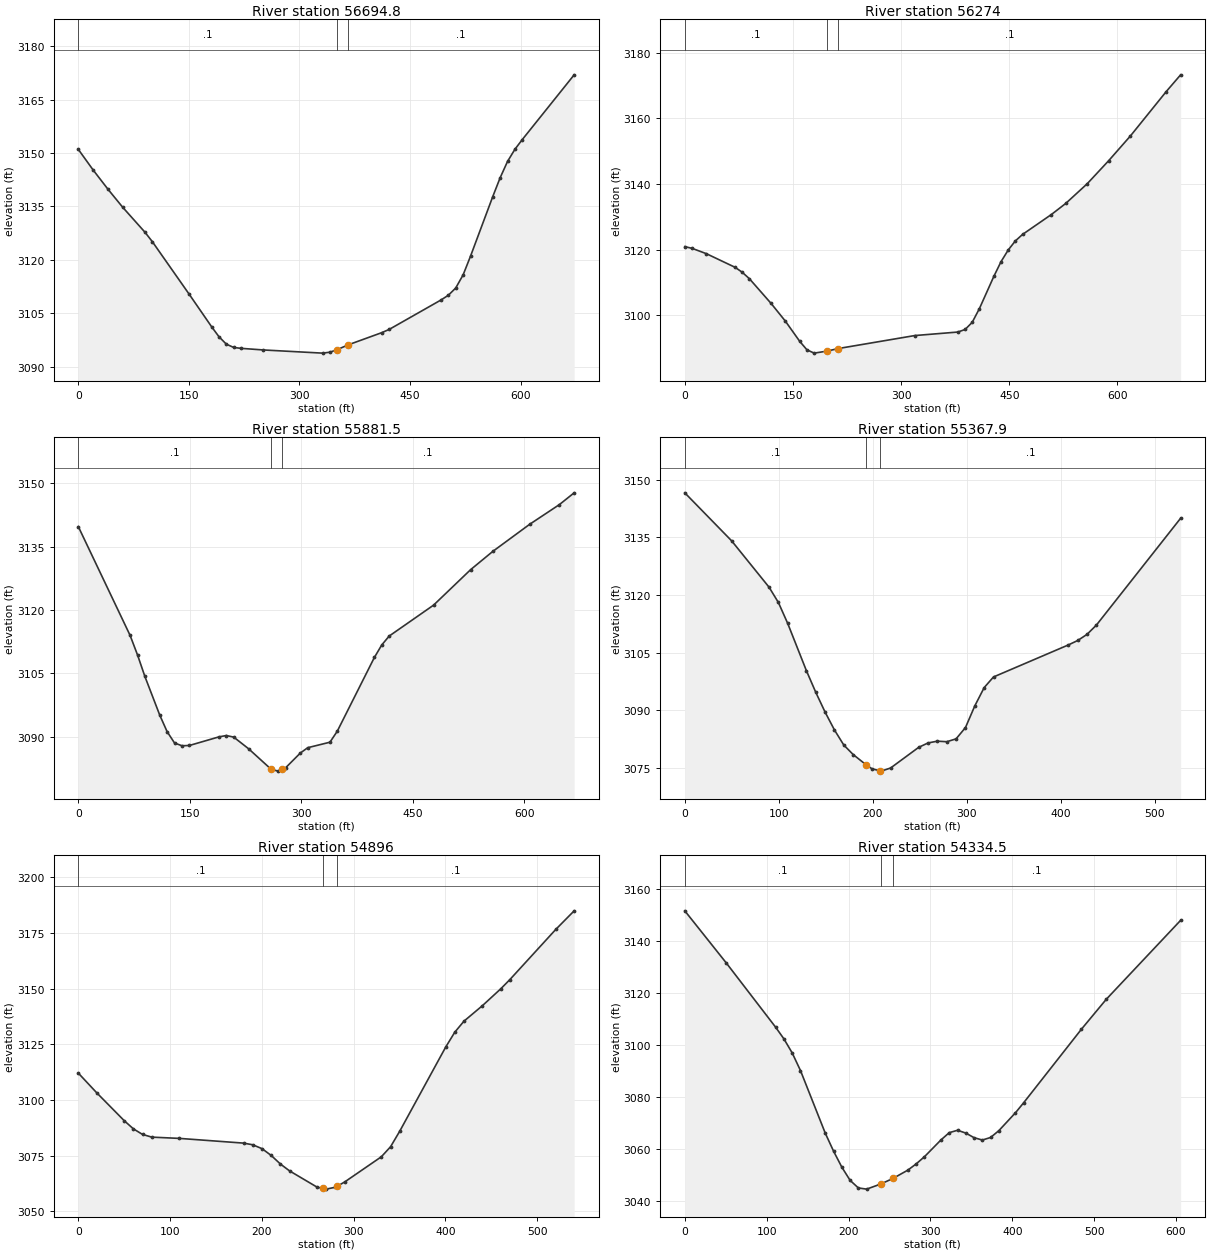
Type RM Length L Ch R = 1 ,56694.8 ,425.1,420.8,416.5
XS GIS Cut Line= 2
     2135280.143      413571.059     2135429.661      414226.924
#Sta/Elev= 30
       0 3151.02    20.1 3145.24    40.2 3139.85    60.2 3134.78    90.4 3127.78
   100.4 3125.13   150.6 3110.32   180.7 3101.29   190.8 3098.45   200.8 3096.37
   210.8 3095.44   220.9 3095.19     251 3094.74   331.3 3093.85   341.4 3094.11
   351.2 3094.83   366.2 3096.18   411.6 3099.59   421.7  3100.5     492 3108.76
     502 3110.09     512 3112.12   522.1 3115.83   532.1 3121.06   562.2 3137.74
   572.3 3143.07   582.3 3147.64   592.4 3151.08   602.4  3153.8   672.7 3171.95
#Mann= 3 , 0 , 0
       0      .1       0   351.2    .045       0   366.2      .1       0
Bank Sta=351.2,366.2
XS Rating Curve= 0 ,0
Exp/Cntr=0.3,0.1

Type RM Length L Ch R = 1 ,56274   ,394.9,392.5,390
XS GIS Cut Line= 2
      2134857.49      413738.341     2135157.751      414356.968
#Sta/Elev= 30
       0  3120.9      10 3120.39    29.9 3118.76    69.8  3114.6    79.7 3113.09
    89.7 3111.11   119.6 3103.63   139.5 3098.21   159.4 3092.06   169.4 3089.48
   179.4 3088.48   197.4  3089.1   212.4 3089.86   318.9 3093.83   378.7  3094.9
   388.7 3095.68   398.6 3097.86   408.6 3102.06   428.5 3111.81   438.5 3116.31
   448.5 3119.88   458.4 3122.64   468.4 3124.62   508.3 3130.67   528.2 3134.04
   558.1 3140.06     588 3147.11   617.9 3154.58   667.7 3168.13   687.6 3173.21
#Mann= 3 , 0 , 0
       0      .1       0   197.4    .045       0   212.4      .1       0
Bank Sta=197.4,212.4
XS Rating Curve= 0 ,0
Exp/Cntr=0.3,0.1

Type RM Length L Ch R = 1 ,55881.5 ,518.6,513.6,508.6
XS GIS Cut Line= 2
     2134515.277      413929.083     2134868.992       414495.07
#Sta/Elev= 30
       0  3139.7    69.7 3113.94    79.7 3109.31    89.6 3104.22   109.6 3095.07
   119.5 3091.16   129.5 3088.47   139.5 3087.82   149.4 3087.88   189.3 3089.92
   199.2 3090.24   209.2 3089.86   229.1 3087.12   259.6 3082.24     269 3081.81
   274.6 3082.24   278.9 3082.58   298.8 3086.09   308.8 3087.36   338.7 3088.66
   348.6 3091.28   398.5 3108.73   408.4 3111.68   418.4 3113.79   478.2 3121.12
     528 3129.51   557.8 3133.83   607.7 3140.28   647.5 3144.92   667.4 3147.71
#Mann= 3 , 0 , 0
       0      .1       0   259.6    .045       0   274.6      .1       0
Bank Sta=259.6,274.6
XS Rating Curve= 0 ,0
Exp/Cntr=0.3,0.1

Type RM Length L Ch R = 1 ,55367.9 ,463.6,471.9,480.2
XS GIS Cut Line= 2
     2134105.491      414307.323     2134475.073      414683.466
#Sta/Elev= 30
       0 3146.58    49.8 3134.08    89.6 3122.01    99.5 3118.04   109.4  3112.6
   129.3 3100.28   139.3 3094.63   149.2 3089.48   159.2 3084.81   169.1  3080.9
   179.1 3078.42   192.5 3075.82     199 3074.72   207.5  3074.2   208.9 3074.11
   218.9 3074.93   248.7  3080.3   258.7 3081.45   268.6 3081.91   278.6 3081.77
   288.5 3082.51   298.5 3085.46   308.4 3091.09   318.4 3095.87   328.3 3098.63
   407.9 3106.97   417.9 3108.13   427.8 3109.73   437.8 3112.16   527.3 3139.96
#Mann= 3 , 0 , 0
       0      .1       0   192.5    .045       0   207.5      .1       0
Bank Sta=192.5,207.5
XS Rating Curve= 0 ,0
Exp/Cntr=0.3,0.1

Type RM Length L Ch R = 1 ,54896   ,558.7,561.6,564.4
XS GIS Cut Line= 2
     2133834.473      414551.901      2134050.06      415047.443
#Sta/Elev= 30
       0 3112.09      20 3103.28      50 3090.75      60 3087.08      70 3084.57
    80.1 3083.36   110.1  3082.8   180.1 3080.68   190.1 3079.93   200.2 3078.19
   210.2 3075.15   220.2 3071.31   230.2 3068.22   260.2 3060.92   266.9 3060.33
   270.2 3060.03   280.2 3060.89   281.9 3061.28   290.2 3063.22   330.2 3074.53
   340.3 3079.05   350.3 3086.03   400.3 3123.71   410.3 3130.46   420.3  3135.4
   440.3 3142.32   460.4 3149.92   470.4 3154.09   520.4 3176.59   540.4 3184.92
#Mann= 3 , 0 , 0
       0      .1       0   266.9    .045       0   281.9      .1       0
Bank Sta=266.9,281.9
XS Rating Curve= 0 ,0
Exp/Cntr=0.3,0.1

Type RM Length L Ch R = 1 ,54334.5 ,424.3,424.3,424.3
XS GIS Cut Line= 2
     2133324.614      414660.624     2133498.462      415240.754
#Sta/Elev= 30
       0 3151.53    50.5 3131.58     111 3106.81   121.1 3102.33   131.2 3096.94
   141.3 3090.18   171.6 3066.12   181.7 3059.23   191.8 3053.09   201.9 3048.02
     212  3045.1   222.1 3044.65   239.2  3046.6   254.2 3048.74   272.5 3051.96
   282.6 3054.34   292.7 3057.09   312.9 3063.55     323 3066.34   333.1 3067.25
   343.2 3066.18   353.3 3064.41   363.4  3063.5   373.5 3064.49   383.6 3067.11
   403.8 3073.95   413.8 3077.79   484.5 3106.09   514.8 3117.56   605.6 3147.88
#Mann= 3 , 0 , 0
       0      .1       0   239.2    .045       0   254.2      .1       0
Bank Sta=239.2,254.2
XS Rating Curve= 0 ,0
Exp/Cntr=0.3,0.1

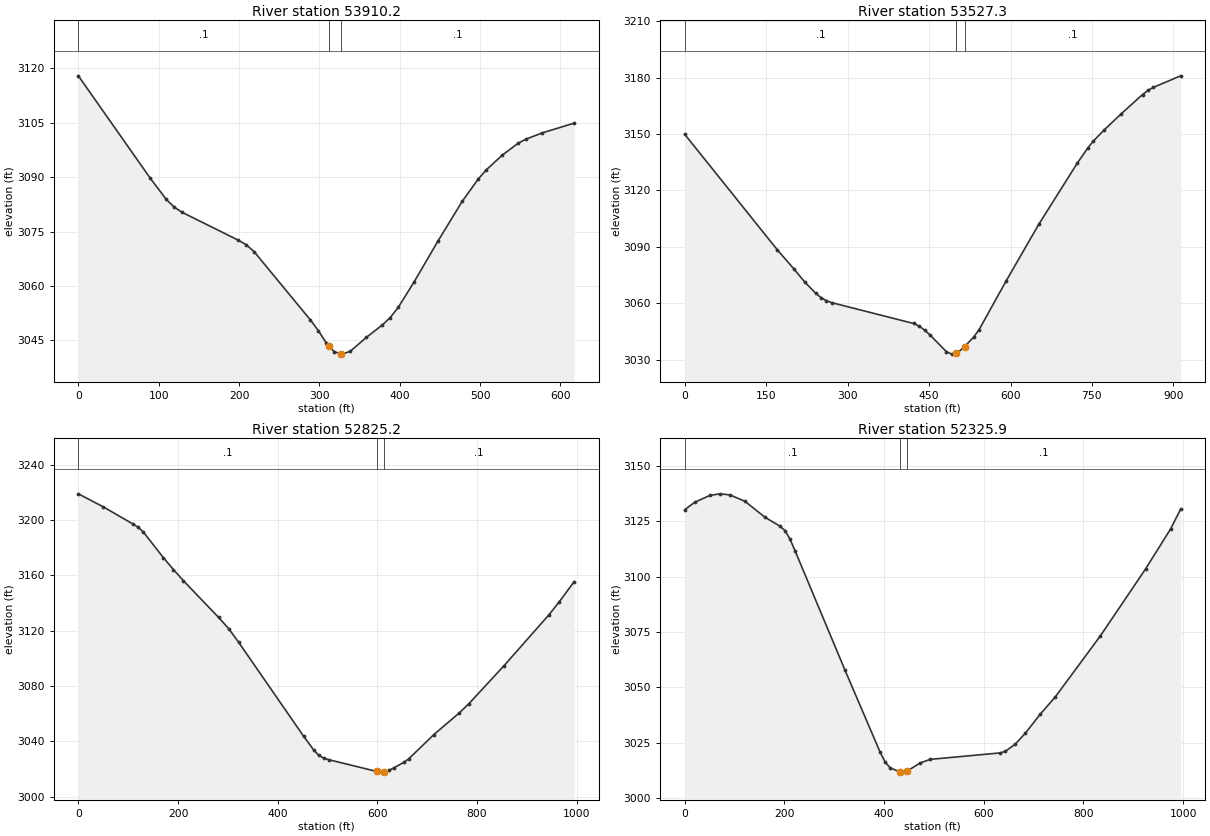
Type RM Length L Ch R = 1 ,53910.2 ,369.6,382.9,396.2
XS GIS Cut Line= 2
      2132911.25      414749.576     2133088.363      415340.604
#Sta/Elev= 30
       0 3117.95    89.6 3089.68   109.5 3083.85   119.4 3081.72   129.4 3080.28
     199 3072.62     209 3071.36   218.9 3069.42   288.6 3050.67   298.6  3047.7
   308.5 3044.28   312.2 3043.37   318.4 3041.85   327.2 3041.27   328.4 3041.19
   338.4 3041.98   358.3 3045.78   378.2 3049.21   388.1 3051.27   398.1 3054.08
     418 3061.17   447.8 3072.48   477.7 3083.33   497.6 3089.47   507.5 3091.98
   527.4 3096.04   547.3 3099.37   557.3 3100.51   577.2  3102.2     617  3104.9
#Mann= 3 , 0 , 0
       0      .1       0   312.2    .045       0   327.2      .1       0
Bank Sta=312.2,327.2
XS Rating Curve= 0 ,0
Exp/Cntr=0.3,0.1

Type RM Length L Ch R = 1 ,53527.3 ,690.4,702,713.7
XS GIS Cut Line= 2
     2132780.129      414616.551      2132522.15      415492.793
#Sta/Elev= 30
       0 3149.79   170.6 3088.31   200.8 3078.28   220.8 3071.28   240.9 3065.34
   250.9 3062.95     261 3061.28     271 3060.23   421.6 3049.16   431.6 3047.79
   441.7 3045.66   451.7 3043.07   481.8  3034.2   491.8 3032.86   500.3 3033.37
   501.9 3033.47   515.3  3036.8     532 3041.89     542 3045.81   592.2 3071.94
   652.4 3102.09   722.7 3134.34   742.8 3142.75   752.8 3146.33   772.9 3152.26
     803  3160.5   843.2 3171.02   853.2 3173.17   863.2 3174.82   913.4 3180.97
#Mann= 3 , 0 , 0
       0      .1       0   500.3    .045       0   515.3      .1       0
Bank Sta=500.3,515.3
XS Rating Curve= 0 ,0
Exp/Cntr=0.3,0.1

Type RM Length L Ch R = 1 ,52825.2 ,521.2,499.4,482.2
XS GIS Cut Line= 2
     2132559.972      414213.853     2131861.475      414922.319
#Sta/Elev= 30
       0 3219.04    50.2 3209.58   110.5 3197.01   120.6  3194.7   130.6 3191.35
   170.8 3172.78   190.9 3164.21     211 3156.12   281.4 3129.64   301.5 3121.59
   321.6 3111.67   452.2 3043.56   472.3 3033.69   482.4  3029.8   492.4 3027.82
   502.5 3026.67   598.9 3018.15     613 3017.67   613.9 3017.77   623.1 3018.86
   633.1  3020.8   653.2 3024.74   663.3 3027.39   713.5 3044.88   763.8 3060.32
   783.9 3067.26   854.2 3094.68   944.6 3131.63   964.8  3140.8   994.9  3155.5
#Mann= 3 , 0 , 0
       0      .1       0   598.9    .045       0   613.9      .1       0
Bank Sta=598.9,613.9
XS Rating Curve= 0 ,0
Exp/Cntr=0.3,0.1

Type RM Length L Ch R = 1 ,52325.9 ,530.7,534.8,539
XS GIS Cut Line= 2
     2131841.966      413852.268     2131788.635      414845.735
#Sta/Elev= 30
       0 3130.32    20.1 3133.66    50.2 3136.73    70.4 3137.46    90.4 3136.98
   120.6  3134.1   160.8  3126.9   190.9 3122.86     201 3120.87     211 3117.05
   221.1  3111.8   321.6 3057.74   391.9 3020.79     402 3016.34     412 3013.72
   431.5 3011.85   442.2 3011.76   446.5  3012.3   472.3 3015.89   492.4 3017.52
   633.1 3020.45   643.2 3021.18   663.3 3024.43   683.4 3029.36   713.5    3038
   743.7 3045.81   834.1 3073.38   924.6 3103.55   974.8 3121.61   994.9 3130.56
#Mann= 3 , 0 , 0
       0      .1       0   431.5    .045       0   446.5      .1       0
Bank Sta=431.5,446.5
XS Rating Curve= 0 ,0
Exp/Cntr=0.3,0.1