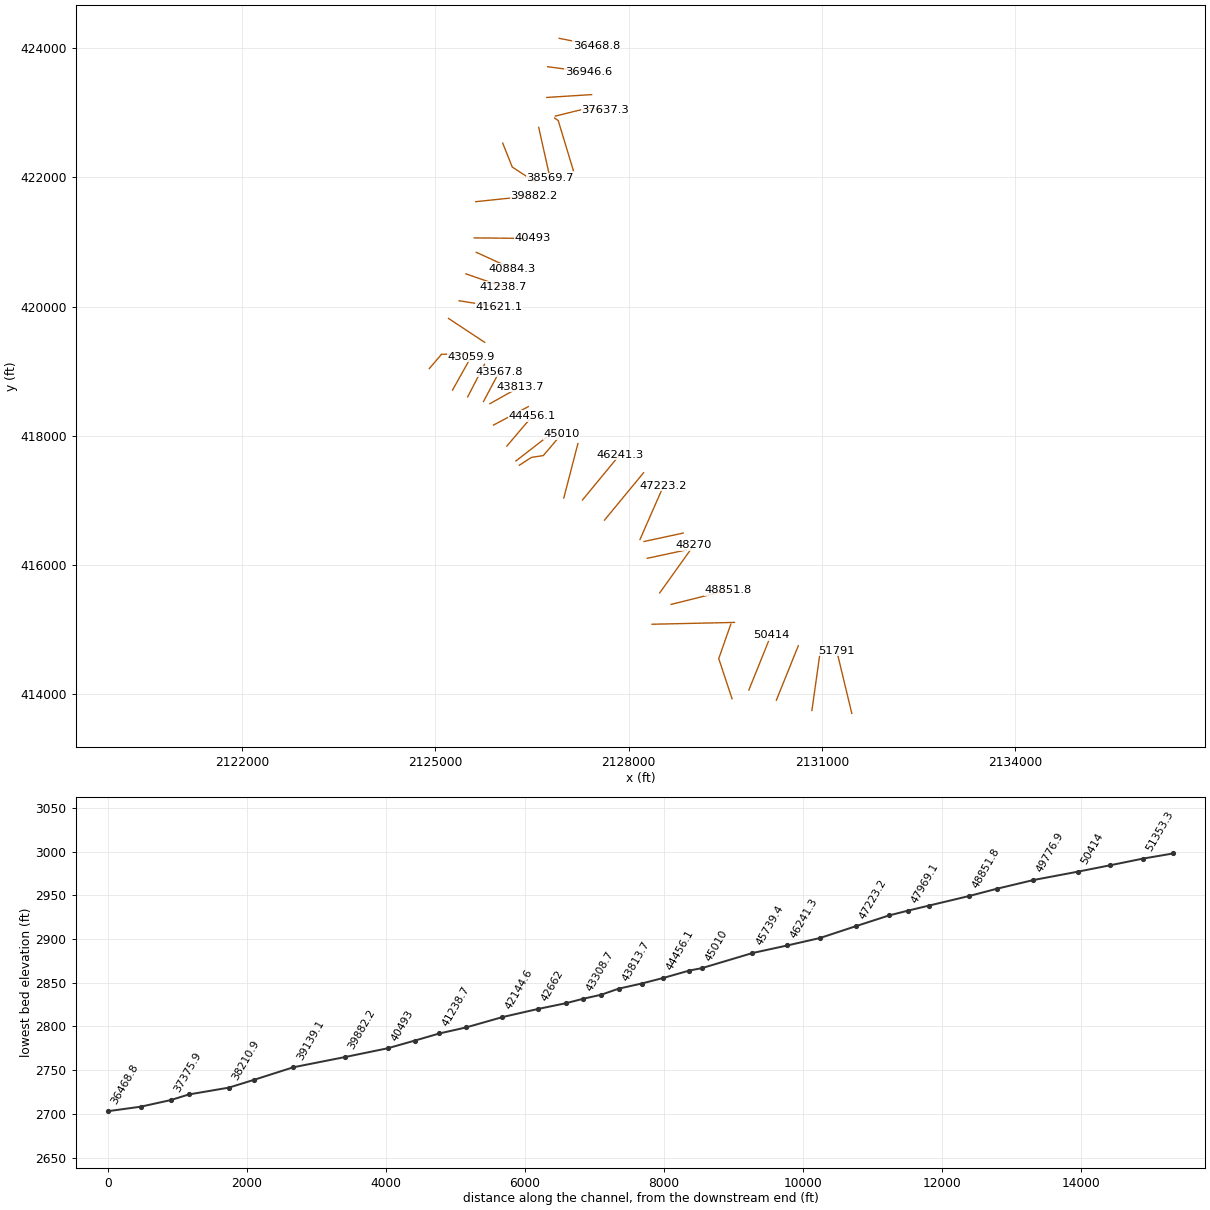
HEC-RAS study SFrkChryRv.prj: SFrkChryRv

--- SFrkChryRv.g01 (geometry) --- (continued)

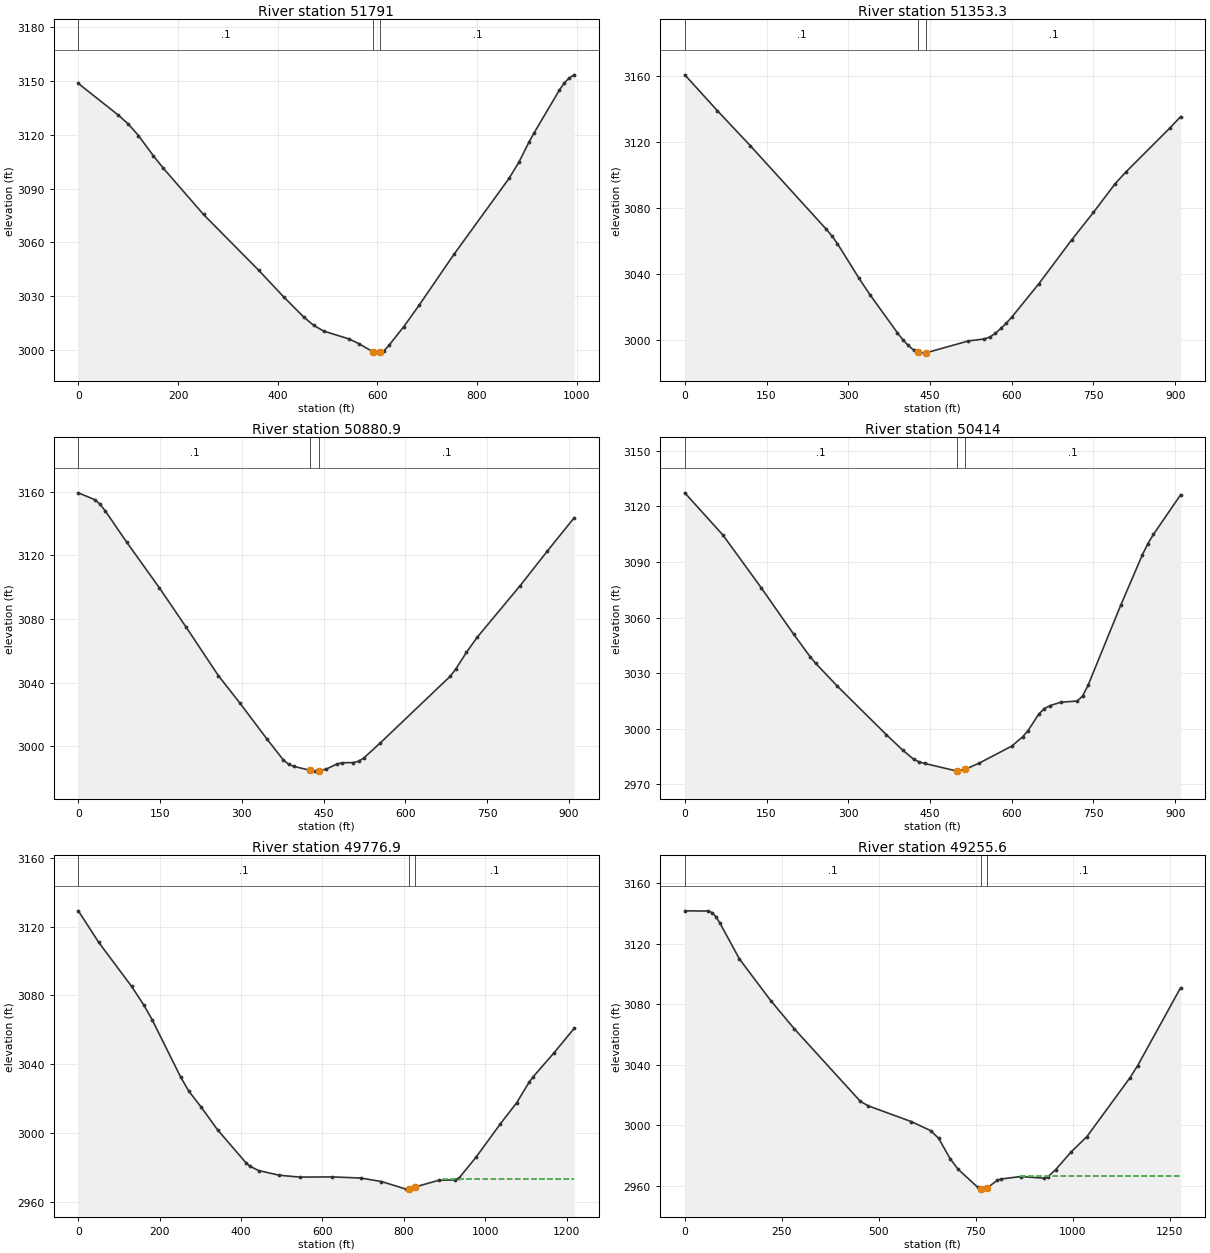
Type RM Length L Ch R = 1 ,51791   ,445.3,437.7,466.7
XS GIS Cut Line= 2
     2131461.356      413703.223     2131228.069      414670.383
#Sta/Elev= 30
       0 3148.71    80.4 3131.01   100.5    3126   120.6 3119.61   150.7 3108.27
   170.8 3101.28   251.2 3075.52   361.8 3044.39     412  3029.5   452.2 3018.26
   472.3 3013.57   492.4 3010.37   542.7 3006.02   562.8 3003.38     591 2998.83
     603 2998.06     606 2998.42     613 2999.25   623.1 3002.34   653.2 3012.92
   683.4 3024.68   753.7 3053.24   864.2 3095.66   884.4 3104.92   904.4 3116.06
   914.5 3121.07   964.8 3144.81   974.8 3148.88   984.8 3151.75   994.9 3153.54
#Mann= 3 , 0 , 0
       0      .1       0     591    .045       0     606      .1       0
Bank Sta=591,606
XS Rating Curve= 0 ,0
Exp/Cntr=0.3,0.1

Type RM Length L Ch R = 1 ,51353.3 ,478,472.5,467
XS GIS Cut Line= 2
     2130842.617      413747.388     2130969.638      414648.479
#Sta/Elev= 30
       0 3160.67      60 3138.87     120 3117.83     260 3067.05     270 3063.08
     280 3058.51     320 3037.32     340 3027.44     390 3004.55     400 3000.32
     410 2996.79     420 2993.99   427.7 2992.75     430 2992.38     440 2992.12
   442.7  2992.3     520 2999.46     550 3000.74     560 3001.87     570 3004.13
     580 3007.06     590 3010.23     600 3013.87     650 3034.25     710 3060.69
     750 3077.37     790  3094.8     810 3101.98     890 3128.39     910 3135.31
#Mann= 3 , 0 , 0
       0      .1       0   427.7    .045       0   442.7      .1       0
Bank Sta=427.7,442.7
XS Rating Curve= 0 ,0
Exp/Cntr=0.3,0.1

Type RM Length L Ch R = 1 ,50880.9 ,467,466.9,466.7
XS GIS Cut Line= 3
     2130290.964      413906.757     2130461.344      414328.652
     2130631.725      414750.547
#Sta/Elev= 30
       0 3159.38    29.7 3155.13    39.6 3152.36    49.5    3148      89 3128.25
   148.4 3099.84   197.8    3075   257.2  3044.4   296.7 3027.17   346.2 3004.64
   375.9 2991.66   385.8 2988.83   395.6 2987.45     426 2984.94   435.2 2984.47
     441  2984.6     455 2985.76   474.8 2988.96   484.7 2989.74   504.5 2989.84
   514.4 2990.65   524.2  2992.8   553.9 3002.09   682.5 3044.09   692.4 3048.46
   712.2 3059.07     732 3068.58   811.1 3101.12   860.5 3122.66     910 3143.69
#Mann= 3 , 0 , 0
       0      .1       0     426    .045       0     441      .1       0
Bank Sta=426,441
XS Rating Curve= 0 ,0
Exp/Cntr=0.3,0.1

Type RM Length L Ch R = 1 ,50414   ,636,637,638
XS GIS Cut Line= 2
     2129865.018      414065.732      2130205.78      414909.522
#Sta/Elev= 30
       0 3127.28      70  3104.5     140 3076.16     200 3050.93     230 3038.86
     240 3035.35     280 3022.96     370 2996.76     400 2988.43     420 2983.54
     430 2982.11     440 2981.28     500 2977.12     515 2978.16     540  2981.4
     600 2990.61     620 2995.62     630 2999.02     650 3008.03     660 3010.91
     670 3012.42     690 3014.31     720 3014.94     730 3017.61     740 3023.34
     800 3066.58     840 3093.97     850 3099.92     860  3104.8     910 3126.23
#Mann= 3 , 0 , 0
       0      .1       0     500    .045       0     515      .1       0
Bank Sta=500,515
XS Rating Curve= 0 ,0
Exp/Cntr=0.3,0.1

Type RM Length L Ch R = 1 ,49776.9 ,549.3,521.3,493.6
XS GIS Cut Line= 3
     2129603.452      413930.728     2129397.484      414551.937
     2129584.602      415084.357
#Sta/Elev= 30
       0  3129.1    50.3 3110.73   130.9 3085.27   161.1 3074.37   181.2 3065.99
   251.7 3032.54   271.8 3024.35   302.1 3015.12   342.3 3001.99   412.8 2982.66
   422.9 2980.72     443 2978.36   493.4 2975.65   543.7 2974.54   624.3 2974.66
   694.8 2973.99   745.2 2971.96   805.6 2967.56   813.6 2967.77   828.6 2968.87
   886.2 2972.71   926.6 2972.88   936.6 2974.23     977 2985.92  1037.4 3005.45
  1077.7 3017.76    1108 3029.61    1118 3032.77  1168.4 3046.43  1218.8 3060.84
#Mann= 3 , 0 , 0
       0      .1       0   813.6    .045       0   828.6      .1       0
#XS Ineff= 2 , 0
                          895.31         2973.26
Permanent Ineff=
       F       F
Bank Sta=813.6,828.6
XS Rating Curve= 0 ,0
Exp/Cntr=0.3,0.1

Type RM Length L Ch R = 1 ,49255.6 ,398.3,403.8,409.1
XS GIS Cut Line= 2
     2128363.012      415083.096      2129641.22      415111.442
#Sta/Elev= 30
       0 3141.69    60.4 3141.54    70.5 3140.55    80.5 3137.73    90.6 3133.59
   140.9 3109.85   221.5 3082.38   281.9 3063.81     453 3015.62   473.2 3012.72
   583.9 3002.34   634.2 2996.31   654.4 2991.31   684.6 2977.61   704.7 2970.82
     755 2958.97   764.8 2957.71   765.1 2957.67   779.8 2958.51   805.4 2963.43
   815.4 2964.34   865.8    2966   926.2  2964.9   936.2 2965.88   956.4  2970.6
   996.6 2982.38  1036.9 2992.42  1147.6 3031.21  1167.8 3039.37  1278.5 3090.88
#Mann= 3 , 0 , 0
       0      .1       0   764.8    .045       0   779.8      .1       0
#XS Ineff= 2 , 0
                          866.78         2966.05
Permanent Ineff=
       F       F
Bank Sta=764.8,779.8
XS Rating Curve= 0 ,0
Exp/Cntr=0.3,0.1

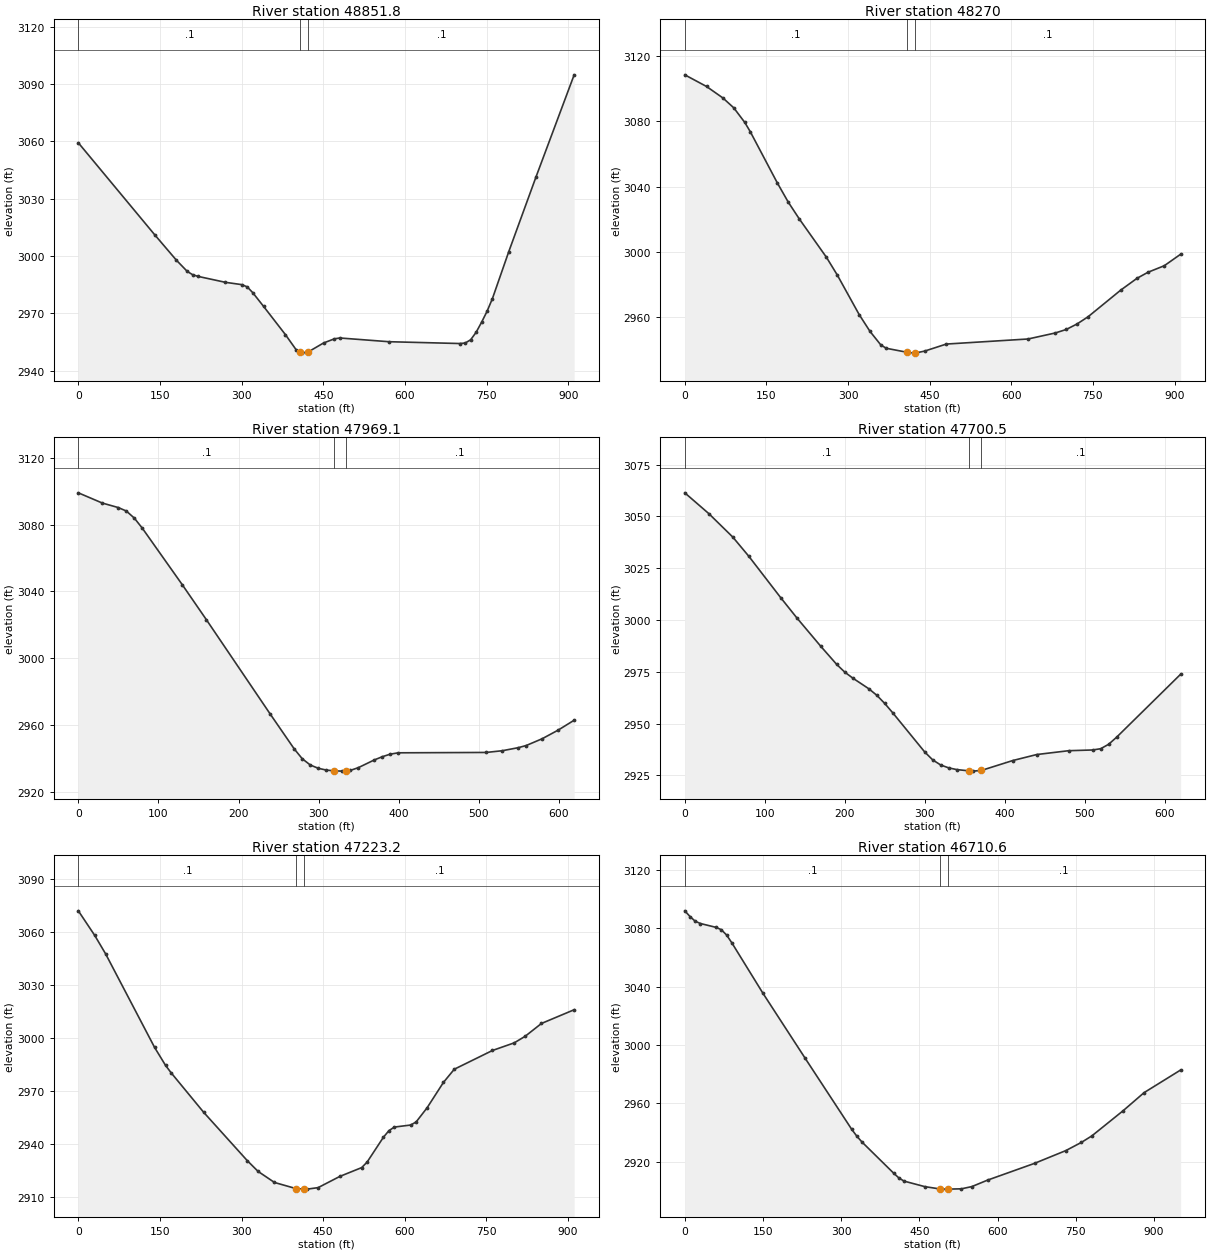
Type RM Length L Ch R = 1 ,48851.8 ,566.1,581.8,596.7
XS GIS Cut Line= 2
     2128658.534      415390.235     2129542.579      415610.014
#Sta/Elev= 30
       0 3059.23   140.2 3011.18   180.2 2997.84   200.2 2991.96   210.2 2990.23
   220.2 2989.36   270.3 2986.27   300.3 2985.07   310.3  2983.9   320.3 2980.92
   340.4 2973.68   380.4 2958.96   400.4 2950.93   407.8 2949.69   410.4 2949.25
   422.8 2949.95   450.5 2954.55   470.5 2956.73   480.5 2957.17   570.6 2955.22
   700.7 2954.27   710.8 2954.52   720.8 2956.23   730.8 2960.11   740.8 2965.34
   750.8 2971.02   760.8 2977.75   790.8 3002.27   840.9 3041.38     911 3094.77
#Mann= 3 , 0 , 0
       0      .1       0   407.8    .045       0   422.8      .1       0
#XS Ineff= 2 , 0
                          480.96         2957.06
Permanent Ineff=
       F       F
Bank Sta=407.8,422.8
XS Rating Curve= 0 ,0
Exp/Cntr=0.3,0.1

Type RM Length L Ch R = 1 ,48270   ,317.5,300.9,285.2
XS GIS Cut Line= 2
     2128481.388      415567.936     2129011.891      416308.794
#Sta/Elev= 30
       0  3108.3      40 3101.17    70.1 3094.14    90.1 3088.09   110.2 3079.22
   120.2 3073.63   170.2 3042.14   190.2 3030.47   210.3 3020.29   260.4 2996.74
   280.4 2985.86   320.4 2961.81   340.4 2951.48   360.5 2943.12   370.5 2941.17
   408.9 2938.71   420.6 2938.22   423.9 2938.31   440.6 2939.44   480.6 2943.76
   630.8 2946.86   680.9 2950.54   700.9 2952.66     721 2956.07     741 2960.41
   801.1 2976.72   831.1 2983.96   851.1 2987.62   881.2 2991.64   911.2 2998.66
#Mann= 3 , 0 , 0
       0      .1       0   408.9    .045       0   423.9      .1       0
Bank Sta=408.9,423.9
XS Rating Curve= 0 ,0
Exp/Cntr=0.3,0.1

Type RM Length L Ch R = 1 ,47969.1 ,287.2,268.6,287.6
XS GIS Cut Line= 2
     2128288.759      416103.956     2128894.093      416233.782
#Sta/Elev= 30
       0 3098.97      30 3092.84    49.9 3090.15    59.9 3088.09    69.9 3083.85
    79.9  3077.8   129.8 3043.98   159.8 3023.11   239.6 2966.58   269.6 2945.71
   279.6 2939.84   289.6  2936.1   299.6 2934.13   309.6 2933.06   319.6 2932.59
   329.5 2932.43   334.6 2932.64   339.5 2932.85   349.5 2934.48   369.5 2939.12
   379.4 2941.03   389.4 2942.58   399.4 2943.39   509.3 2943.61   529.2 2944.63
   549.2 2946.45   559.2 2947.75   579.2 2951.82   599.1 2956.97   619.1  2962.9
#Mann= 3 , 0 , 0
       0      .1       0   319.6    .045       0   334.6      .1       0
Bank Sta=319.6,334.6
XS Rating Curve= 0 ,0
Exp/Cntr=0.3,0.1

Type RM Length L Ch R = 1 ,47700.5 ,455.5,477.3,499.1
XS GIS Cut Line= 2
     2128238.984       416364.32     2128844.848       416494.26
#Sta/Elev= 30
       0 3061.37      30 3051.34      60    3040      80 3030.74   119.9 3010.73
   139.9 3001.06   169.9 2987.29   189.9  2978.5   199.9 2974.82   209.9 2971.93
   229.9  2966.8   239.9 2963.65   249.9 2959.67   259.8  2955.2   299.8 2936.27
   309.8 2932.44   319.8 2929.98   329.8 2928.59   339.8 2927.77   355.6 2927.13
   359.8 2927.02   370.6 2927.35   409.8 2932.13   439.8 2935.03   479.7 2936.88
   509.7 2937.23   519.7 2937.84   529.7 2939.99   539.7 2943.43   619.6 2973.79
#Mann= 3 , 0 , 0
       0      .1       0   355.6    .045       0   370.6      .1       0
Bank Sta=355.6,370.6
XS Rating Curve= 0 ,0
Exp/Cntr=0.3,0.1

Type RM Length L Ch R = 1 ,47223.2 ,519.6,512.6,505.6
XS GIS Cut Line= 2
     2128175.556      416394.972     2128542.158      417229.182
#Sta/Elev= 30
       0 3071.97      30 3058.14    50.1 3047.68   140.2 2994.76   160.2 2984.67
   170.2 2980.58   230.3 2958.14   310.4 2930.83   330.4 2924.71   360.5 2918.47
   400.6 2914.96   415.6 2914.73   420.6 2914.71   440.6 2915.55   480.6  2921.9
   520.7 2926.87   530.7 2929.99   560.7 2944.04   570.8 2947.76   580.8 2949.78
   610.8 2950.93   620.8 2952.68   640.8 2960.61   670.9 2974.99   690.9 2982.46
     761 2993.05   801.1 2997.37   821.1 3001.06   851.1 3008.32   911.2 3016.08
#Mann= 3 , 0 , 0
       0      .1       0   400.6    .045       0   415.6      .1       0
Bank Sta=400.6,415.6
XS Rating Curve= 0 ,0
Exp/Cntr=0.3,0.1

Type RM Length L Ch R = 1 ,46710.6 ,469.2,469.3,469.4
XS GIS Cut Line= 2
      2127625.18       416695.19     2128231.127       417428.59
#Sta/Elev= 30
       0 3091.94      10 3088.04      20 3084.79      30 3083.24    60.1  3080.6
    70.1 3078.99    80.1 3075.41    90.1  3070.1   150.2  3035.3   230.3 2991.26
   320.4 2942.13   330.5 2937.33   340.5 2933.32   400.6 2912.21   410.6 2908.94
   420.6 2906.74   460.6 2902.94   489.6 2901.36   500.7 2901.24   504.6 2901.24
   530.8 2901.45   550.8 2902.99   580.8  2907.4     671  2918.9     731 2927.64
   761.1 2933.29   781.1 2937.75   841.2 2955.03   881.2 2967.36   951.3 2982.87
#Mann= 3 , 0 , 0
       0      .1       0   489.6    .045       0   504.6      .1       0
Bank Sta=489.6,504.6
XS Rating Curve= 0 ,0
Exp/Cntr=0.3,0.1

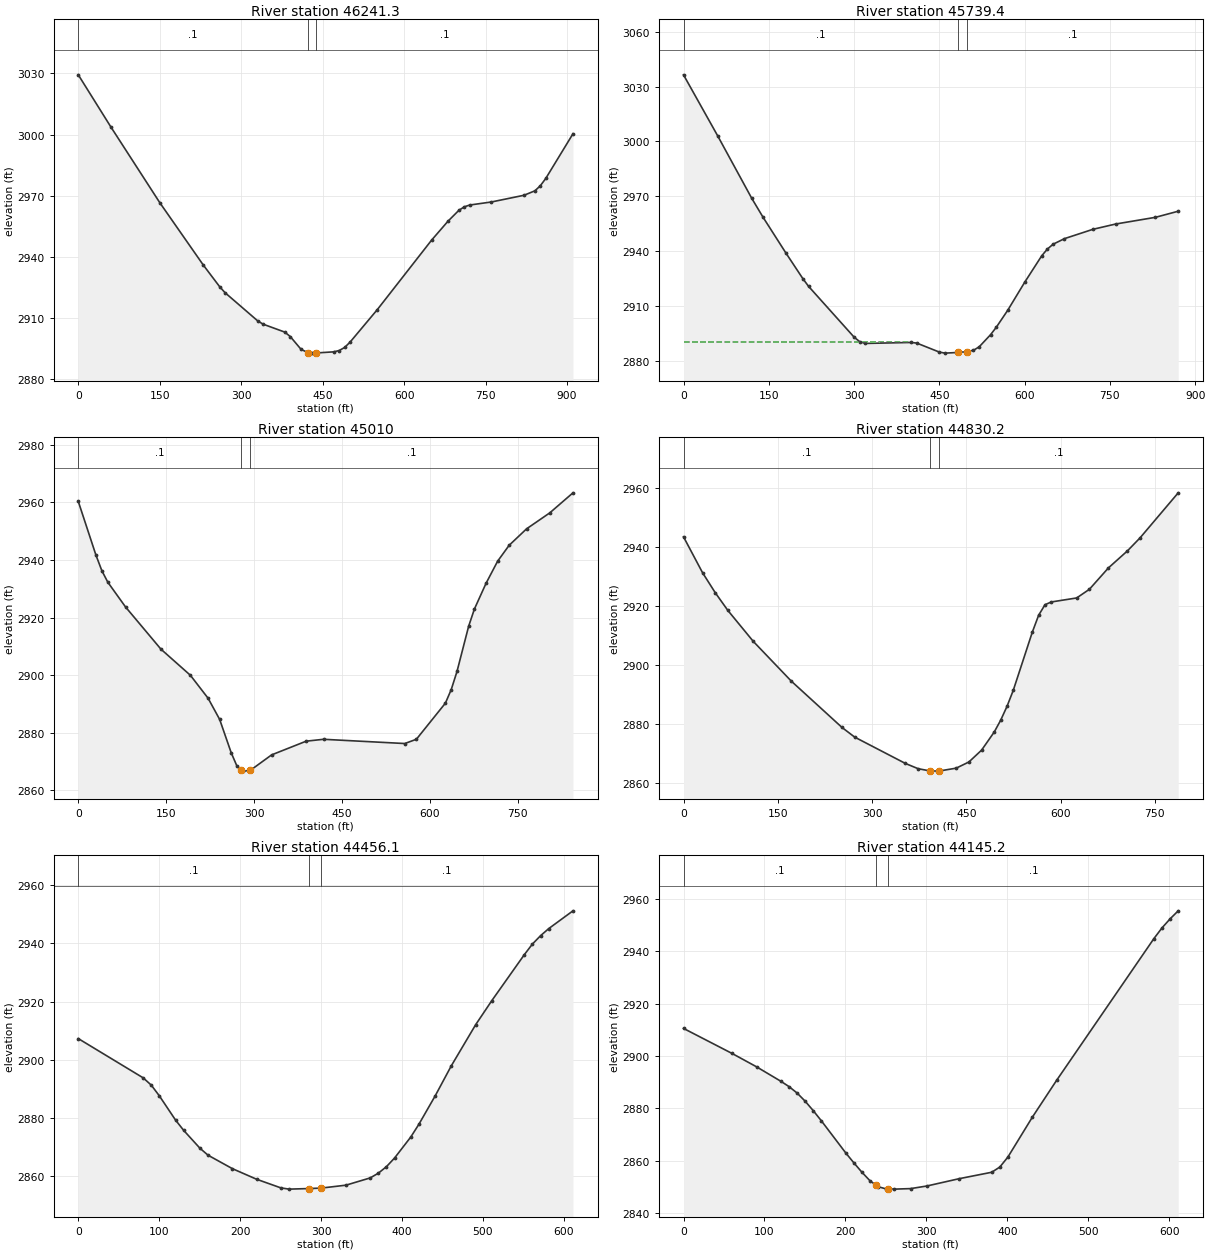
Type RM Length L Ch R = 1 ,46241.3 ,491.9,501.9,511.9
XS GIS Cut Line= 2
     2127283.863      417007.349     2127863.955      417709.462
#Sta/Elev= 30
       0 3029.33      60 3003.75   150.1 2966.57   230.2 2935.95   260.2 2925.36
   270.2  2922.4   330.3 2908.57   340.3 2906.94   380.3 2903.04   390.3 2900.86
   410.3 2894.55     423 2892.98   430.4 2892.73     438 2892.81   470.4 2893.36
   480.4 2894.01   490.4 2895.51   500.4 2898.13   550.5 2914.07   650.5 2948.19
   680.6 2957.46   700.6 2962.79   710.6 2964.53   720.6 2965.42   760.6 2966.92
   820.7 2970.22   840.7  2972.4   850.7 2974.89   860.7 2978.48   910.8 3000.41
#Mann= 3 , 0 , 0
       0      .1       0     423    .045       0     438      .1       0
Bank Sta=423,438
XS Rating Curve= 0 ,0
Exp/Cntr=0.3,0.1

Type RM Length L Ch R = 1 ,45739.4 ,757.1,729.4,701.5
XS GIS Cut Line= 2
     2126993.706      417037.129     2127212.453      417879.351
#Sta/Elev= 30
       0 3036.43      60 3003.08     120 2968.83     140  2958.4     180 2938.92
     210  2924.8     220  2920.6   300.1 2892.79   310.1 2890.28   320.1 2889.35
   400.1 2889.88   410.1 2889.56   450.1  2884.6   460.1 2884.04   483.1 2884.41
   498.1 2884.84   510.1  2885.6   520.1 2887.49   540.1 2894.12   550.1 2898.16
   570.1  2907.4   600.1 2922.82   630.1 2937.33   640.1 2941.03   650.1 2943.67
   670.1 2946.73   720.1 2951.83   760.1 2954.73   830.2 2958.41   870.2 2961.74
#Mann= 3 , 0 , 0
       0      .1       0   483.1    .045       0   498.1      .1       0
#XS Ineff= 2 , 0
          398.58 2889.89
Permanent Ineff=
       F       F
Bank Sta=483.1,498.1
XS Rating Curve= 0 ,0
Exp/Cntr=0.3,0.1

Type RM Length L Ch R = 1 ,45010   ,165.2,179.8,191.7
XS GIS Cut Line= 4
     2126305.163      417545.176     2126490.738      417666.179
     2126675.781      417693.835     2126957.876      418025.599
#Sta/Elev= 30
       0 2960.35    30.2 2941.67    40.3 2936.26    50.4  2932.3    80.6 2923.72
     141 2909.07   191.3 2899.99   221.5 2892.02   241.2 2884.69   260.9 2873.12
   270.8 2868.43   278.3 2867.13   280.6 2866.72   293.3 2866.95   329.9 2872.36
   388.9 2877.12   418.5 2877.77   557.1  2876.3   576.9 2877.78   626.4 2890.32
   636.3 2894.99   646.2 2901.31     666 2916.96   675.9 2922.99   695.7 2931.89
   715.5 2939.59   735.2 2945.12   764.9 2950.83   804.5 2956.37   844.1 2963.33
#Mann= 3 , 0 , 0
       0      .1       0   278.3    .045       0   293.3      .1       0
Bank Sta=278.3,293.3
XS Rating Curve= 0 ,0
Exp/Cntr=0.3,0.1

Type RM Length L Ch R = 1 ,44830.2 ,375.3,374.1,375.6
XS GIS Cut Line= 2
     2126250.662      417610.606     2126873.127      418092.112
#Sta/Elev= 30
       0 2943.54    30.3 2931.35    50.4 2924.59    70.6 2918.53     111 2908.03
   171.5 2894.53   252.2 2878.79   272.4 2875.51   353.1 2866.57   373.3 2864.79
   391.5 2864.07   403.6 2863.97   406.5    2864   433.8 2864.98     454 2867.07
   474.2  2871.1   494.4 2877.28   504.5 2881.23   514.6 2885.94   524.6 2891.41
   554.9 2911.17     565 2916.93   575.1 2920.49   585.2 2921.42   625.5 2922.78
   645.7 2925.72     676 2932.99   706.2 2938.76   726.4 2943.21     787 2958.48
#Mann= 3 , 0 , 0
       0      .1       0   391.5    .045       0   406.5      .1       0
Bank Sta=391.5,406.5
XS Rating Curve= 0 ,0
Exp/Cntr=0.3,0.1

Type RM Length L Ch R = 1 ,44456.1 ,317.3,310.9,304.5
XS GIS Cut Line= 2
     2126110.416      417841.682     2126506.803      418306.959
#Sta/Elev= 30
       0 2907.25    80.2 2893.74    90.2 2891.24   100.2 2887.54   120.2 2879.22
   130.3 2875.66   150.3 2869.55   160.3 2867.15   190.4 2862.52   220.4 2858.87
   250.5 2855.89   260.5 2855.48   285.3 2855.68   300.3 2855.84   330.7 2856.84
   360.7 2859.34   370.8 2860.98   380.8 2863.22   390.8 2866.19   410.8  2873.4
   420.8 2877.77   440.9 2887.52   460.9  2897.9     491 2912.04     511 2920.33
   551.1 2936.11   561.1 2939.76   571.2 2942.64   581.2 2945.06   611.2 2951.18
#Mann= 3 , 0 , 0
       0      .1       0   285.3    .045       0   300.3      .1       0
Bank Sta=285.3,300.3
XS Rating Curve= 0 ,0
Exp/Cntr=0.3,0.1

Type RM Length L Ch R = 1 ,44145.2 ,330.9,331.5,332.1
XS GIS Cut Line= 2
     2125903.554      418167.035     2126444.061      418452.442
#Sta/Elev= 30
       0 2910.56    60.1 2900.97    90.2 2895.89   120.2 2890.37   130.3 2888.33
   140.3 2885.87   150.3 2882.74   160.3 2879.12   170.3 2875.25   200.4 2862.99
   210.4  2859.2   220.4  2855.6   230.5 2852.29   238.2 2850.57   240.5 2850.06
   250.5 2849.19   253.2 2849.18   260.5 2849.13   280.6 2849.33   300.6 2850.32
   340.7 2853.13   380.8 2855.58   390.8 2857.57   400.8  2861.4   430.9 2876.59
   460.9 2890.68   581.2  2944.9   591.2 2948.99   601.2 2952.44   611.2  2955.5
#Mann= 3 , 0 , 0
       0      .1       0   238.2    .045       0   253.2      .1       0
Bank Sta=238.2,253.2
XS Rating Curve= 0 ,0
Exp/Cntr=0.3,0.1

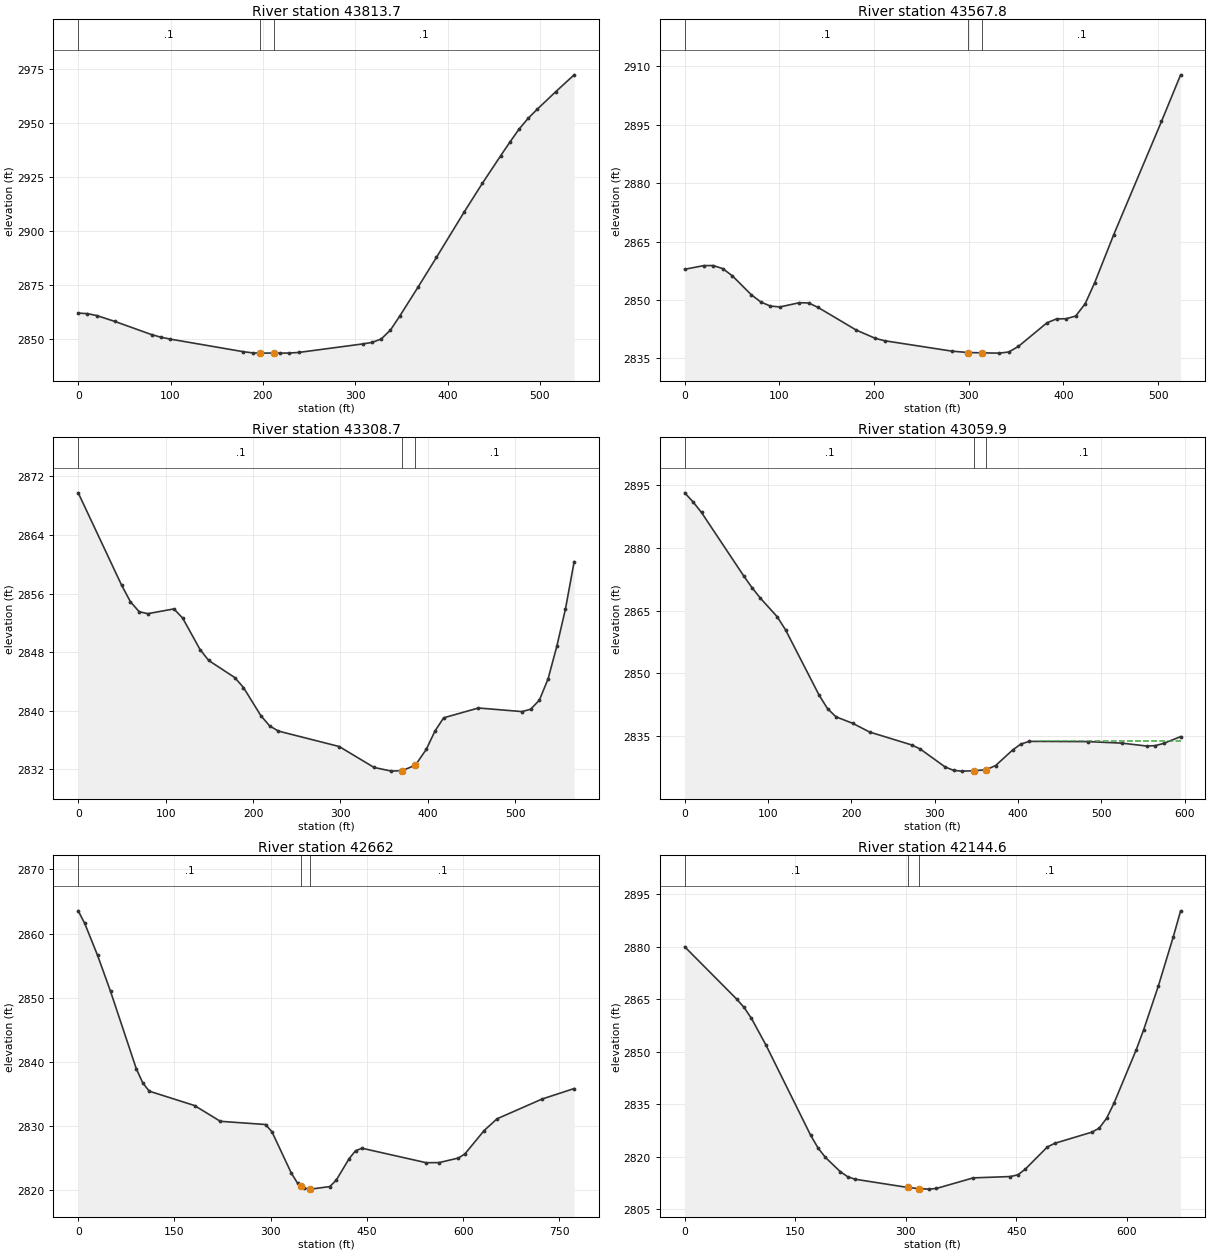
Type RM Length L Ch R = 1 ,43813.7 ,232.7,245.9,259.1
XS GIS Cut Line= 2
     2125847.455      418497.667     2126316.224      418759.786
#Sta/Elev= 30
       0 2861.81      10 2861.54    19.9 2860.68    39.8 2857.92    79.6  2851.8
    89.5 2850.63    99.5 2849.75     179 2843.88     189 2843.35   196.8 2843.26
   211.8 2843.24   218.8 2843.23   228.8 2843.28   238.7 2843.54   308.3 2847.51
   318.3 2848.21   328.2 2849.81   338.2 2853.96   348.1 2860.34     368 2873.82
   387.9  2887.6   417.7 2908.49   437.6 2921.94   457.5 2934.78   467.5 2941.11
   477.4 2947.14   487.4 2952.22   497.3 2956.45   517.2 2964.52   537.1 2972.33
#Mann= 3 , 0 , 0
       0      .1       0   196.8    .045       0   211.8      .1       0
Bank Sta=196.8,211.8
XS Rating Curve= 0 ,0
Exp/Cntr=0.3,0.1

Type RM Length L Ch R = 1 ,43567.8 ,259.1,259.1,259.2
XS GIS Cut Line= 2
     2125748.332      418532.099      2125995.07       418994.09
#Sta/Elev= 30
       0  2857.9    20.1 2858.84    30.2 2858.86    40.3 2858.06    50.4 2856.21
    70.5 2851.33    80.6 2849.47    90.6 2848.45   100.7 2848.23   120.9 2849.31
   130.9 2849.26     141 2848.09   181.3 2842.28   201.4 2840.16   211.5 2839.54
     282 2836.89   298.9 2836.53   313.9 2836.44   332.4 2836.37   342.4 2836.67
   352.5  2838.1   382.7 2844.17   392.8 2845.16   402.9  2845.2     413  2845.9
     423 2849.05   433.1 2854.49   453.2 2866.82   503.6 2895.87   523.8 2907.83
#Mann= 3 , 0 , 0
       0      .1       0   298.9    .045       0   313.9      .1       0
Bank Sta=298.9,313.9
XS Rating Curve= 0 ,0
Exp/Cntr=0.3,0.1

Type RM Length L Ch R = 1 ,43308.7 ,249.6,248.8,248
XS GIS Cut Line= 2
     2125502.894      418602.912      2125763.52      419106.944
#Sta/Elev= 30
       0 2869.76    49.8 2857.11    59.7  2854.9    69.7 2853.53    79.6 2853.26
   109.5 2853.91   119.5 2852.66   139.4 2848.36   149.3 2846.87   179.2 2844.53
   189.1 2843.17     209 2839.33     219 2837.94     229 2837.23   298.6 2835.12
   338.5 2832.26   358.4 2831.76   370.8 2831.83   385.8 2832.58   398.2 2834.73
   408.2 2837.24   418.1 2839.04   457.9 2840.38   507.7 2839.89   517.6 2840.21
   527.6 2841.45   537.6 2844.37   547.5 2848.78   557.5 2853.93   567.4 2860.36
#Mann= 3 , 0 , 0
       0      .1       0   370.8    .045       0   385.8      .1       0
Bank Sta=370.8,385.8
XS Rating Curve= 0 ,0
Exp/Cntr=0.3,0.1

Type RM Length L Ch R = 1 ,43059.9 ,422,397.9,373.8
XS GIS Cut Line= 2
      2125267.58      418707.868      2125558.17      419227.055
#Sta/Elev= 30
       0 2893.14    10.1 2890.97    20.2 2888.44    70.6 2873.36    80.7 2870.51
    90.8 2867.98   110.9 2863.56     121 2860.41   161.4 2844.76   171.4 2841.58
   181.5 2839.63   201.7 2838.06   221.9 2835.99   272.3 2832.91   282.4 2831.96
   312.6 2827.63   322.7 2826.83   332.8 2826.65   346.9 2826.73   361.9    2827
   373.1 2827.99   393.3 2831.67   403.4 2833.13   413.5 2833.76     484  2833.7
   524.4 2833.34   554.6 2832.64   564.7 2832.75   574.8 2833.28     595  2834.9
#Mann= 3 , 0 , 0
       0      .1       0   346.9    .045       0   361.9      .1       0
#XS Ineff= 2 , 0
                          424.09         2833.89
Permanent Ineff=
       F       F
Bank Sta=346.9,361.9
XS Rating Curve= 0 ,0
Exp/Cntr=0.3,0.1

Type RM Length L Ch R = 1 ,42662   ,530.7,517.4,504.2
XS GIS Cut Line= 3
     2124907.249      419041.077     2125097.057      419263.008
     2125578.015      419267.256
#Sta/Elev= 30
       0 2863.55    10.1  2861.6    30.2  2856.6    50.4 2850.98    90.6  2838.9
   100.7 2836.69   110.8 2835.42   181.3 2833.18   221.5 2830.72     292 2830.22
     302 2829.08   332.1 2822.65   342.1 2821.04     347 2820.65   352.2 2820.25
     362 2820.15   362.2 2820.14   392.2 2820.54   402.2 2821.54   422.3  2824.9
   432.3 2826.13   442.3 2826.52   542.5 2824.26   562.6 2824.28   592.6 2824.99
   602.7 2825.63   632.7 2829.28   652.8 2831.11   722.9 2834.19     773 2835.83
#Mann= 3 , 0 , 0
       0      .1       0     347    .045       0     362      .1       0
Bank Sta=347,362
XS Rating Curve= 0 ,0
Exp/Cntr=0.3,0.1

Type RM Length L Ch R = 1 ,42144.6 ,513.9,523.5,533.1
XS GIS Cut Line= 2
     2125205.536      419817.449     2125767.405      419447.386
#Sta/Elev= 30
       0 2880.05    70.3 2865.13    80.3 2862.76    90.4 2859.62   110.5 2851.84
   170.7 2826.21   180.8 2822.54   190.8 2819.82   210.9 2815.76   220.9  2814.3
     231 2813.56   302.7  2811.2   317.7 2810.87   331.4 2810.72   341.4 2810.91
   391.6 2813.94   441.8 2814.32   451.9  2814.8   461.9  2816.4     492 2822.78
   502.1 2823.83   552.3 2827.01   562.3 2828.15   572.4 2830.98   582.4  2835.3
   612.5 2850.54   622.6 2856.26   642.7  2868.9   662.8 2882.85   672.8 2890.32
#Mann= 3 , 0 , 0
       0      .1       0   302.7    .045       0   317.7      .1       0
Bank Sta=302.7,317.7
XS Rating Curve= 0 ,0
Exp/Cntr=0.3,0.1

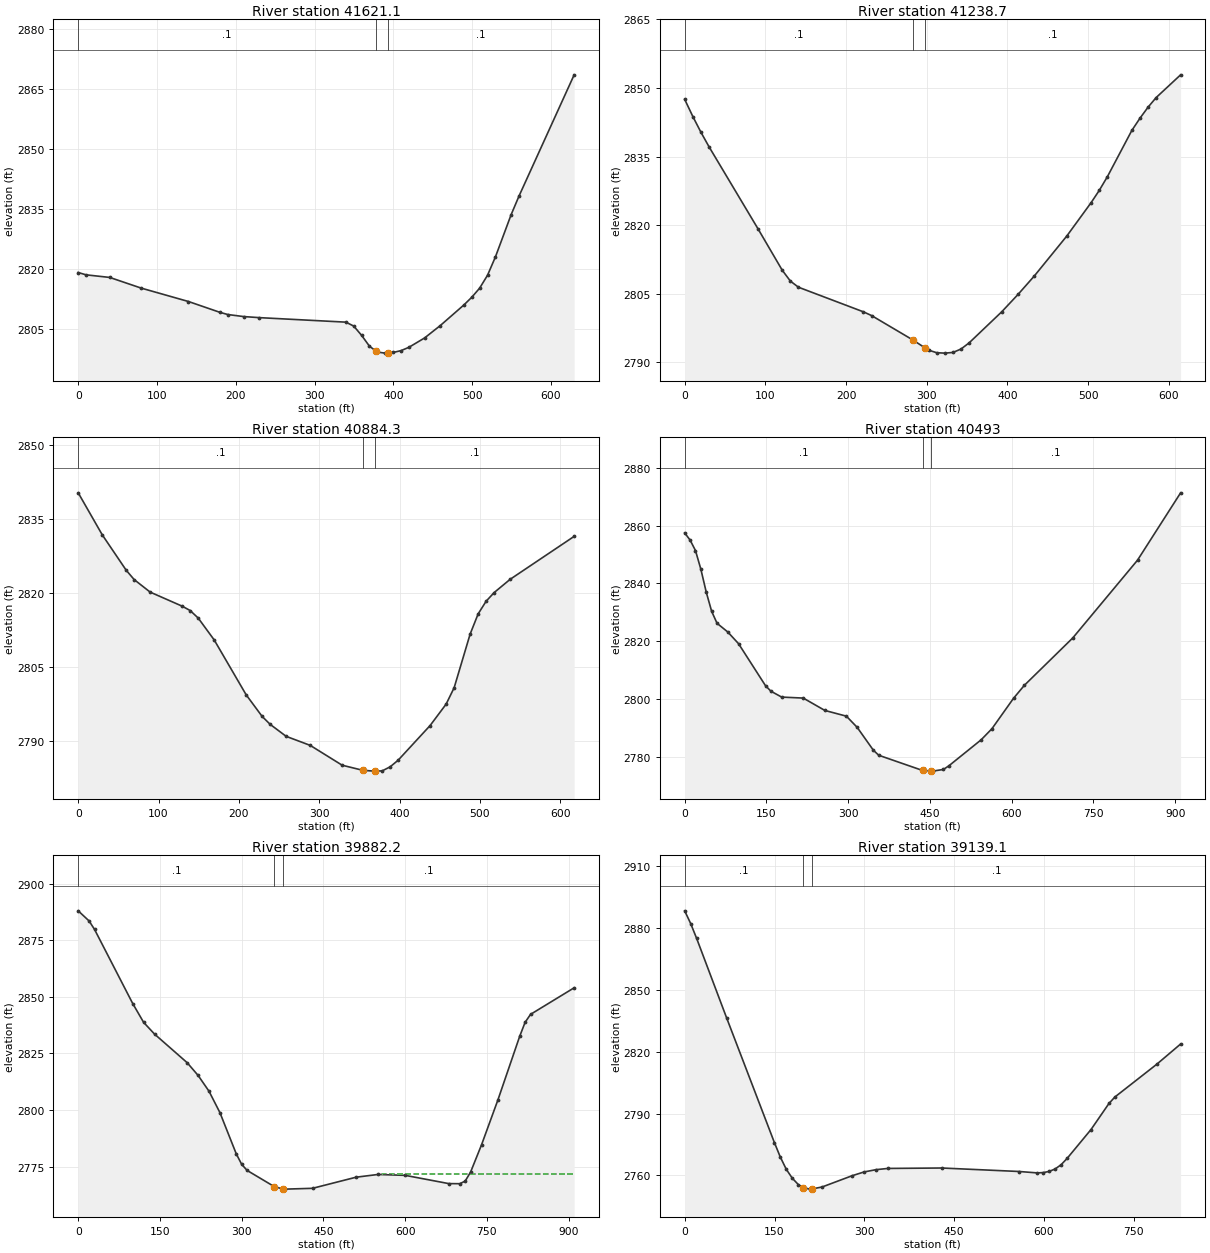
Type RM Length L Ch R = 1 ,41621.1 ,386.5,382.3,378.2
XS GIS Cut Line= 2
     2125369.741      420091.637     2125991.282      419992.456
#Sta/Elev= 30
       0 2819.06      10 2818.48      40 2817.83    79.9 2815.16   139.9  2811.8
   179.8 2809.09   189.8 2808.54   209.8 2808.03   229.8 2807.76   339.7 2806.63
   349.7 2805.64   359.7 2803.31   369.6 2800.61   377.6 2799.43   379.6 2799.13
   389.6 2798.87   392.6 2798.92   399.6 2799.03   409.6 2799.49   419.6 2800.32
   439.6 2802.67   459.6 2805.79   489.5 2810.94   499.5 2812.87   509.5 2815.16
   519.5 2818.39   529.5 2822.98   549.5 2833.59   559.5 2838.25   629.4 2868.58
#Mann= 3 , 0 , 0
       0      .1       0   377.6    .045       0   392.6      .1       0
Bank Sta=377.6,392.6
XS Rating Curve= 0 ,0
Exp/Cntr=0.3,0.1

Type RM Length L Ch R = 1 ,41238.7 ,356.8,354.5,352.1
XS GIS Cut Line= 2
     2125475.727      420507.502     2126056.955      420307.886
#Sta/Elev= 30
       0 2847.53    10.1 2843.77    20.2 2840.31    30.2 2837.14    90.7 2819.25
   120.9 2810.14     131 2807.76     141 2806.42   221.6 2801.03   231.7 2800.21
   282.5 2794.91   297.5 2793.19   302.2 2792.66   312.3 2792.09   322.4    2792
   332.5 2792.15   342.5  2792.9   352.6 2794.26   392.9 2801.04   413.1 2804.84
   433.2 2808.86   473.5 2817.61   503.7 2824.93   513.8 2827.61   523.9 2830.62
   554.1 2840.71   564.2 2843.39   574.2  2845.8   584.3 2847.92   614.6 2852.89
#Mann= 3 , 0 , 0
       0      .1       0   282.5    .045       0   297.5      .1       0
Bank Sta=282.5,297.5
XS Rating Curve= 0 ,0
Exp/Cntr=0.3,0.1

Type RM Length L Ch R = 1 ,40884.3 ,381.7,391.2,400.8
XS GIS Cut Line= 2
      2125636.17      420841.366     2126197.841      420585.107
#Sta/Elev= 30
       0  2840.3    29.9 2831.78    59.8 2824.57    69.7 2822.68    89.6 2820.14
   129.4 2817.29   139.4  2816.4   149.4 2814.87   169.3 2810.43   209.1 2799.29
     229  2794.9     239 2793.29   258.9 2790.86   288.8 2789.03   328.6    2785
   354.2 2783.97   368.4  2783.8   369.2  2783.8   378.4 2783.85   388.3 2784.67
   398.3 2786.02   438.1 2793.06     458  2797.4     468 2800.73   487.9 2811.62
   497.9 2815.73   507.8 2818.29   517.8 2820.05   537.7 2822.74   617.4 2831.46
#Mann= 3 , 0 , 0
       0      .1       0   354.2    .045       0   369.2      .1       0
Bank Sta=354.2,369.2
XS Rating Curve= 0 ,0
Exp/Cntr=0.3,0.1

Type RM Length L Ch R = 1 ,40493   ,608.3,610.9,613.5
XS GIS Cut Line= 3
     2125602.703      421064.765      2126057.68       421060.19
     2126512.657      421055.614
#Sta/Elev= 30
       0 2857.44     9.9 2854.97    19.8 2851.34    29.7 2844.87    39.6 2836.92
    49.5 2830.29    59.4 2826.16    79.1 2823.15    98.9 2819.09   148.4 2804.54
   158.3 2802.65     178 2800.62   217.6 2800.28   257.2    2796   296.7 2794.02
   316.5 2790.15   346.2 2782.24   356.1 2780.49   436.5 2775.23   451.5 2775.04
     455    2775   474.8 2775.58   484.7 2776.83     544 2785.84   563.8 2789.68
   603.4  2800.2   623.2 2804.68   712.2 2821.11   830.9    2848     910 2871.31
#Mann= 3 , 0 , 0
       0      .1       0   436.5    .045       0   451.5      .1       0
Bank Sta=436.5,451.5
XS Rating Curve= 0 ,0
Exp/Cntr=0.3,0.1

Type RM Length L Ch R = 1 ,39882.2 ,772.4,743,713.6
XS GIS Cut Line= 2
     2125628.414       421625.53     2126533.527      421719.718
#Sta/Elev= 30
       0 2888.06      20 2883.57      30 2879.82     100 2847.07     120 2838.75
     140 2833.57     200 2820.89     220 2815.27     240 2808.29     260 2798.84
     290  2780.6     300 2775.94     310 2773.26     360 2766.08     375 2765.12
     380    2765     430 2765.36     510 2770.28     550 2771.48     600 2771.09
     680 2767.44     700  2767.4     710 2768.53     720 2772.56     740 2784.55
     770 2804.37     810 2832.52     820 2838.76     830 2842.28     910 2854.03
#Mann= 3 , 0 , 0
       0      .1       0     360    .045       0     375      .1       0
#XS Ineff= 2 , 0
                          558.02         2771.73
Permanent Ineff=
       F       F
Bank Sta=360,375
XS Rating Curve= 0 ,0
Exp/Cntr=0.3,0.1

Type RM Length L Ch R = 1 ,39139.1 ,572.9,569.5,566
XS GIS Cut Line= 3
      2126046.36      422532.026     2126194.218      422161.079
     2126553.923        421927.6
#Sta/Elev= 30
       0 2888.47      10  2882.3      20 2875.05    69.9 2836.58   149.8 2775.93
   159.7 2768.88   169.7 2762.92   179.7  2758.6   189.7 2755.54   198.3 2753.95
   209.6  2753.3   213.3 2753.42   229.6 2754.35   279.5  2759.8   299.5 2761.64
   319.5 2762.75   339.4 2763.35   429.2 2763.56   558.9 2761.86   588.8 2761.18
   598.8 2761.33   608.8 2761.91   618.7  2763.1   628.7 2765.17   638.7 2768.24
   678.6 2782.26   708.5 2794.89   718.5 2798.06   788.3 2813.94   828.2 2823.78
#Mann= 3 , 0 , 0
       0      .1       0   198.3    .045       0   213.3      .1       0
Bank Sta=198.3,213.3
XS Rating Curve= 0 ,0
Exp/Cntr=0.3,0.1

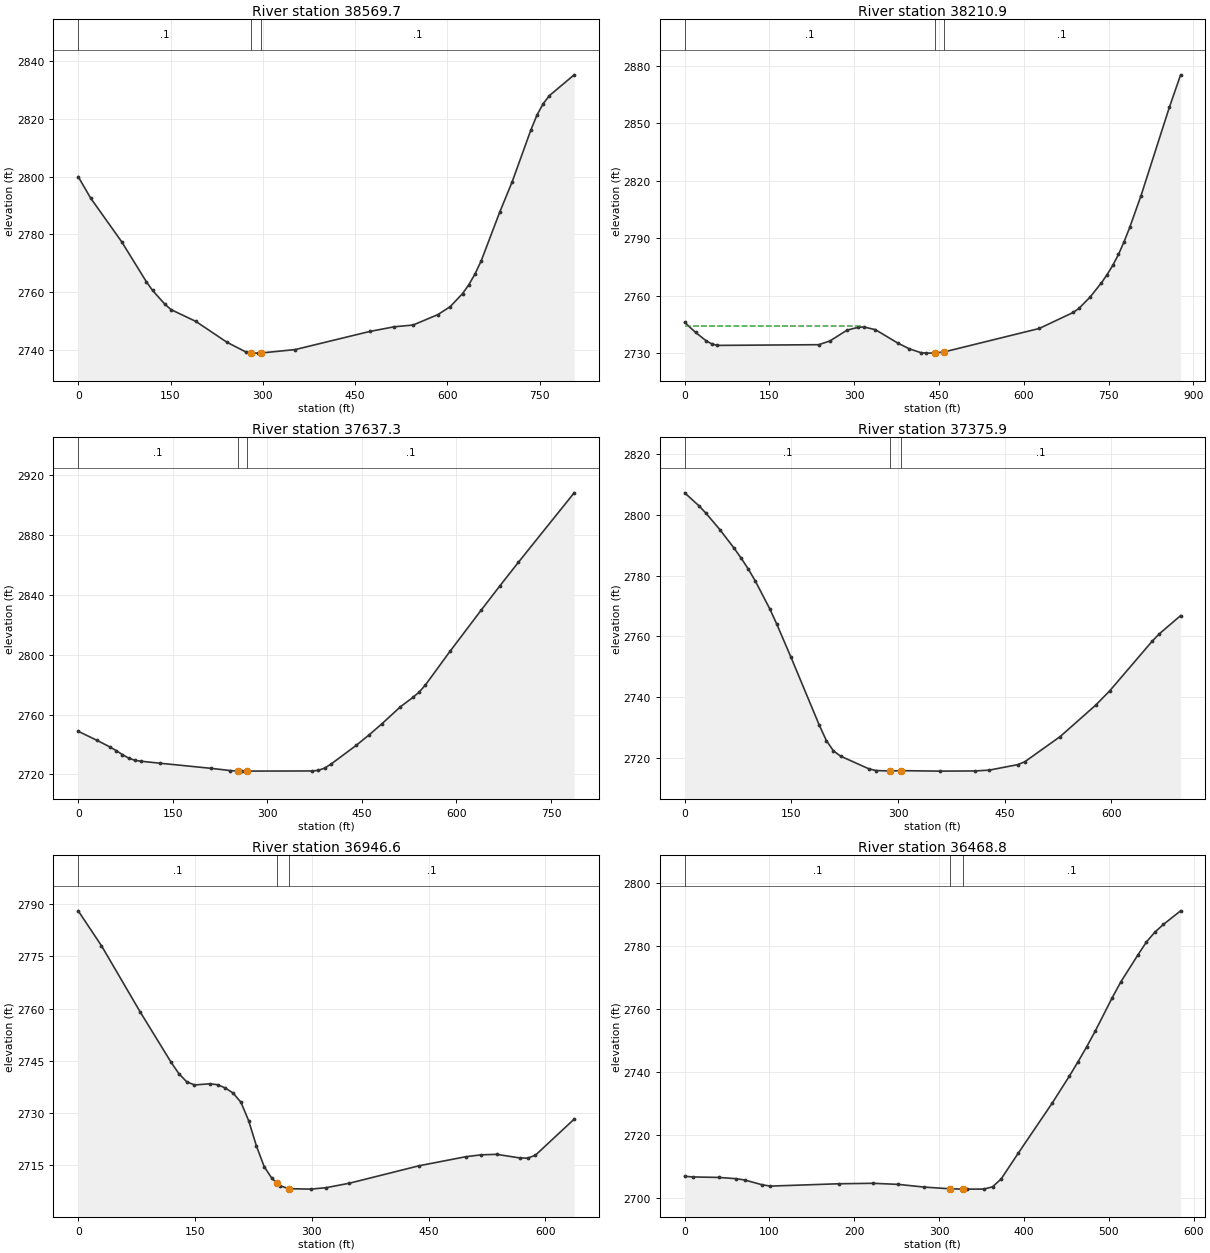
Type RM Length L Ch R = 1 ,38569.7 ,356.9,358.7,360.5
XS GIS Cut Line= 2
     2126604.706      422775.202     2126780.767      421988.614
#Sta/Elev= 30
       0 2800.03    20.2 2792.61    70.5 2777.51   110.8 2763.58   120.9 2760.57
   141.1 2755.74   151.1  2753.9   191.4 2749.81   241.8 2742.59     272 2739.29
   281.4  2738.9   292.2 2738.83   296.4 2738.86   352.6 2740.06   473.6 2746.34
   513.9 2747.98   544.1 2748.57   584.4 2752.18   604.5 2754.95   624.7  2759.5
   634.8 2762.56   644.8 2766.27   654.9 2770.82   685.1 2787.77   705.3 2798.28
   735.5 2816.16   745.6 2821.42   755.7 2825.36   765.8 2828.16     806 2835.37
#Mann= 3 , 0 , 0
       0      .1       0   281.4    .045       0   296.4      .1       0
Bank Sta=281.4,296.4
XS Rating Curve= 0 ,0
Exp/Cntr=0.3,0.1

Type RM Length L Ch R = 1 ,38210.9 ,538.6,573.6,608.6
XS GIS Cut Line= 3
     2126852.262      422919.479      2126907.29      422880.974
     2127142.851      422105.828
#Sta/Elev= 30
       0 2746.04    19.2 2740.82    38.4 2736.33      48 2734.81    57.6 2734.02
   237.2 2734.39   257.2 2736.38   287.2    2742   307.2 2743.48   317.2 2743.63
   337.2 2742.26   377.2 2735.21   397.2 2732.26   417.2 2730.28   427.2 2729.98
   443.5 2730.06   458.5 2730.58   627.3 2742.87   687.3 2751.24   697.3 2753.33
   717.3 2759.31   737.3 2766.76   747.3 2771.03   757.3 2775.86   767.3 2781.52
   777.3  2788.2   787.3 2795.71   807.3 2812.31   857.3 2858.37   877.3  2875.4
#Mann= 3 , 0 , 0
       0      .1       0   443.5    .045       0   458.5      .1       0
#XS Ineff= 2 , 0
          315.32 2743.96
Permanent Ineff=
       F       F
Bank Sta=443.5,458.5
XS Rating Curve= 0 ,0
Exp/Cntr=0.3,0.1

Type RM Length L Ch R = 1 ,37637.3 ,265.7,261.5,257.2
XS GIS Cut Line= 3
     2126863.885      422950.475      2127360.32      423072.618
     2127634.916      423051.213
#Sta/Elev= 30
       0 2748.86    30.1 2742.73    50.1 2738.42    60.2 2735.94    70.2 2733.25
    80.2 2730.86    90.2 2729.42   100.2  2728.8   130.3 2727.46   210.5 2724.08
   240.6 2722.61   253.1 2722.25   260.6  2722.2   268.1 2722.23   370.9 2722.31
   380.9 2722.72     391 2724.24     401 2726.89   441.1 2739.48   461.1 2746.33
   481.2 2753.65   511.2 2765.28   530.9  2771.5   540.8 2775.04   550.6 2779.73
   589.9  2802.4   639.1 2829.81   668.6 2845.97   698.1  2861.8   786.7 2908.34
#Mann= 3 , 0 , 0
       0      .1       0   253.1    .045       0   268.1      .1       0
Bank Sta=253.1,268.1
XS Rating Curve= 0 ,0
Exp/Cntr=0.3,0.1

Type RM Length L Ch R = 1 ,37375.9 ,433.5,429.3,425.1
XS GIS Cut Line= 2
     2126729.525      423238.952     2127425.623      423282.772
#Sta/Elev= 30
       0 2807.19    19.9 2802.96    29.9 2800.51    49.8 2795.01    69.8 2788.91
    79.7 2785.63    89.7 2782.08    99.6  2778.1   119.6 2769.11   129.5 2764.06
   149.5 2753.17   189.3 2730.85   199.3 2725.78   209.2 2722.41   219.2 2720.67
   259.1 2716.49     269 2715.94   288.8 2715.78   303.8  2715.9   358.7 2715.74
   408.5  2715.8   428.4 2716.07   468.3 2717.87   478.3 2718.81   528.1  2727.1
   577.9 2737.39   597.8 2742.13   657.6 2758.46   667.6 2760.87   697.5 2766.85
#Mann= 3 , 0 , 0
       0      .1       0   288.8    .045       0   303.8      .1       0
Bank Sta=288.8,303.8
XS Rating Curve= 0 ,0
Exp/Cntr=0.3,0.1

Type RM Length L Ch R = 1 ,36946.6 ,479.1,477.7,476.3
XS GIS Cut Line= 2
     2126743.662      423714.526     2127374.986      423630.239
#Sta/Elev= 30
       0 2788.03    29.9 2778.01    79.6 2759.03   119.4 2744.54   129.4 2741.29
   139.3 2738.99   149.3 2738.08   169.2 2738.42   179.1 2738.15   189.1  2737.2
     199 2735.74     209  2733.1   218.9 2727.83   228.9 2720.56   238.8 2714.67
   248.8 2711.27   255.4 2709.89   258.8  2709.2   270.4 2708.33   298.6  2708.2
   318.5 2708.62   348.3  2709.9   437.9 2714.91   497.6 2717.49   517.5 2718.04
   537.4 2718.18   567.3 2717.14   577.2 2717.09   587.2 2717.93   636.9 2728.28
#Mann= 3 , 0 , 0
       0      .1       0   255.4    .045       0   270.4      .1       0
Bank Sta=255.4,270.4
XS Rating Curve= 0 ,0
Exp/Cntr=0.3,0.1

Type RM Length L Ch R = 1 ,36468.8 ,363.2,385.6,407.8
XS GIS Cut Line= 2
     2126922.828       424154.09      2127496.73      424041.637
#Sta/Elev= 30
       0 2707.03    10.1 2706.83    40.3 2706.68    60.5 2706.28    70.6 2705.88
    90.8 2704.39   100.8 2703.93   181.5 2704.67   221.8 2704.82   252.1 2704.47
   282.3 2703.62   313.2 2703.07   328.2 2702.98   332.7 2702.97   352.9 2702.99
     363  2703.7   373.1 2706.18   393.2 2714.31   433.6 2730.34   453.7 2738.85
   463.8 2743.34   473.9 2748.04     484 2753.02   504.2 2763.69   514.2 2768.64
   534.4 2777.21   544.5 2781.34   554.6  2784.5   564.6 2786.92   584.8 2791.21
#Mann= 3 , 0 , 0
       0      .1       0   313.2    .045       0   328.2      .1       0
Bank Sta=313.2,328.2
XS Rating Curve= 0 ,0
Exp/Cntr=0.3,0.1