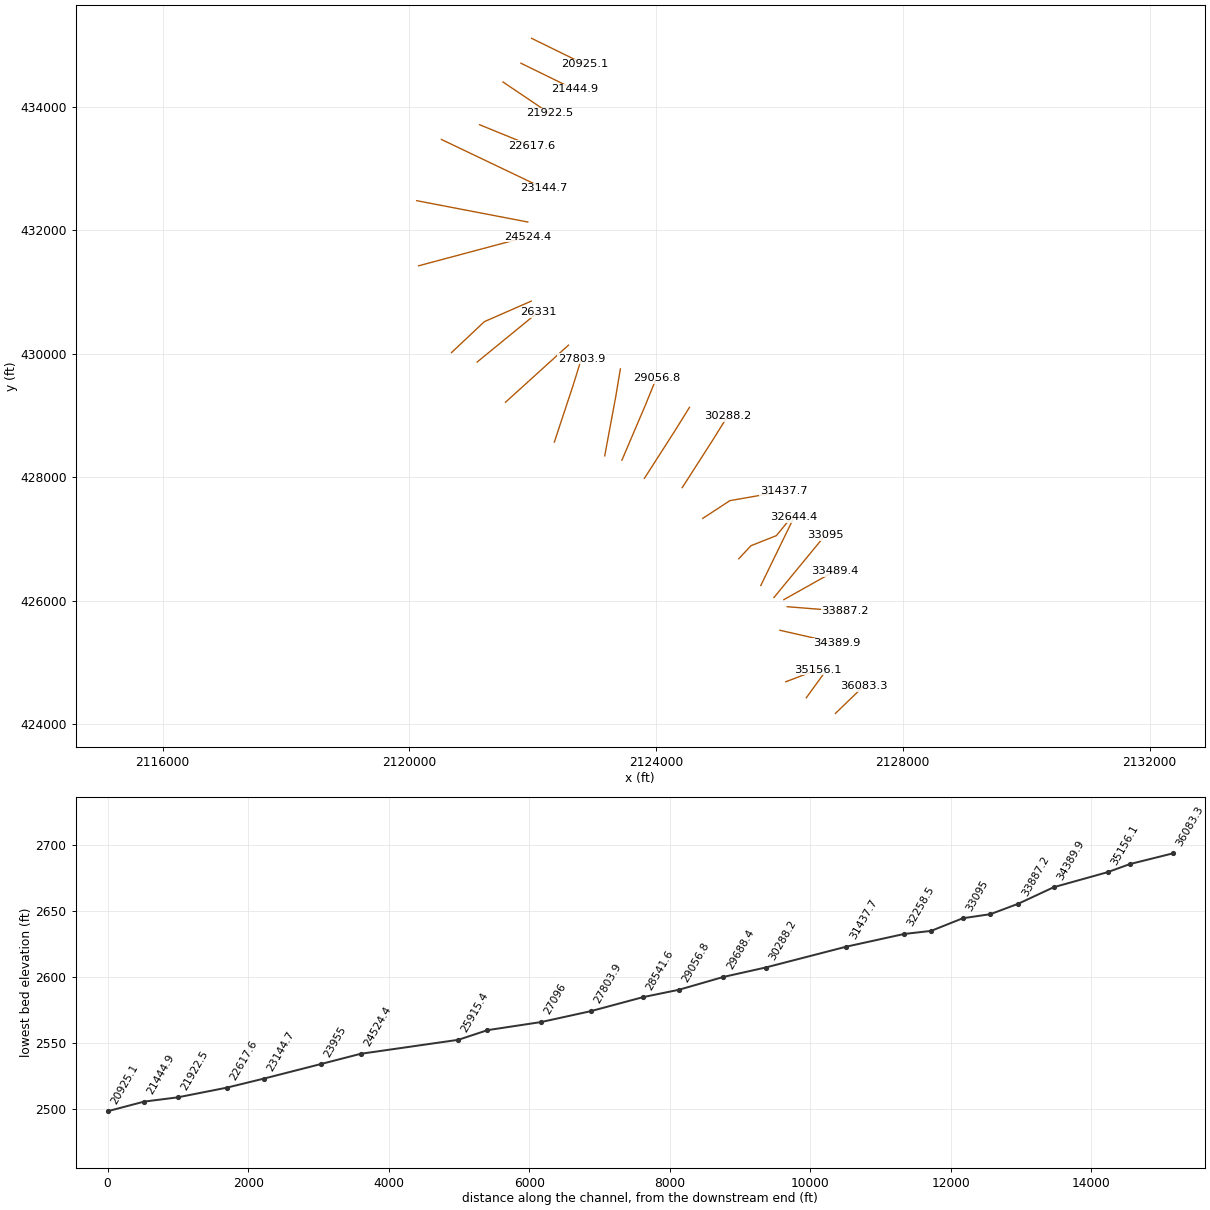
HEC-RAS study SFrkChryRv.prj: SFrkChryRv

--- SFrkChryRv.g01 (geometry) --- (continued)

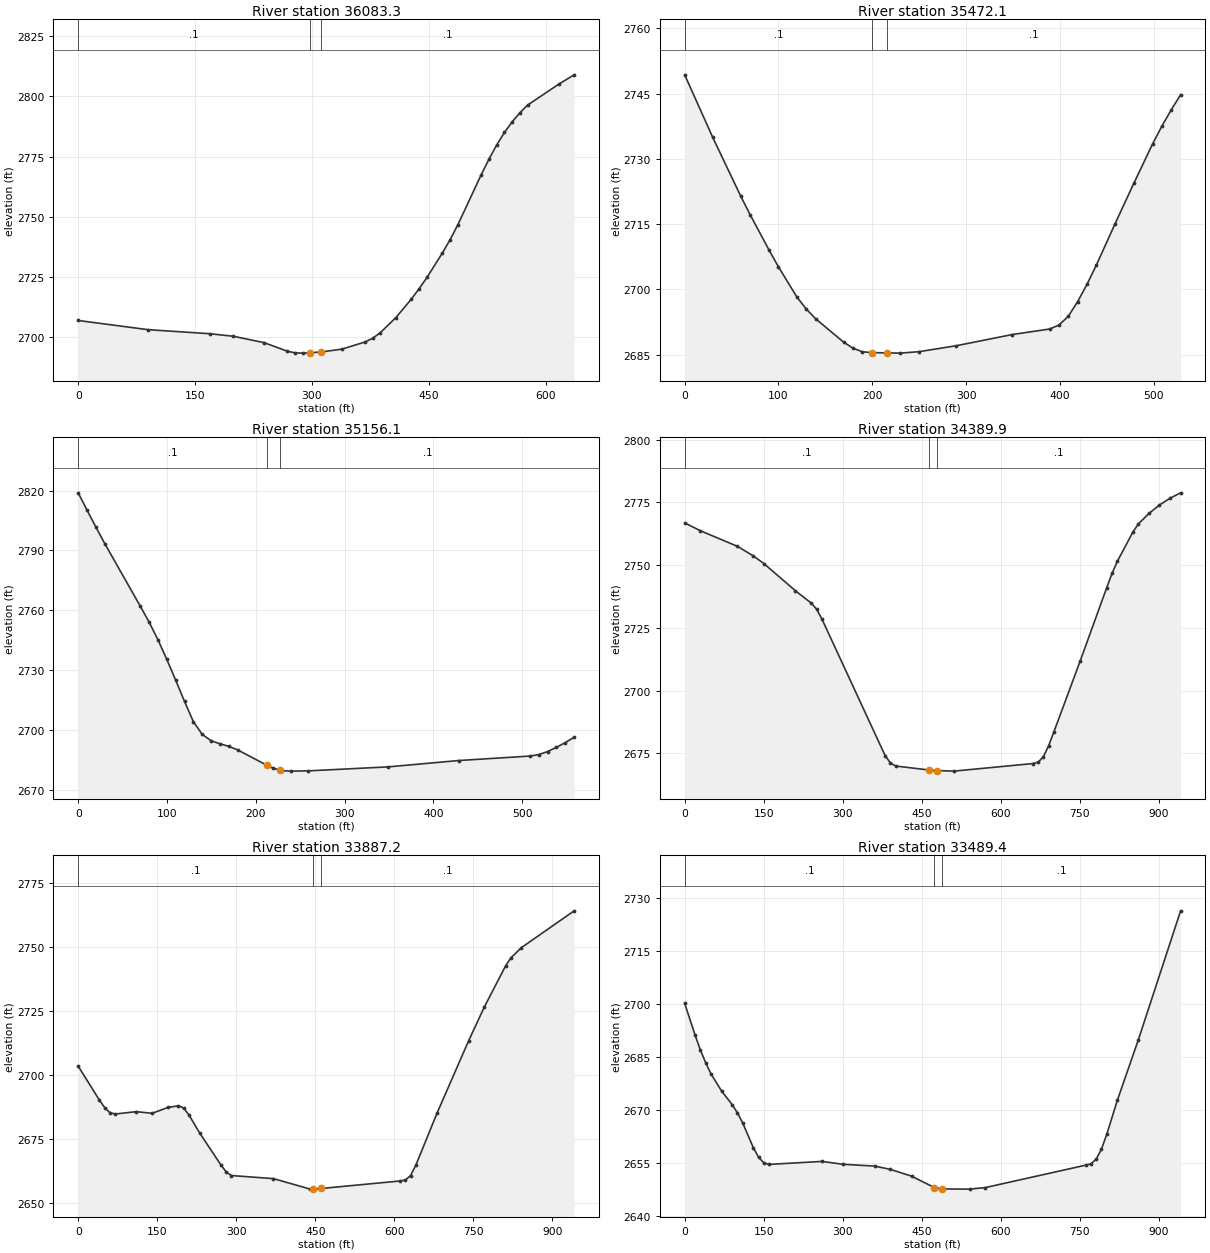
Type RM Length L Ch R = 1 ,36083.3 ,606.4,611.2,616
XS GIS Cut Line= 2
     2126908.575       424174.03      2127366.81        424616.1
#Sta/Elev= 30
       0 2706.96    89.5 2703.15   169.1 2701.46     199 2700.42   238.8 2697.74
   268.6  2694.2   278.6 2693.52   288.5 2693.41     297 2693.55     312  2693.9
   338.2 2695.05   368.1 2698.02     378 2699.57     388 2701.94   407.9 2708.18
   427.8 2715.87   437.7 2720.16   447.7  2724.8   467.6 2735.01   477.5 2740.53
   487.5 2746.77   517.3  2767.4   527.3 2773.88   537.2 2779.79   547.2    2785
   557.1 2789.39   567.1 2793.19     577 2796.38   616.8 2805.02   636.7 2808.92
#Mann= 3 , 0 , 0
       0      .1       0     297    .045       0     312      .1       0
Bank Sta=297,312
XS Rating Curve= 0 ,0
Exp/Cntr=0.3,0.1

Type RM Length L Ch R = 1 ,35472.1 ,329.6,316,302.4
XS GIS Cut Line= 2
     2126435.612      424426.538     2126746.007      424854.549
#Sta/Elev= 30
       0 2749.31    29.9 2734.94    59.8  2721.4    69.8 2717.16    89.8 2709.08
    99.8 2705.24   119.7 2698.21   129.7 2695.46   139.7 2693.22   169.6 2687.84
   179.6 2686.46   189.5 2685.65   200.2 2685.45   215.2  2685.4   229.4 2685.34
   249.4 2685.66   289.3 2687.03   349.2 2689.61     389 2690.88     399 2691.79
     409 2693.82     419  2697.2     429  2701.2   438.9 2705.58   458.9 2715.12
   478.8 2724.36   498.8 2733.42   508.8 2737.54   518.7 2741.26   528.7 2744.74
#Mann= 3 , 0 , 0
       0      .1       0   200.2    .045       0   215.2      .1       0
Bank Sta=200.2,215.2
XS Rating Curve= 0 ,0
Exp/Cntr=0.3,0.1

Type RM Length L Ch R = 1 ,35156.1 ,775.5,766.2,756.5
XS GIS Cut Line= 2
     2126102.481      424685.878     2126624.767      424883.661
#Sta/Elev= 30
       0 2818.86      10 2810.12      20 2801.61    29.9 2793.39    69.8 2762.08
    79.8 2754.03    89.8 2745.14    99.7 2735.34   109.7 2724.94   119.7 2714.22
   129.6 2704.12   139.6  2697.7   149.6 2694.49   159.6 2692.96   169.5 2691.66
   179.5 2689.89   212.7 2682.12   219.4 2680.71   227.7 2679.71   229.4 2679.51
   239.4 2679.23   259.3 2679.37     349 2681.36   428.8 2684.56   508.6 2686.78
   518.6  2687.5   528.6 2689.05   538.5 2691.15   548.5 2693.54   558.5 2696.23
#Mann= 3 , 0 , 0
       0      .1       0   212.7    .045       0   227.7      .1       0
Bank Sta=212.7,227.7
XS Rating Curve= 0 ,0
Exp/Cntr=0.3,0.1

Type RM Length L Ch R = 1 ,34389.9 ,503.3,502.7,502.5
XS GIS Cut Line= 2
     2126009.415      425519.673     2126927.498      425311.507
#Sta/Elev= 30
       0 2766.85      30  2763.7   100.2 2757.49   130.2 2753.71   150.2 2750.65
   210.3 2739.77   240.4 2734.85   250.4 2732.45   260.4 2728.56   380.6 2674.02
   390.6 2671.14   400.6 2669.92   463.2 2668.34   478.2 2668.12   510.8 2667.88
     661  2670.9     671 2671.43     681 2673.66     691 2678.07     701 2683.61
   751.1 2711.98   801.2 2741.06   811.2 2746.69   821.2 2751.51   851.2 2763.31
   861.3 2766.46   881.3  2770.6   901.3 2773.98   921.4  2776.7   941.4 2778.83
#Mann= 3 , 0 , 0
       0      .1       0   463.2    .045       0   478.2      .1       0
Bank Sta=463.2,478.2
XS Rating Curve= 0 ,0
Exp/Cntr=0.3,0.1

Type RM Length L Ch R = 1 ,33887.2 ,383.7,397.9,412
XS GIS Cut Line= 2
      2126125.29      425901.932     2127063.695      425827.055
#Sta/Elev= 30
       0 2703.44    40.1 2690.22    50.1  2687.3    60.1 2685.33    70.1 2684.76
   110.2 2685.68   140.2 2685.04   170.2 2687.31   190.3 2687.97   200.3 2687.08
   210.3 2684.36   230.3 2677.43   270.4 2665.02   280.4 2662.29   290.4 2660.75
   370.6 2659.54   440.6 2655.44   446.4 2655.47   461.4 2655.69   610.9 2658.62
   620.9 2658.97   630.9 2660.75   640.9 2664.78     681 2685.04   741.1 2713.35
   771.1 2726.64   811.2 2742.55   821.2 2745.69   841.2  2749.7   941.4 2764.08
#Mann= 3 , 0 , 0
       0      .1       0   446.4    .045       0   461.4      .1       0
Bank Sta=446.4,461.4
XS Rating Curve= 0 ,0
Exp/Cntr=0.3,0.1

Type RM Length L Ch R = 1 ,33489.4 ,386.2,394.3,402.5
XS GIS Cut Line= 2
      2126072.62       426016.61     2126893.778      426476.946
#Sta/Elev= 30
       0  2700.1      20 2691.03      30 2686.81    40.1 2683.24    50.1 2680.11
    70.1 2675.28    90.1 2671.46   100.2  2669.1   110.2 2666.23   130.2 2659.29
   140.2 2656.58   150.2 2654.94   160.2 2654.52   260.4 2655.36   300.4 2654.56
   360.5 2654.04   390.6 2653.11   430.6 2651.19   473.9 2647.97   488.9 2647.57
   540.8 2647.52   570.8 2647.96   761.1  2654.3   771.1 2654.69   781.2    2656
   791.2 2658.86   801.2 2663.04   821.2 2672.62   861.3 2689.85   941.4 2726.31
#Mann= 3 , 0 , 0
       0      .1       0   473.9    .045       0   488.9      .1       0
Bank Sta=473.9,488.9
XS Rating Curve= 0 ,0
Exp/Cntr=0.3,0.1

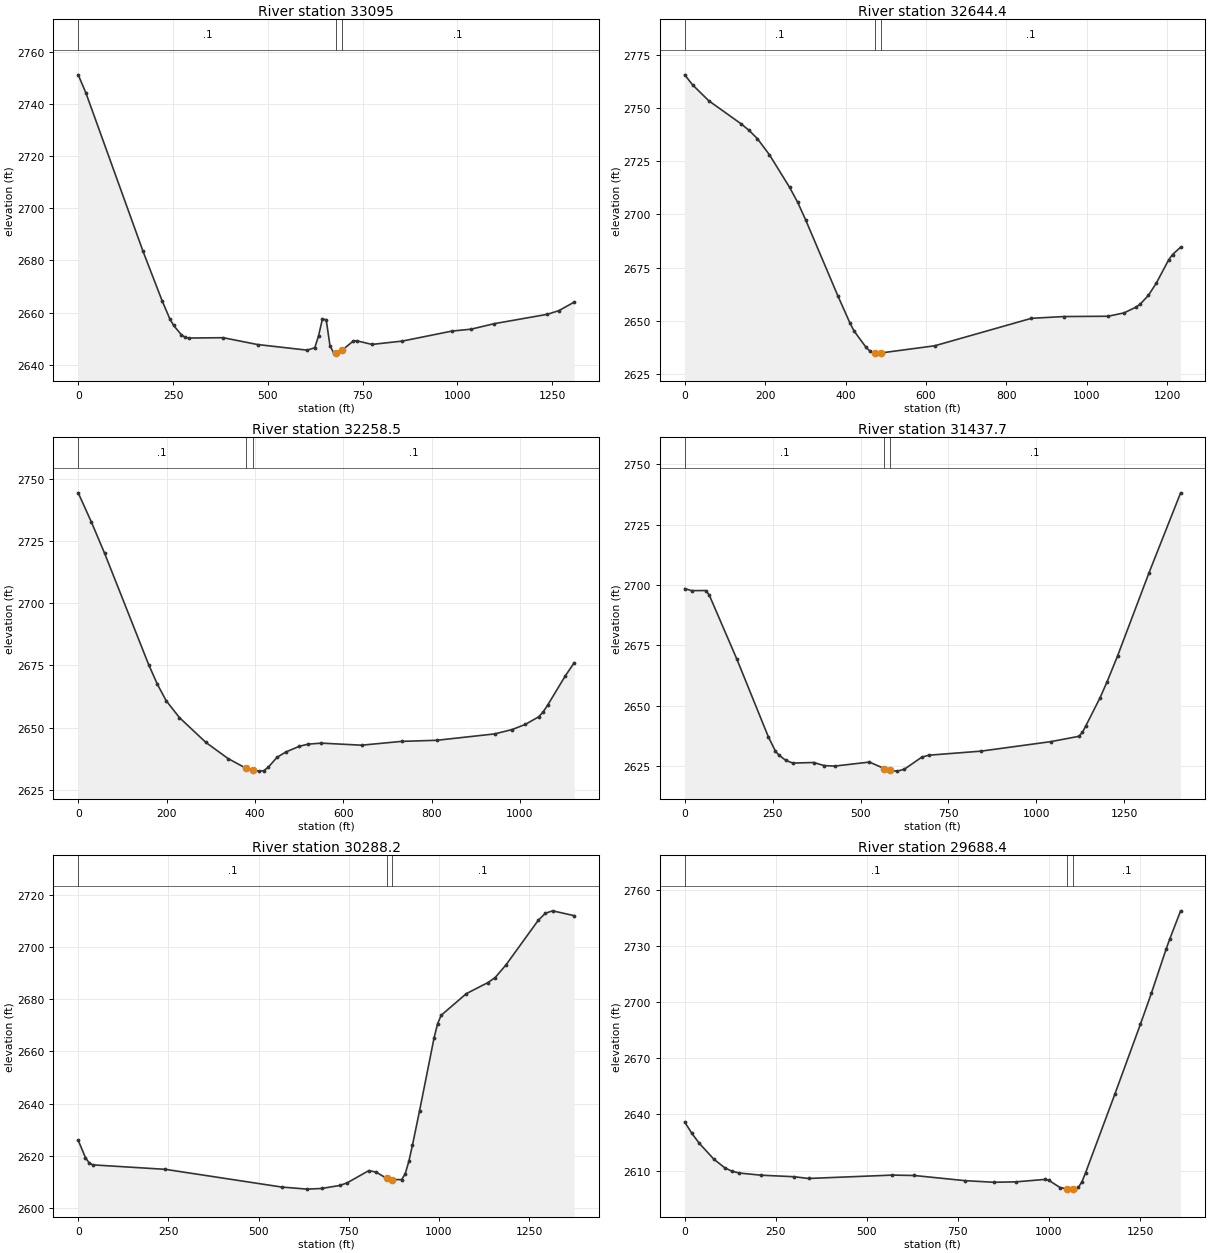
Type RM Length L Ch R = 1 ,33095   ,445,450.6,456.3
XS GIS Cut Line= 2
     2125910.752      426050.097     2126742.019       427059.62
#Sta/Elev= 30
       0  2751.2    20.1 2744.32     171 2683.46   221.3 2664.49   241.4 2657.63
   251.5 2655.07   271.6 2651.52   281.7  2650.5   291.7 2650.21   382.3 2650.34
   472.8 2647.72   603.6 2645.56   623.7 2646.49   633.7 2651.03   643.8 2657.45
   653.9 2657.25   663.9 2647.26     674 2644.42   680.7 2644.53   695.7 2645.54
   724.3 2648.94   734.3 2649.16   774.6 2647.76     855 2649.05   985.8 2652.89
  1036.1 2653.61  1096.5 2655.71  1237.3 2659.32  1267.5 2660.73  1307.7 2663.99
#Mann= 3 , 0 , 0
       0      .1       0   680.7    .045       0   695.7      .1       0
Bank Sta=680.7,695.7
XS Rating Curve= 0 ,0
Exp/Cntr=0.3,0.1

Type RM Length L Ch R = 1 ,32644.4 ,402.9,385.9,368.9
XS GIS Cut Line= 2
     2125698.187      426245.469     2126238.163      427354.143
#Sta/Elev= 30
       0 2765.49      20 2760.72    60.2 2753.28   140.4 2742.48   160.4 2739.37
   180.5 2735.59   210.5 2728.06   260.7 2712.73   280.7 2705.78   300.8 2697.42
     381 2661.73   411.1 2648.95   421.1 2645.28   451.2 2637.54   461.2 2635.72
   472.6 2634.95   481.2 2634.87   487.6 2634.95   621.6 2638.31   862.2 2651.21
   942.4 2652.04  1052.7 2652.18  1092.8 2653.77  1122.9 2656.53  1132.9 2657.93
    1153 2661.95    1173 2667.82  1203.1 2678.53  1213.1 2681.16  1233.2 2684.59
#Mann= 3 , 0 , 0
       0      .1       0   472.6    .045       0   487.6      .1       0
Bank Sta=472.6,487.6
XS Rating Curve= 0 ,0
Exp/Cntr=0.3,0.1

Type RM Length L Ch R = 1 ,32258.5 ,825.3,820.8,816.3
XS GIS Cut Line= 4
     2125341.196      426677.771     2125537.847      426889.399
     2125949.906      427052.309     2126197.952      427354.143
#Sta/Elev= 30
       0 2744.35    29.9 2732.58    59.8 2720.03   159.4 2675.36   179.3  2667.4
   199.2  2660.8   229.1 2654.04   288.9 2644.08   339.2 2637.58   379.9 2633.67
   394.9 2633.01   409.7 2632.52   419.8 2632.68   429.9 2634.02     450 2638.05
   470.2 2640.22   500.4  2642.5   520.5 2643.36   550.7 2643.77   641.4 2642.94
     732 2644.47   812.1 2644.92   942.4 2647.47   982.4 2649.23  1012.5 2651.33
  1042.5 2654.36  1052.5  2656.3  1062.6 2659.01  1102.6 2670.77  1122.7 2676.05
#Mann= 3 , 0 , 0
       0      .1       0   379.9    .045       0   394.9      .1       0
Bank Sta=379.9,394.9
XS Rating Curve= 0 ,0
Exp/Cntr=0.3,0.1

Type RM Length L Ch R = 1 ,31437.7 ,1130.4,1149.4,1168.5
XS GIS Cut Line= 4
     2124757.378      427332.383     2125197.325      427619.687
     2125616.971      427693.097     2126067.453      427778.389
#Sta/Elev= 30
       0 2698.47    19.8 2697.64    59.5 2697.68    69.4 2695.96   148.7 2669.17
   237.9 2637.14   257.8 2631.29   267.7 2629.61   287.5  2627.4   307.3 2626.28
   366.8 2626.52   396.6 2625.25   426.3 2625.03   525.4  2626.7   567.6    2624
   582.6 2623.23   604.7 2622.95   624.5 2623.73   674.1 2628.73   693.9 2629.54
   842.5 2631.22  1041.2 2635.16  1120.9 2637.36  1130.9 2639.02  1140.8 2641.78
  1180.7 2653.24  1200.6 2659.81  1230.6 2670.58  1320.2 2705.05    1410 2738.11
#Mann= 3 , 0 , 0
       0      .1       0   567.6    .045       0   582.6      .1       0
Bank Sta=567.6,582.6
XS Rating Curve= 0 ,0
Exp/Cntr=0.3,0.1

Type RM Length L Ch R = 1 ,30288.2 ,599.5,599.8,600.1
XS GIS Cut Line= 3
     2124424.338      427830.027     2124919.639      428601.504
     2125161.938      428990.734
#Sta/Elev= 30
       0 2625.92    20.2 2619.26    30.2 2617.27    40.3  2616.5   241.8 2614.78
   564.2 2607.99   634.7 2607.19     675 2607.44   725.4  2608.6   745.5 2609.58
     806  2614.3   826.1 2613.71   855.8 2611.29   870.8 2610.86   896.6 2610.82
   906.7 2613.04   916.8  2617.8   926.8 2623.99   946.7 2637.32   986.6 2665.05
   996.5 2670.61  1006.5 2673.89  1076.3 2682.19  1136.1 2686.43    1156 2688.33
  1185.9 2693.15  1275.6  2710.3  1295.5 2713.03  1315.5 2713.96  1375.3 2712.11
#Mann= 3 , 0 , 0
       0      .1       0   855.8    .045       0   870.8      .1       0
Bank Sta=855.8,870.8
XS Rating Curve= 0 ,0
Exp/Cntr=0.3,0.1

Type RM Length L Ch R = 1 ,29688.4 ,627.8,631.7,635.6
XS GIS Cut Line= 3
     2123811.833      427981.683     2124303.369      428747.296
     2124541.984      429130.609
#Sta/Elev= 30
       0  2635.9      20 2629.78      40 2624.57      80 2616.09     110 2611.46
     130 2609.61     150 2608.67     210 2607.51   299.9 2606.71   339.9 2605.77
   569.9 2607.57   629.9 2607.36   769.8  2604.6   849.8 2603.74   909.8 2603.97
   990.1 2605.29  1000.1 2604.71  1030.2 2600.94  1050.4 2600.18  1065.4  2600.1
  1070.4 2600.08  1080.4 2600.97  1090.4 2603.99  1100.5 2608.86  1180.7 2650.76
    1251 2688.14  1281.1 2704.69  1321.2 2728.05  1331.2 2733.48  1361.3 2748.64
#Mann= 3 , 0 , 0
       0      .1       0  1050.4    .045       0  1065.4      .1       0
#XS Ineff= 2 , 0
          605.14 2607.37
Permanent Ineff=
       F       F
Bank Sta=1050.4,1065.4
XS Rating Curve= 0 ,0
Exp/Cntr=0.3,0.1

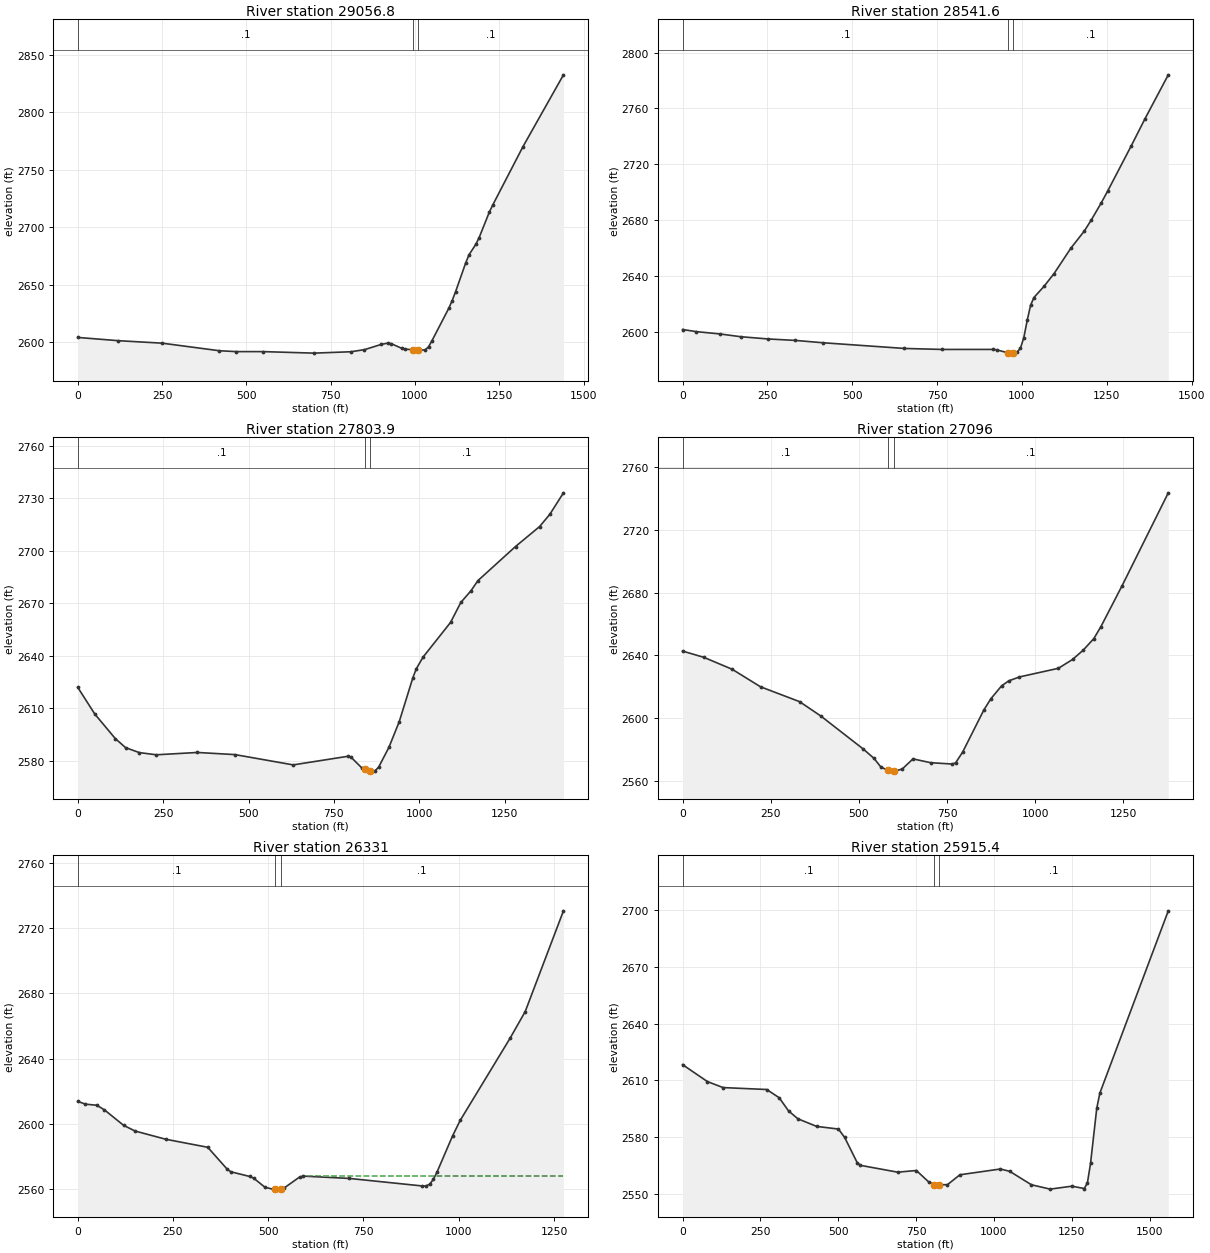
Type RM Length L Ch R = 1 ,29056.8 ,510.7,515.2,519.9
XS GIS Cut Line= 3
     2123446.331      428274.952     2123831.349      429176.638
     2124004.098       429602.94
#Sta/Elev= 30
       0 2604.07     120 2601.24   250.1 2599.08   420.2 2592.48   470.2 2591.73
   550.2 2591.72   700.3 2590.41   810.4 2591.61   850.4 2593.44   900.4 2598.02
   920.4 2599.15   930.4 2598.55   960.4 2594.65   970.4 2593.88   995.3 2593.33
  1010.3 2593.07  1030.4 2593.21  1040.4 2595.97  1050.4 2601.14  1100.4 2629.46
  1110.4 2636.09  1120.4 2643.73  1150.4 2668.81  1160.4 2676.02  1180.4 2684.98
  1190.4 2690.96  1220.4 2712.98  1230.4 2719.11  1320.4  2770.1  1440.4 2832.54
#Mann= 3 , 0 , 0
       0      .1       0   995.3    .045       0  1010.3      .1       0
Bank Sta=995.3,1010.3
XS Rating Curve= 0 ,0
Exp/Cntr=0.3,0.1

Type RM Length L Ch R = 1 ,28541.6 ,740.6,737.7,734.5
XS GIS Cut Line= 3
     2123167.823       428344.85     2123346.434      429304.172
     2123421.457      429753.284
#Sta/Elev= 30
       0 2601.69    40.2 2600.18   110.7  2598.5     171 2596.54   251.5 2594.93
     332 2593.89   412.4 2592.23   653.9 2588.13   764.6 2587.42   915.4 2587.43
   925.5 2587.13   959.6 2584.95   965.8 2584.78   974.6  2584.8   985.7 2585.48
   995.6 2588.35  1005.5 2595.88  1015.4 2608.17  1025.3  2618.9  1035.2 2624.58
  1064.9 2632.55  1094.6 2641.75  1144.1 2659.92  1183.7 2672.18  1203.5 2679.78
  1233.2 2692.17    1253 2701.03  1322.3 2733.33  1361.8 2752.26  1431.1 2784.02
#Mann= 3 , 0 , 0
       0      .1       0   959.6    .045       0   974.6      .1       0
Bank Sta=959.6,974.6
XS Rating Curve= 0 ,0
Exp/Cntr=0.3,0.1

Type RM Length L Ch R = 1 ,27803.9 ,720.2,707.9,695.7
XS GIS Cut Line= 3
     2122351.102      428567.967     2122656.368      429489.911
     2122790.071      429920.317
#Sta/Elev= 30
       0 2622.09    50.1 2606.81   110.1 2592.82   140.2 2587.65   180.2 2584.84
   230.3 2583.58   350.4 2584.91   460.6 2583.68   630.8 2577.82     791 2582.73
     801 2582.04     831 2576.22   841.7 2575.19   856.7 2574.43     861 2574.26
     871 2574.53   881.1  2576.6   911.1 2587.88   941.1 2602.42   981.2 2627.61
   991.2 2632.67  1011.2 2639.38  1091.4 2659.09  1121.4 2670.46  1151.4  2677.2
  1171.5 2682.93  1281.6  2702.4  1351.8 2713.73  1381.8  2720.7  1421.9 2733.02
#Mann= 3 , 0 , 0
       0      .1       0   841.7    .045       0   856.7      .1       0
Bank Sta=841.7,856.7
XS Rating Curve= 0 ,0
Exp/Cntr=0.3,0.1

Type RM Length L Ch R = 1 ,27096   ,766.2,765,763.9
XS GIS Cut Line= 2
     2121559.267        429213.6     2122580.193      430138.037
#Sta/Elev= 30
       0 2642.71    60.3 2638.71   140.7 2631.09   221.2 2619.88   331.8  2610.4
   392.1 2601.23   512.7 2580.09   542.9 2574.16     563 2568.48   583.8  2566.5
   598.8 2566.11   603.2 2566.01   623.3 2567.43   653.4 2573.82   703.7  2571.4
     764 2570.55   774.1 2571.24   794.2 2578.16   854.5 2605.15   874.6 2612.34
   904.8 2620.52   924.9 2623.66     955 2626.17  1065.6 2631.69  1105.8 2637.34
    1136 2643.26  1166.2 2650.68  1186.3 2658.31  1246.6 2684.58  1377.3  2743.8
#Mann= 3 , 0 , 0
       0      .1       0   583.8    .045       0   598.8      .1       0
Bank Sta=583.8,598.8
XS Rating Curve= 0 ,0
Exp/Cntr=0.3,0.1

Type RM Length L Ch R = 1 ,26331   ,421.8,415.6,409.4
XS GIS Cut Line= 2
     2121100.282       429865.18     2122087.552       430671.84
#Sta/Elev= 30
       0 2613.76    20.1 2612.03    50.2 2611.35    70.3  2608.5   120.5 2599.02
   150.6 2595.53   230.9  2590.5   341.3 2585.55   391.5 2572.34   401.6 2570.53
   451.7 2567.63   461.8 2566.62   491.9 2560.94     512 2559.87   517.5 2559.92
   532.5 2560.12   542.1 2560.61   582.2 2567.28   592.3 2567.86   712.8 2566.44
   903.5 2561.84   913.5 2561.76   923.6 2562.88   933.6 2565.88   943.6 2570.63
   983.8 2592.52  1003.9 2602.07  1134.4 2652.34  1174.5 2668.84  1274.9 2730.69
#Mann= 3 , 0 , 0
       0      .1       0   517.5    .045       0   532.5      .1       0
#XS Ineff= 2 , 0
                          602.66         2567.89
Permanent Ineff=
       F       F
Bank Sta=517.5,532.5
XS Rating Curve= 0 ,0
Exp/Cntr=0.3,0.1

Type RM Length L Ch R = 1 ,25915.4 ,1393.5,1391,1388.2
XS GIS Cut Line= 3
     2120684.014      430017.613     2121216.482      430518.619
     2121975.934      430850.944
#Sta/Elev= 30
       0 2618.35    80.1 2609.37   130.2 2606.22   270.4  2605.2   310.5 2600.84
   340.5 2593.89   370.6 2589.72   430.7 2585.71   500.8  2584.3   520.8 2579.86
   560.9  2566.6   570.9 2565.15     691 2561.53   751.1 2562.41     791  2556.3
   808.8 2554.94   823.8 2554.84     851 2554.94   890.9 2560.16  1020.8  2563.2
  1050.7 2561.99  1120.6 2554.87  1180.6 2552.57  1250.5 2554.13  1290.4 2552.89
  1300.4  2555.9  1310.4 2566.15  1330.4 2595.28  1340.4 2603.32  1560.1 2699.59
#Mann= 3 , 0 , 0
       0      .1       0   808.8    .045       0   823.8      .1       0
#XS Ineff= 2 , 0
                         1021.79         2562.95
Permanent Ineff=
       F       F
Bank Sta=808.8,823.8
XS Rating Curve= 0 ,0
Exp/Cntr=0.3,0.1

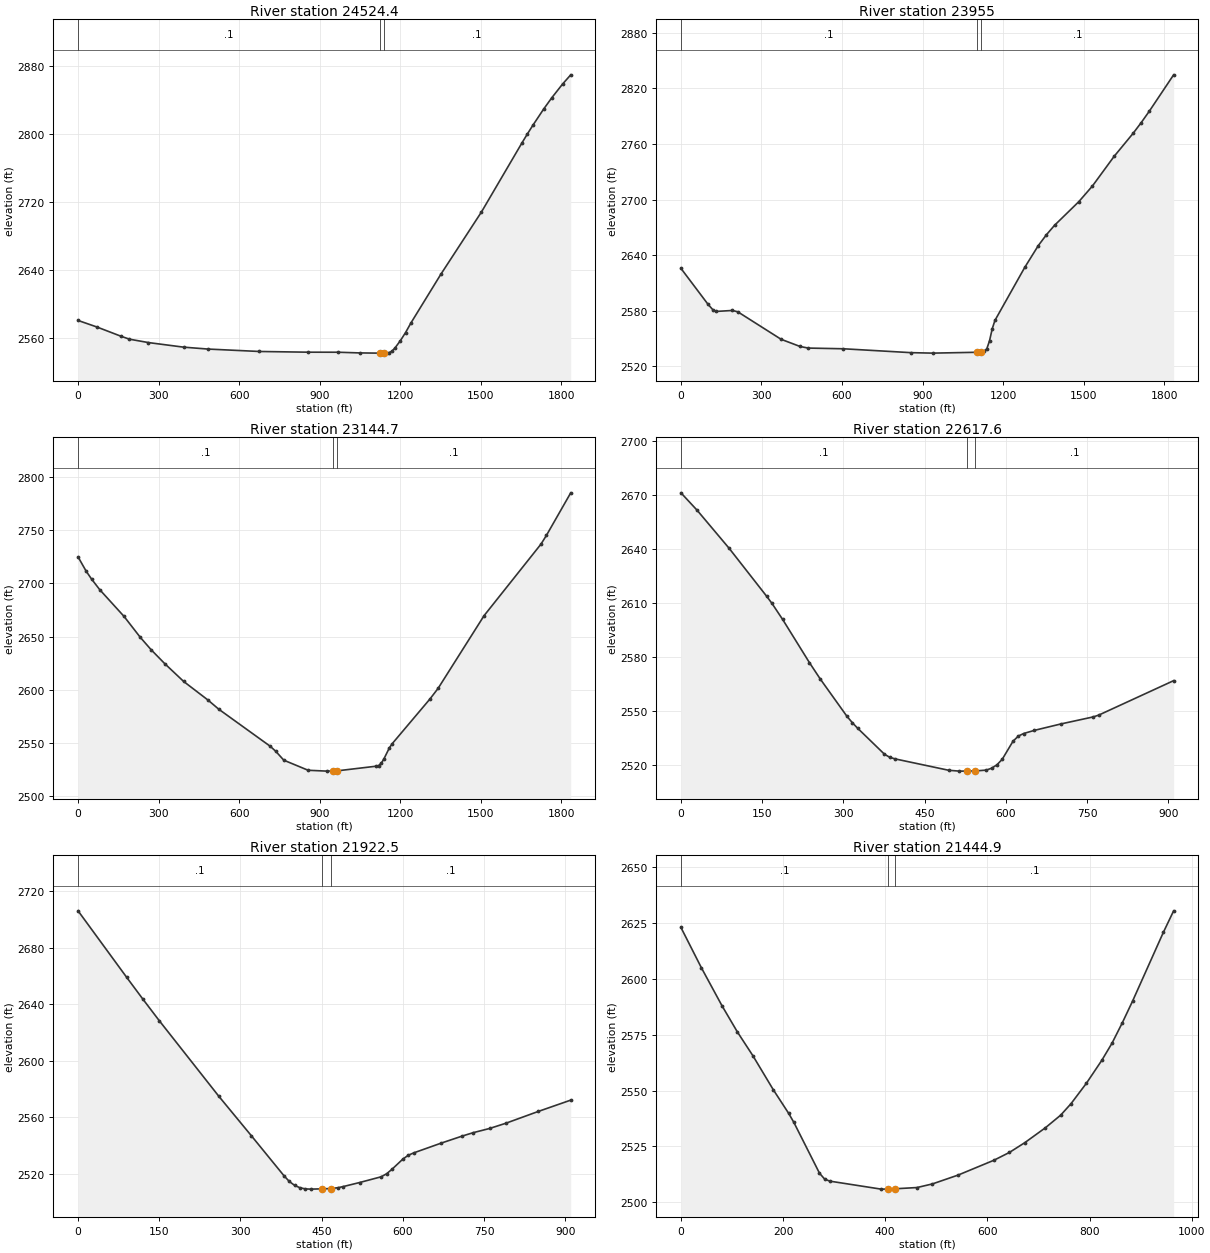
Type RM Length L Ch R = 1 ,24524.4 ,579.6,569.4,559.2
XS GIS Cut Line= 2
     2120149.847      431423.191     2121922.862      431896.496
#Sta/Elev= 30
       0 2580.41    70.6 2572.67   161.3 2561.68   191.6 2558.38   262.2  2554.4
   393.2 2549.01     484 2546.77   675.6 2543.93     857 2543.09     968 2543.05
  1048.6 2542.24  1119.2 2541.99  1123.4    2542  1138.4 2542.01  1149.5 2542.07
  1159.5 2542.62  1169.6 2544.46  1179.7 2547.76  1199.9 2556.34    1220 2566.24
  1240.2 2577.64  1351.1  2634.6  1502.4 2707.86  1653.6 2789.25  1673.8 2799.74
  1693.9 2809.78  1734.3 2828.95  1764.5 2842.21  1804.8 2858.37  1835.1 2869.17
#Mann= 3 , 0 , 0
       0      .1       0  1123.4    .045       0  1138.4      .1       0
Bank Sta=1123.4,1138.4
XS Rating Curve= 0 ,0
Exp/Cntr=0.3,0.1

Type RM Length L Ch R = 1 ,23955   ,816.1,810.3,804.5
XS GIS Cut Line= 2
     2120119.031      432478.408     2121921.266      432132.649
#Sta/Elev= 30
       0  2625.7   100.8 2586.92     121 2580.34   131.1  2579.2   191.6 2580.25
   211.7 2578.79   373.1 2549.12   443.6 2541.38   473.9 2539.65     605 2538.89
     857  2534.7   937.7 2534.19  1104.3 2535.12  1119.3 2535.43  1129.3 2536.11
  1139.4 2538.94  1149.5 2547.64  1159.5 2560.54  1169.6 2569.54  1280.5 2626.72
    1331 2650.26  1361.2 2661.95  1391.4 2672.13  1482.2 2697.78  1532.6 2714.59
  1613.3 2746.55  1683.9 2771.37  1714.1 2782.94  1744.4 2795.33  1835.1 2834.64
#Mann= 3 , 0 , 0
       0      .1       0  1104.3    .045       0  1119.3      .1       0
Bank Sta=1104.3,1119.3
XS Rating Curve= 0 ,0
Exp/Cntr=0.3,0.1

Type RM Length L Ch R = 1 ,23144.7 ,525.8,527.1,528.4
XS GIS Cut Line= 2
     2120521.663      433469.437     2122177.978       432679.36
#Sta/Elev= 30
       0    2725    30.2 2711.54    50.4 2704.11    80.7 2694.15   171.4 2668.92
   231.9  2649.2   272.2 2637.56   322.7  2624.5   393.2 2607.71     484 2590.15
   524.3  2581.5   715.9 2546.61   736.1 2541.96   766.3 2533.53     857 2524.02
   927.6 2523.21   949.8 2523.33   964.8 2523.47  1109.1 2527.81  1119.2 2528.45
  1129.3 2530.59  1139.4  2534.8  1159.5 2545.09  1169.6  2548.9  1310.8 2591.19
    1341 2601.14  1512.4 2669.69  1724.2 2737.02  1744.4  2745.2  1835.1 2785.35
#Mann= 3 , 0 , 0
       0      .1       0   949.8    .045       0   964.8      .1       0
Bank Sta=949.8,964.8
XS Rating Curve= 0 ,0
Exp/Cntr=0.3,0.1

Type RM Length L Ch R = 1 ,22617.6 ,699.8,695.1,690.4
XS GIS Cut Line= 3
     2121139.346      433708.211     2121560.766       433536.66
     2121982.186      433365.108
#Sta/Elev= 30
       0 2671.36    29.7 2661.72      89 2640.47   158.3 2613.76   168.2 2609.76
   187.9 2600.82   237.4 2576.77   257.2 2567.74   306.6 2546.91   316.5 2543.38
   326.4 2540.26   375.9  2525.8   385.8 2524.05   395.6 2523.19   494.6 2516.85
   514.4 2516.38   528.1  2516.4   543.1 2516.48   563.8 2516.94   573.7    2518
   583.6 2519.88   593.5 2523.01   613.3 2533.01   623.2  2535.9     633 2537.33
   652.8 2539.08   702.3 2542.69   761.6 2546.58   771.5 2547.56     910 2566.76
#Mann= 3 , 0 , 0
       0      .1       0   528.1    .045       0   543.1      .1       0
Bank Sta=528.1,543.1
XS Rating Curve= 0 ,0
Exp/Cntr=0.3,0.1

Type RM Length L Ch R = 1 ,21922.5 ,474,477.6,481.2
XS GIS Cut Line= 2
     2121518.637      434400.673      2122273.41      433892.324
#Sta/Elev= 30
       0    2706      90 2658.84     120 2643.39     150 2628.28     260  2574.8
     320 2546.92     380 2518.73     390  2514.6     400 2511.74     410 2510.06
     420 2509.25     430  2509.1   451.4 2509.31   466.4  2509.5     480  2510.1
     490 2510.93     520 2513.77     560 2517.85     570    2520     580  2523.2
     600 2530.39     610 2533.07     620 2534.75     670 2541.56     710  2546.7
     730 2549.06     760    2552     790 2555.69     850 2564.06     910 2572.07
#Mann= 3 , 0 , 0
       0      .1       0   451.4    .045       0   466.4      .1       0
Bank Sta=451.4,466.4
XS Rating Curve= 0 ,0
Exp/Cntr=0.3,0.1

Type RM Length L Ch R = 1 ,21444.9 ,519.7,519.8,519.4
XS GIS Cut Line= 2
     2121809.088      434704.814     2122675.751       434281.08
#Sta/Elev= 30
       0 2623.03    40.2 2604.92    80.4 2587.98   110.5 2576.26   140.7 2565.68
   180.9 2550.36     211 2539.79   221.1 2535.76   271.3 2513.02   281.4 2510.38
   291.4 2509.47   391.9 2505.89     405 2505.91     420 2506.05   462.2  2506.6
   492.4 2508.22   542.6 2512.17     613 2518.84   643.1 2522.31   673.3 2526.69
   713.5 2533.34   743.6 2539.02   763.7 2544.12   793.9 2553.28     824 2563.53
   844.1 2571.24   864.2 2580.35   884.3 2590.06   944.6 2620.85   964.7 2630.48
#Mann= 3 , 0 , 0
       0      .1       0     405    .045       0     420      .1       0
Bank Sta=405,420
XS Rating Curve= 0 ,0
Exp/Cntr=0.3,0.1

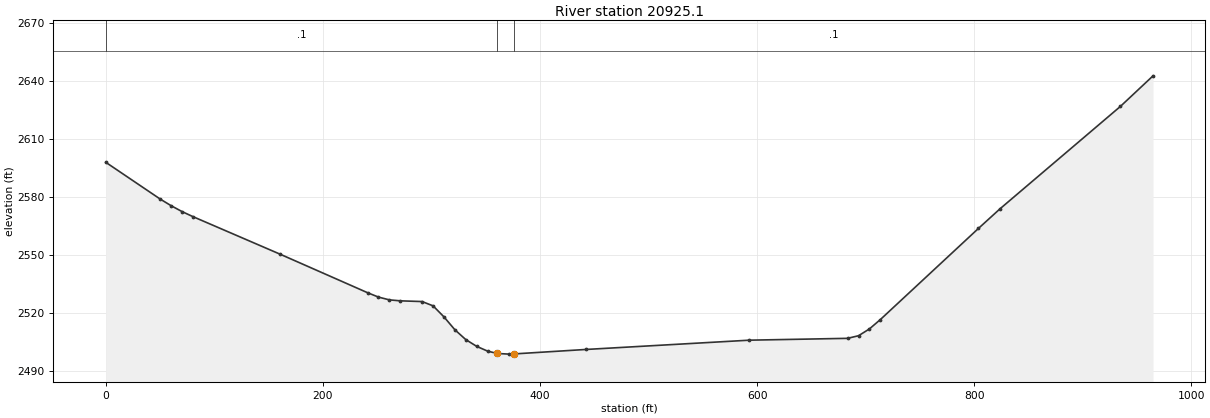
Type RM Length L Ch R = 1 ,20925.1 ,276.9,275.2,273.6
XS GIS Cut Line= 2
     2121982.368      435107.661     2122849.031      434683.926
#Sta/Elev= 30
       0 2597.87    50.2 2578.82    60.3 2575.38    70.3 2572.36    80.4 2569.73
   160.8 2550.27   241.2 2530.38   251.2 2528.12   261.3 2526.68   271.3 2526.19
   291.4 2525.81   301.5 2523.59   311.5 2517.89   321.6  2511.2   331.6 2506.14
   341.7 2502.62   351.7 2500.17   360.6 2498.94   371.8 2498.61   375.6  2498.7
   442.2 2501.02   592.9 2505.83   683.3 2506.78   693.4 2508.13   703.4 2511.64
   713.5 2516.49   803.9 2563.68     824 2573.94   934.6 2626.78   964.7 2642.62
#Mann= 3 , 0 , 0
       0      .1       0   360.6    .045       0   375.6      .1       0
Bank Sta=360.6,375.6
XS Rating Curve= 0 ,0
Exp/Cntr=0.3,0.1