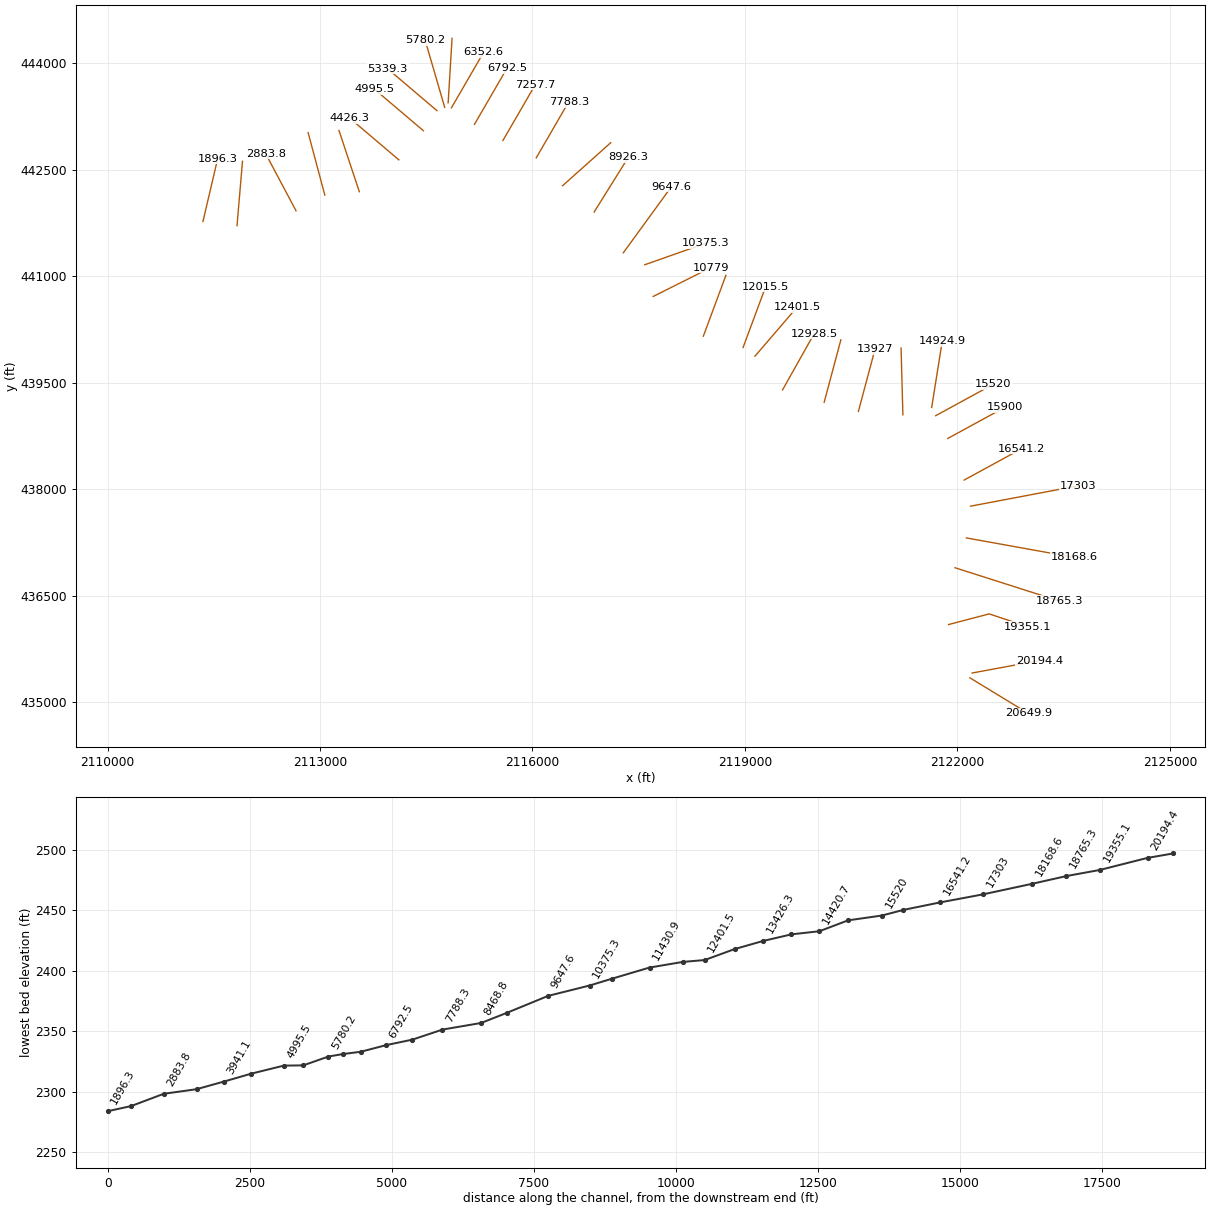
HEC-RAS study SFrkChryRv.prj: SFrkChryRv

--- SFrkChryRv.g01 (geometry) --- (continued)

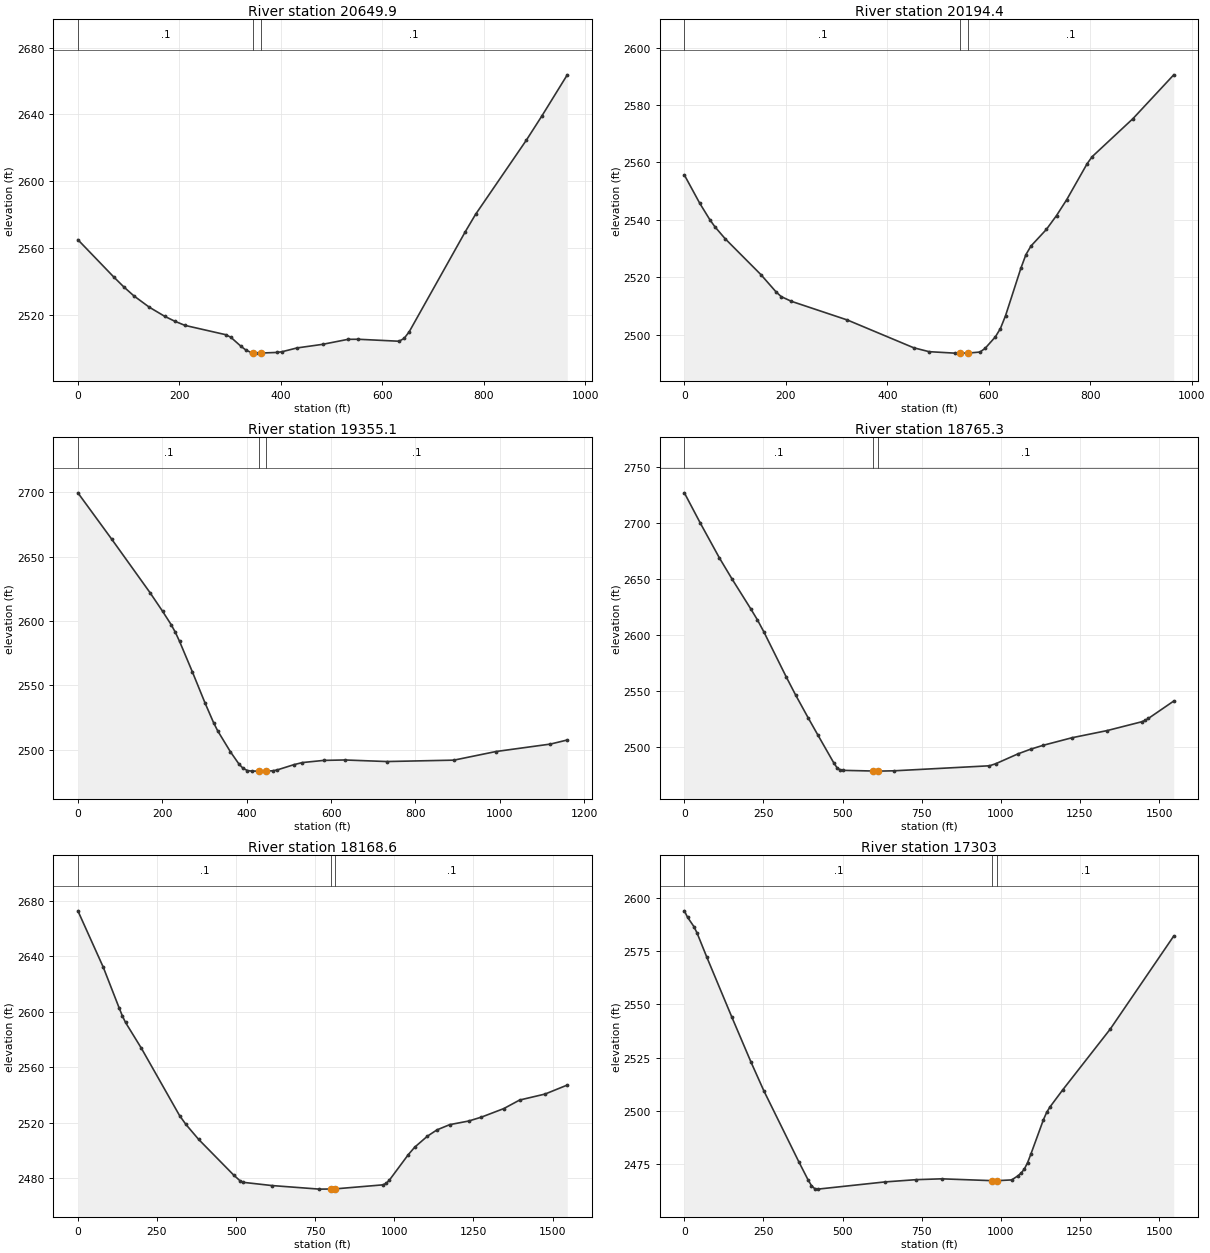
Type RM Length L Ch R = 1 ,20649.9 ,438.7,455.5,472.2
XS GIS Cut Line= 2
     2122175.029      435344.516     2122999.238      434843.183
#Sta/Elev= 30
       0 2565.07    70.3  2542.9    90.4 2536.87   110.5 2531.44   140.7 2524.71
   170.8  2519.3   190.9 2516.32     211 2513.82   291.4 2508.25   301.5  2506.7
   321.6 2501.28   331.6 2498.97   341.7 2497.59   346.1 2497.43   351.7 2497.22
   361.1 2497.27   391.9 2497.63     402 2498.03   432.1 2500.33   482.4 2502.48
   532.6 2505.48   552.7 2505.52   633.1 2504.33   643.1 2506.04   653.2 2510.04
   763.7 2569.87   783.8 2580.18   884.3 2624.74   914.5 2639.03   964.7  2663.7
#Mann= 3 , 0 , 0
       0      .1       0   346.1    .045       0   361.1      .1       0
#XS Ineff= 2 , 0
                          536.76         2505.26
Permanent Ineff=
       F       F
Bank Sta=346.1,361.1
XS Rating Curve= 0 ,0
Exp/Cntr=0.3,0.1

Type RM Length L Ch R = 1 ,20194.4 ,837.5,839.2,841
XS GIS Cut Line= 2
     2122207.351      435411.709     2123155.964      435587.174
#Sta/Elev= 30
       0 2555.62    30.2  2545.8    50.2 2540.04    60.3 2537.54    80.4  2533.4
   150.7 2520.92   180.9 2514.84   190.9 2513.22     211 2511.58   321.6 2505.05
   452.2 2495.38   482.4 2494.03   532.6 2493.52   543.9 2493.53   558.9 2493.53
   582.8  2493.9   592.9 2495.19     613 2499.17     623 2502.08   633.1 2506.55
   663.2 2523.02   673.3 2527.85   683.3 2530.86   713.5 2536.61   733.6 2541.46
   753.7    2547   793.9 2559.52   803.9    2562   884.3 2575.25   964.7 2590.52
#Mann= 3 , 0 , 0
       0      .1       0   543.9    .045       0   558.9      .1       0
Bank Sta=543.9,558.9
XS Rating Curve= 0 ,0
Exp/Cntr=0.3,0.1

Type RM Length L Ch R = 1 ,19355.1 ,602.7,589.9,577.1
XS GIS Cut Line= 3
     2121874.463      436094.204     2122447.651      436244.584
     2122985.968      436065.872
#Sta/Elev= 30
       0 2699.48    80.4 2663.42   170.8  2622.1   200.9 2607.49     221 2597.21
     231 2591.25     241  2584.2   271.2 2560.65   301.3 2536.45   321.4 2521.27
   331.4 2514.75   361.6  2498.5   381.7 2489.05   391.7 2485.64   401.8    2484
   411.8 2483.57   429.7 2483.55   441.9 2483.54   444.7 2483.54     462 2483.82
   472.1 2484.45   512.2 2488.58   532.3  2490.2   582.5 2491.86   632.4  2492.2
   731.9 2490.98   891.1 2492.06   990.6 2498.74    1120 2504.54  1159.8  2507.7
#Mann= 3 , 0 , 0
       0      .1       0   429.7    .045       0   444.7      .1       0
Bank Sta=429.7,444.7
XS Rating Curve= 0 ,0
Exp/Cntr=0.3,0.1

Type RM Length L Ch R = 1 ,18765.3 ,593.2,596.7,600.1
XS GIS Cut Line= 2
     2121965.491      436894.661      2123439.16      436425.638
#Sta/Elev= 30
       0    2727    50.2 2700.09   110.5 2669.01   150.6  2650.1   210.9 2622.92
     231 2613.49   251.1 2602.93   321.4 2562.94   351.5 2546.53   391.6 2525.89
   421.8 2510.79     472 2485.95     482  2481.7   492.1 2479.59   502.1 2479.16
   595.6 2478.57   602.5 2478.47   610.6 2478.47   662.8 2478.76   964.1 2483.24
   984.1 2485.09  1054.4  2493.9  1094.6  2498.1  1134.8  2501.6  1225.2  2508.3
  1335.6 2514.65  1446.1  2522.6  1456.1 2523.81  1466.2 2525.49  1546.5 2541.05
#Mann= 3 , 0 , 0
       0      .1       0   595.6    .045       0   610.6      .1       0
Bank Sta=595.6,610.6
XS Rating Curve= 0 ,0
Exp/Cntr=0.3,0.1

Type RM Length L Ch R = 1 ,18168.6 ,858.2,865.6,873.1
XS GIS Cut Line= 2
     2122126.255       437314.47     2123648.412      437041.118
#Sta/Elev= 30
       0 2672.81    80.3  2632.1   130.6 2602.67   140.6 2597.01   150.6 2592.29
   200.8 2573.66   321.4 2525.14   341.4 2518.78   381.6 2507.99   492.1 2482.33
   512.2  2478.2   522.2 2477.04   612.6 2474.72   763.2 2472.13   798.7 2472.22
   813.7 2472.32   964.1 2475.22   974.1 2476.28   984.1 2478.54  1044.4 2497.09
  1064.5  2502.4  1104.6 2510.33  1134.8 2514.86  1174.9 2518.62  1235.2 2521.25
  1275.4 2524.07  1345.7 2530.19  1395.9 2536.37  1476.2 2540.68  1546.5 2547.18
#Mann= 3 , 0 , 0
       0      .1       0   798.7    .045       0   813.7      .1       0
Bank Sta=798.7,813.7
XS Rating Curve= 0 ,0
Exp/Cntr=0.3,0.1

Type RM Length L Ch R = 1 ,17303   ,754.9,761.8,768.7
XS GIS Cut Line= 2
     2122184.186      437761.807     2123703.823      438048.842
#Sta/Elev= 30
       0 2593.76      10 2590.78    30.1 2586.39    40.2 2583.36    70.3  2572.3
   150.6 2543.79   210.9 2522.79   251.1 2509.48   361.5 2476.25   391.6 2467.52
   401.7 2465.01   411.7 2463.61   421.8 2463.37   632.7 2466.73   733.1 2467.81
   813.4  2468.2   973.2 2467.33   988.2 2467.33  1034.4 2467.69  1054.4 2469.62
  1064.5 2470.94  1074.5 2472.81  1084.6 2475.77  1094.6  2479.6  1134.8 2495.93
  1144.8 2499.28  1154.9 2501.77    1195 2509.75  1345.7 2538.33  1546.5 2581.95
#Mann= 3 , 0 , 0
       0      .1       0   973.2    .045       0   988.2      .1       0
Bank Sta=973.2,988.2
XS Rating Curve= 0 ,0
Exp/Cntr=0.3,0.1

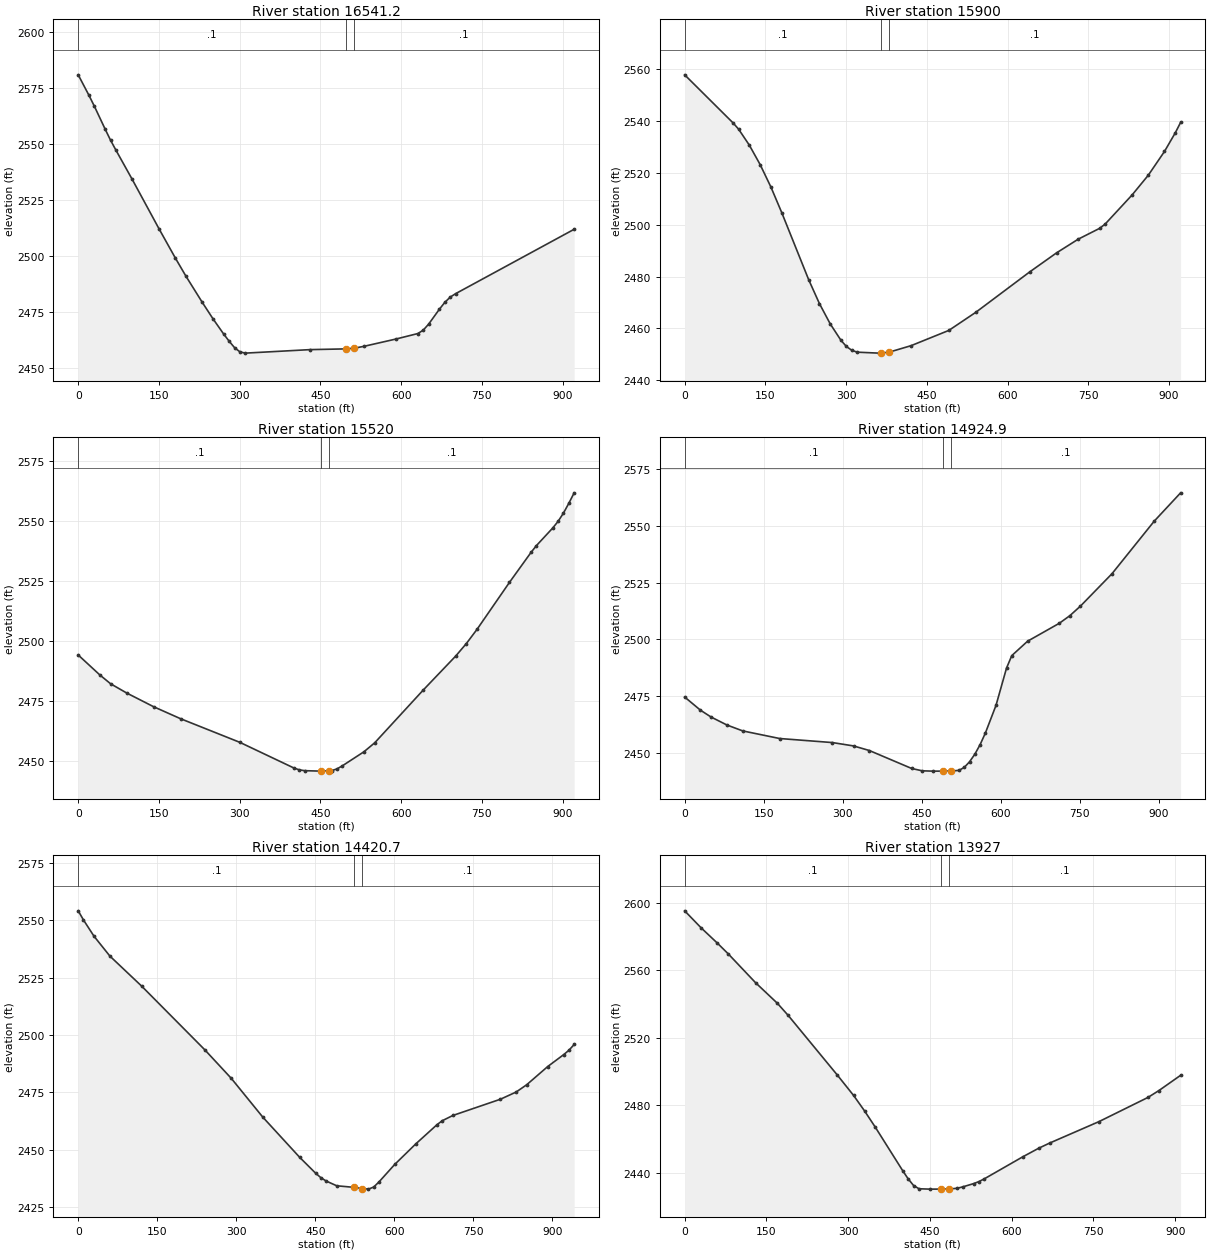
Type RM Length L Ch R = 1 ,16541.2 ,640.9,641.2,641.5
XS GIS Cut Line= 2
     2122094.528      438129.624     2122903.828      438570.318
#Sta/Elev= 30
       0 2580.75      20 2571.59      30 2566.75    50.1  2556.5    60.1 2551.59
    70.1 2547.15   100.2 2534.19   150.2 2512.07   180.3 2499.13   200.3 2490.91
   230.4 2479.33   250.4 2471.97   270.4 2465.12   280.5 2461.95   290.5 2459.09
   300.5 2457.21   310.5 2456.65   430.7 2458.21   496.7 2458.54   511.7  2458.8
   530.9 2459.68     591 2462.97     631 2465.38     641 2466.88   651.1 2469.57
   671.1 2476.23   681.1 2479.26   691.1 2481.61   701.2 2483.16   921.5 2511.88
#Mann= 3 , 0 , 0
       0      .1       0   496.7    .045       0   511.7      .1       0
Bank Sta=496.7,511.7
XS Rating Curve= 0 ,0
Exp/Cntr=0.3,0.1

Type RM Length L Ch R = 1 ,15900   ,380.2,380,379.9
XS GIS Cut Line= 2
     2121863.136      438715.481     2122672.436      439156.174
#Sta/Elev= 30
       0 2557.83    90.2 2539.22   100.2 2536.87   120.2 2530.68   140.2 2523.22
   160.3 2514.52   180.3 2504.71   230.4 2478.81   250.4 2469.59   270.4 2461.78
   290.5  2455.4   300.5 2453.05   310.5 2451.59   320.5 2450.86   360.6 2450.49
   363.9 2450.52   378.9  2450.8   420.7 2453.37   490.8 2459.25   540.9 2466.23
     641  2481.8   691.1 2489.18   731.2 2494.44   771.3 2498.65   781.3 2500.27
   831.4 2511.51   861.4  2519.1   891.5 2528.27   911.5 2535.43   921.5 2539.48
#Mann= 3 , 0 , 0
       0      .1       0   363.9    .045       0   378.9      .1       0
Bank Sta=363.9,378.9
XS Rating Curve= 0 ,0
Exp/Cntr=0.3,0.1

Type RM Length L Ch R = 1 ,15520   ,573.9,595.1,616.2
XS GIS Cut Line= 2
     2121692.097      439036.028     2122501.397      439476.721
#Sta/Elev= 30
       0 2494.14    40.1 2485.86    60.1 2482.18    90.2 2478.31   140.2 2472.61
   190.3 2467.62   300.5 2457.78   400.7 2447.13   410.7 2446.36   420.7 2446.01
   450.7 2445.82   450.9 2445.82   465.9 2445.94   470.8 2446.02   480.8 2446.74
   490.8 2448.03   530.9 2453.87   550.9  2457.6     641 2479.54   701.2 2493.65
   721.2  2498.9   741.2 2504.87   801.3 2524.36   841.4 2536.84   851.4 2539.66
   881.4 2546.91   891.5  2549.7   901.5 2553.14   911.5 2557.22   921.5 2561.62
#Mann= 3 , 0 , 0
       0      .1       0   450.9    .045       0   465.9      .1       0
Bank Sta=450.9,465.9
XS Rating Curve= 0 ,0
Exp/Cntr=0.3,0.1

Type RM Length L Ch R = 1 ,14924.9 ,500,504.2,508.4
XS GIS Cut Line= 2
     2121636.161      439153.175     2121784.922      440082.546
#Sta/Elev= 30
       0 2474.52      30 2468.71    50.1  2465.7    80.1 2462.19   110.1 2459.58
   180.2 2456.22   280.4 2454.43   320.4 2452.95   350.4 2450.93   430.6 2443.02
   450.6 2441.97   470.6 2441.83   489.5 2441.83   504.5 2441.84   520.7 2442.17
   530.7  2443.5   540.7 2445.98   550.7 2449.31   560.7 2453.53   570.7 2458.66
   590.8 2470.82   610.8 2487.29   620.8  2492.8   650.8 2499.16   710.9 2507.05
   730.9  2510.4     751 2514.62     811 2528.94   891.1 2552.12   941.2 2564.62
#Mann= 3 , 0 , 0
       0      .1       0   489.5    .045       0   504.5      .1       0
Bank Sta=489.5,504.5
XS Rating Curve= 0 ,0
Exp/Cntr=0.3,0.1

Type RM Length L Ch R = 1 ,14420.7 ,500.2,493.7,487.2
XS GIS Cut Line= 2
     2121229.634       439048.83     2121204.018      439989.682
#Sta/Elev= 30
       0  2554.2      10 2550.21      30 2543.12    60.1 2534.47   120.2 2521.41
   240.3 2493.58   290.4 2481.17   350.4 2464.21   420.5 2446.66   450.6 2439.78
   460.6 2437.82   470.6 2436.37   490.6  2434.3   524.2  2433.6   539.2 2433.11
   550.7 2432.84   560.7 2433.74   570.7 2435.95   600.8 2443.64   640.8  2452.6
   680.9 2460.94   690.9 2462.67   710.9 2464.95     801 2472.02   831.1 2475.18
   851.1 2478.35   891.1 2486.31   921.2 2491.47   931.2 2493.38   941.2 2495.91
#Mann= 3 , 0 , 0
       0      .1       0   524.2    .045       0   539.2      .1       0
Bank Sta=524.2,539.2
XS Rating Curve= 0 ,0
Exp/Cntr=0.3,0.1

Type RM Length L Ch R = 1 ,13927   ,500.7,500.7,500.7
XS GIS Cut Line= 2
     2120601.408      439096.783     2120836.887      439975.788
#Sta/Elev= 30
       0 2595.19      30 2585.16      60 2576.04      80 2569.66     130 2552.61
     170 2540.42     190 2533.17     280 2497.88     310 2485.73     330 2476.62
     350 2466.83     400 2441.19     410 2436.35     420 2432.38     430 2430.44
     450 2430.23   470.7 2430.25   485.7  2430.3     500 2430.74     510 2431.54
     530 2433.48     540 2434.71     550 2436.37     620 2449.32     650 2454.54
     670 2457.58     760 2470.22     850 2484.57     870 2488.62     910  2497.7
#Mann= 3 , 0 , 0
       0      .1       0   470.7    .045       0   485.7      .1       0
Bank Sta=470.7,485.7
XS Rating Curve= 0 ,0
Exp/Cntr=0.3,0.1

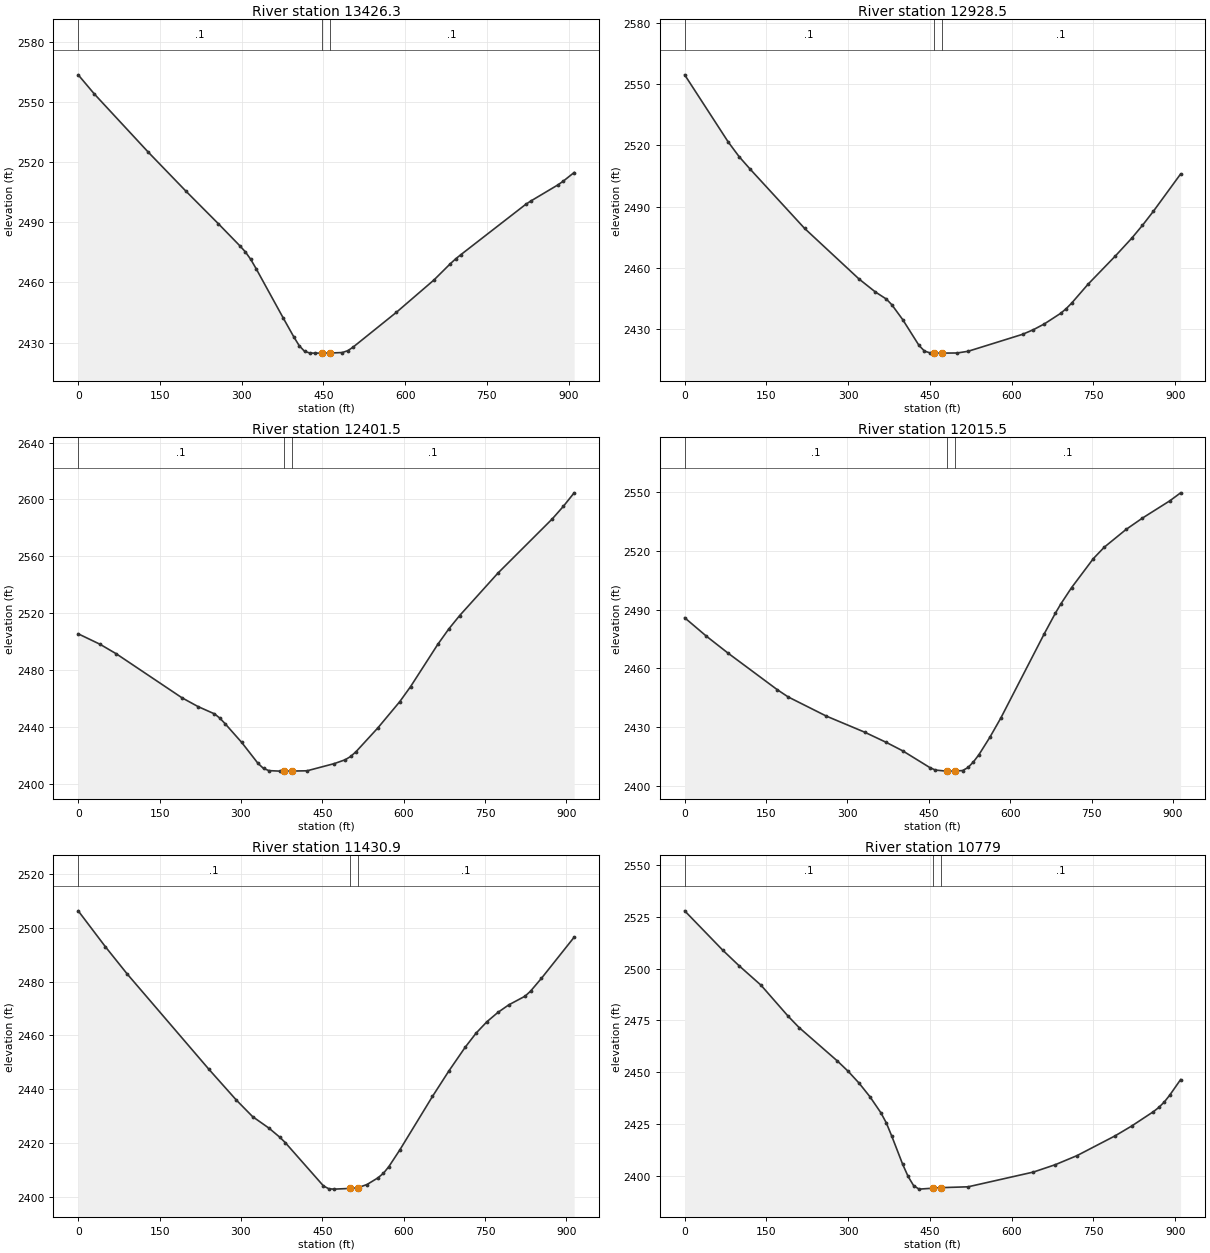
Type RM Length L Ch R = 1 ,13426.3 ,503.5,497.8,492.1
XS GIS Cut Line= 3
     2120118.439      439226.167     2120236.178      439665.669
     2120353.917      440105.172
#Sta/Elev= 30
       0  2563.5    29.7 2553.92   128.6 2524.93   197.8 2505.46   257.2 2489.25
   296.7 2478.22   306.6 2475.26   316.5 2471.52   326.4 2466.88   375.9  2442.4
   395.6 2432.84   405.5 2428.46   415.4 2425.62   425.3 2424.77   435.2 2424.74
   447.5 2424.75   462.5 2424.79   484.7 2425.04   494.6 2425.95   504.5 2427.76
   583.6 2445.04   652.8 2461.22   682.5 2469.24   692.4  2471.7   702.3 2473.87
     821 2498.89   830.9 2500.65   880.3 2508.64   890.2 2510.53     910  2514.8
#Mann= 3 , 0 , 0
       0      .1       0   447.5    .045       0   462.5      .1       0
Bank Sta=447.5,462.5
XS Rating Curve= 0 ,0
Exp/Cntr=0.3,0.1

Type RM Length L Ch R = 1 ,12928.5 ,531.4,527,522.6
XS GIS Cut Line= 2
     2119529.849      439398.649     2119976.567      440191.457
#Sta/Elev= 30
       0 2554.62      80 2521.63     100 2514.44     120 2508.39     220 2479.28
     320 2454.42     350 2448.06     370 2444.61     380 2441.84     400 2434.54
     430 2421.84     440 2419.08     450 2418.21   456.9 2418.11     460 2418.07
   471.9 2418.08     500 2418.14     520 2418.97     620  2427.3     640 2429.59
     660 2432.41     690 2437.62     700 2439.88     710 2442.59     740 2451.84
     790 2465.66     820 2474.36     840 2480.78     860 2487.66     910 2505.97
#Mann= 3 , 0 , 0
       0      .1       0   456.9    .045       0   471.9      .1       0
Bank Sta=456.9,471.9
XS Rating Curve= 0 ,0
Exp/Cntr=0.3,0.1

Type RM Length L Ch R = 1 ,12401.5 ,378,386,394.1
XS GIS Cut Line= 2
     2119141.159      439874.698     2119737.611      440567.504
#Sta/Elev= 30
       0 2505.55    40.2  2498.2    70.3 2491.47   190.9 2460.65     221 2454.36
   251.2 2449.26   261.2 2446.22   271.2 2442.17   301.4 2429.16   331.5 2414.41
   341.6 2410.88   351.6 2409.34   371.7 2408.99   378.7 2409.03   393.7 2409.03
   421.9 2409.23   472.2  2414.3   492.2    2417   502.3 2419.32   512.4 2422.78
   552.5 2439.45   592.7 2457.83   612.8  2468.5     663 2498.24   683.1 2508.96
   703.2 2518.41   773.5 2548.16     874 2586.41   894.1  2595.1   914.2 2604.69
#Mann= 3 , 0 , 0
       0      .1       0   378.7    .045       0   393.7      .1       0
Bank Sta=378.7,393.7
XS Rating Curve= 0 ,0
Exp/Cntr=0.3,0.1

Type RM Length L Ch R = 1 ,12015.5 ,584.6,584.6,584.6
XS GIS Cut Line= 2
      2118973.64      439997.757     2119292.165      440854.656
#Sta/Elev= 30
       0 2485.86    40.2 2476.39    80.4 2467.67   170.8 2449.05   190.9 2445.35
   261.2 2435.56   331.5 2427.38   371.7 2422.12   401.8 2417.82   452.1 2409.22
   462.1 2407.98   482.2 2407.43   482.7 2407.43   497.7 2407.44   512.4 2407.74
   522.4  2409.3   532.4  2412.2   542.5 2415.88   562.6 2424.76   582.7 2434.55
     663 2477.75   683.1 2488.07   693.2 2492.84   713.3  2501.3   753.4 2516.12
   773.5 2521.94   813.7 2531.02   843.9 2536.83   894.1 2545.61   914.2 2549.73
#Mann= 3 , 0 , 0
       0      .1       0   482.7    .045       0   497.7      .1       0
Bank Sta=482.7,497.7
XS Rating Curve= 0 ,0
Exp/Cntr=0.3,0.1

Type RM Length L Ch R = 1 ,11430.9 ,669.7,651.9,634
XS GIS Cut Line= 2
     2118412.294      440156.523     2118730.819      441013.422
#Sta/Elev= 30
       0 2506.41    50.2 2493.01    90.4 2482.87   241.1 2447.35   291.3 2435.97
   321.5 2429.76   351.6 2425.48   371.7 2422.08   381.8 2420.06   452.1 2403.95
   462.1 2402.88   472.2 2402.76   500.1 2403.01   515.1 2403.26   532.4 2404.48
   552.5 2406.96   562.6 2408.66   572.6 2411.14   592.7 2417.32     653 2437.28
   683.1 2446.72   713.3 2455.59   733.4 2460.85   753.4 2465.11   773.5 2468.55
   793.6 2471.38   823.8 2474.63   833.8 2476.49   853.9 2481.27   914.2 2496.59
#Mann= 3 , 0 , 0
       0      .1       0   500.1    .045       0   515.1      .1       0
Bank Sta=500.1,515.1
XS Rating Curve= 0 ,0
Exp/Cntr=0.3,0.1

Type RM Length L Ch R = 1 ,10779   ,406.6,403.7,400.8
XS GIS Cut Line= 2
     2117704.477      440716.102     2118518.611      441122.655
#Sta/Elev= 30
       0 2527.86      70 2508.85     100 2501.34     140 2492.02     190 2477.01
     210 2471.57     280 2455.51     300 2450.49     320 2444.79     340 2438.21
     360  2430.5     370  2425.6     380 2419.23     400 2405.65     410 2399.78
     420  2395.4     430 2393.68   455.2 2394.12   470.2 2394.39     520  2394.8
     640 2401.92     680 2405.46     720 2409.85     790  2419.4     820 2424.08
     860 2431.01     870 2433.07     880 2435.68     890 2438.98     910 2446.51
#Mann= 3 , 0 , 0
       0      .1       0   455.2    .045       0   470.2      .1       0
Bank Sta=455.2,470.2
XS Rating Curve= 0 ,0
Exp/Cntr=0.3,0.1

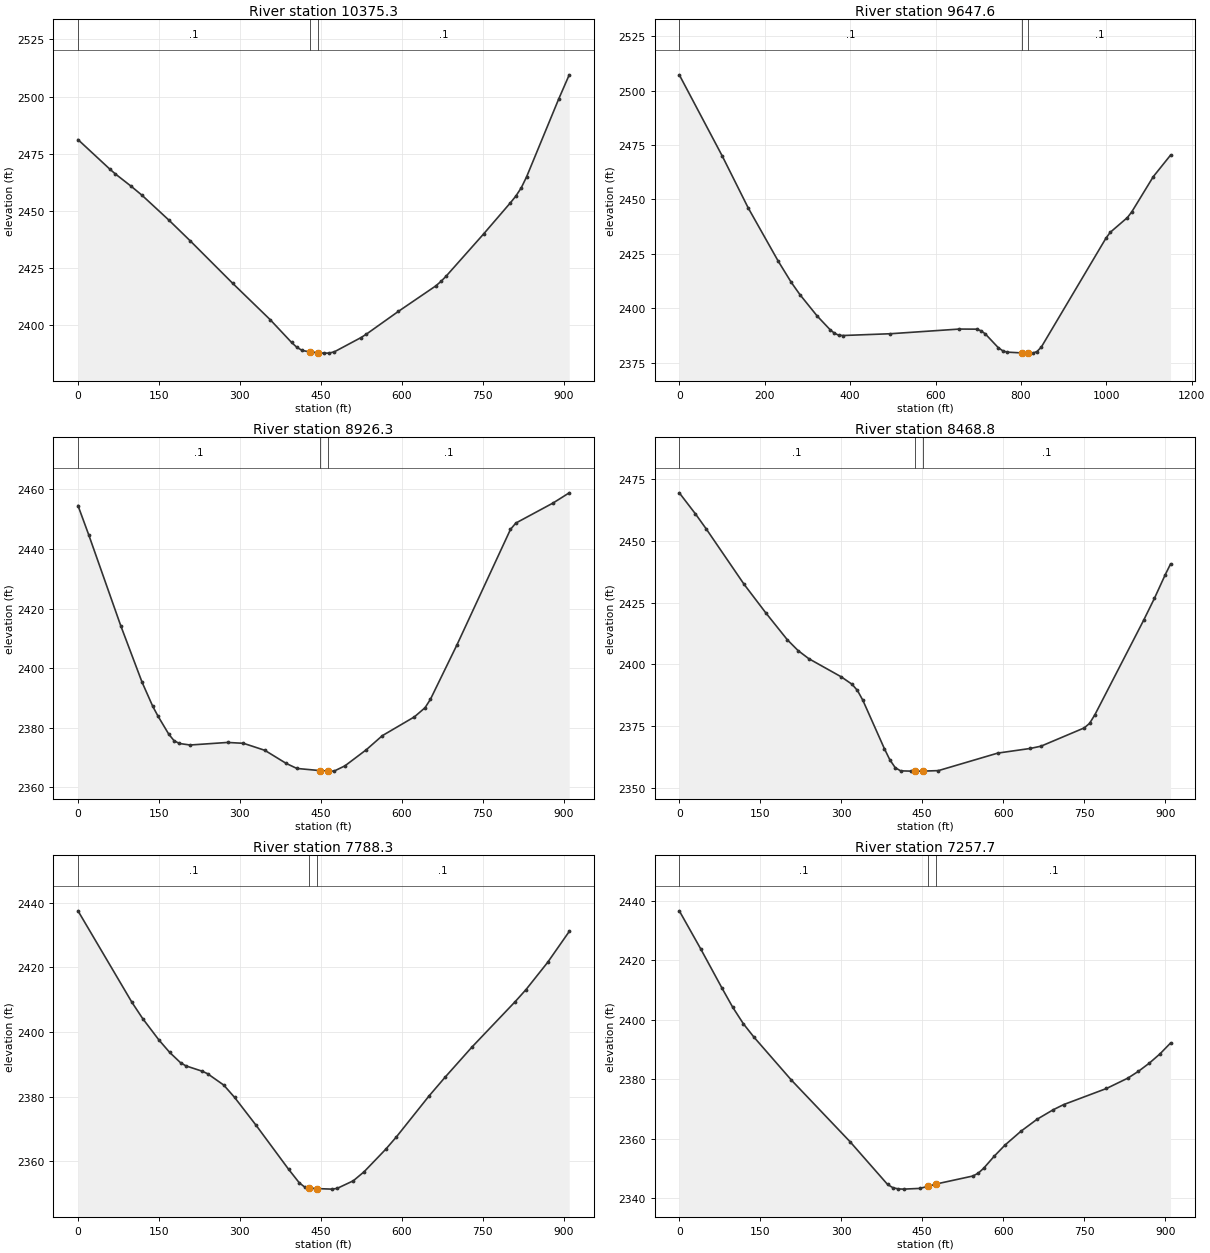
Type RM Length L Ch R = 1 ,10375.3 ,713.7,727.8,741.8
XS GIS Cut Line= 3
     2117586.051       441163.08     2118015.333      441313.886
     2118444.614      441464.691
#Sta/Elev= 30
       0 2481.18    59.4 2468.19    69.2 2466.19    98.9 2460.72   118.7 2456.84
   168.2 2446.05   207.7    2437   286.8 2418.34   356.1  2402.5   395.6 2392.58
   405.5 2390.43   415.4 2389.06   429.6 2388.44   444.6  2388.1     455  2387.9
   464.9 2387.91   474.8 2388.46   524.2 2394.68   534.1 2396.17   593.5 2406.13
   662.7 2417.25   672.6 2419.26   682.5 2421.66   751.7 2440.04   801.2 2453.62
   811.1  2456.5     821 2460.07   830.9 2464.85   890.2 2498.75     910 2509.47
#Mann= 3 , 0 , 0
       0      .1       0   429.6    .045       0   444.6      .1       0
Bank Sta=429.6,444.6
XS Rating Curve= 0 ,0
Exp/Cntr=0.3,0.1

Type RM Length L Ch R = 1 ,9647.6  ,719.5,721.2,723
XS GIS Cut Line= 2
     2117281.949      441330.658     2117960.148       442259.94
#Sta/Elev= 30
       0 2507.31   100.9 2469.87   161.5 2446.07   232.1 2421.49   262.4 2411.83
   282.6 2406.22   322.9 2396.41   353.2 2390.11   363.3  2388.5   373.4 2387.57
   383.5 2387.44   494.5 2388.26     656 2390.41   696.3 2390.36   706.4 2389.64
   716.5  2388.2   746.8 2381.89   756.9 2380.49     767 2379.81   801.6 2379.44
   816.6 2379.36   827.5 2379.34   837.6 2380.07   847.7  2382.1   999.1 2432.19
  1009.2 2434.89  1049.5  2441.7  1059.6  2444.3  1110.1 2460.52  1150.4 2470.38
#Mann= 3 , 0 , 0
       0      .1       0   801.6    .045       0   816.6      .1       0
Bank Sta=801.6,816.6
XS Rating Curve= 0 ,0
Exp/Cntr=0.3,0.1

Type RM Length L Ch R = 1 ,8926.3  ,464,457.6,451.1
XS GIS Cut Line= 3
     2116870.463      441905.096     2117111.798      442290.819
     2117353.133      442676.542
#Sta/Elev= 30
       0 2454.59    19.8 2444.81    79.1 2414.31   118.7 2395.28   138.5 2387.18
   148.4 2383.83   168.2 2377.82     178 2375.64   187.9  2374.7   207.7 2374.19
     277 2375.05   306.6 2374.76   346.2  2372.4   385.8    2368   405.5 2366.32
   447.5 2365.61   462.5 2365.44   464.9 2365.42   474.8 2365.46   494.6  2367.2
   534.1  2372.6   563.8 2377.33   623.2 2383.64   642.9 2386.71   652.8 2389.51
   702.3 2407.92   801.2  2446.6   811.1 2448.71   880.3 2455.47     910 2458.86
#Mann= 3 , 0 , 0
       0      .1       0   447.5    .045       0   462.5      .1       0
Bank Sta=447.5,462.5
XS Rating Curve= 0 ,0
Exp/Cntr=0.3,0.1

Type RM Length L Ch R = 1 ,8468.8  ,673.3,680.5,687.6
XS GIS Cut Line= 2
     2116425.498      442276.444     2117104.818      442881.939
#Sta/Elev= 30
       0 2469.29      30 2460.77      50 2454.69     120 2432.37     160  2420.9
     200    2410     220 2405.61     240 2402.32     300    2395     320    2392
     330  2389.5     340 2385.55     380 2365.96     390 2361.51     400 2358.32
     410 2357.04     430 2356.93   436.6 2356.93   451.6 2356.93     480 2357.14
     590 2364.21     650 2366.08     670    2367     750 2374.37     760 2376.21
     770 2379.75     860 2417.78     880 2426.63     900 2436.15     910 2440.57
#Mann= 3 , 0 , 0
       0      .1       0   436.6    .045       0   451.6      .1       0
Bank Sta=436.6,451.6
XS Rating Curve= 0 ,0
Exp/Cntr=0.3,0.1

Type RM Length L Ch R = 1 ,7788.3  ,530.6,530.6,530.5
XS GIS Cut Line= 2
     2116053.214      442669.101     2116510.532      443455.842
#Sta/Elev= 30
       0 2437.51     100  2409.2     120 2404.16     150 2397.56     170 2393.71
     190 2390.54     200 2389.56     230 2387.92     240 2387.15     270 2383.63
     290 2379.84     330 2371.18     390 2357.62     410 2353.39     420  2352.1
   427.5  2351.8   442.5 2351.62     470 2351.45     480 2351.67     510 2354.03
     530 2356.82     570 2363.77     590 2367.63     650  2380.2     680 2386.05
     730 2395.42     810 2409.45     830 2413.17     870 2421.57     910 2431.13
#Mann= 3 , 0 , 0
       0      .1       0   427.5    .045       0   442.5      .1       0
Bank Sta=427.5,442.5
XS Rating Curve= 0 ,0
Exp/Cntr=0.3,0.1

Type RM Length L Ch R = 1 ,7257.7  ,465.2,465.2,465.1
XS GIS Cut Line= 3
     2115582.323      442912.651     2115810.982      443306.021
     2116039.641      443699.392
#Sta/Elev= 30
       0 2436.55    39.6  2423.8    79.1 2410.61    98.9 2404.21   118.7 2398.64
   138.5 2394.11   207.7 2379.72   316.5 2359.01   385.8 2344.71   395.6 2343.61
   405.5 2343.21   415.4 2343.13   445.1 2343.37   461.3 2344.08   476.3 2344.87
     544 2347.54   553.9  2348.5   563.8 2350.13   583.6 2354.22   603.4 2357.93
     633 2362.58   662.7 2366.58   692.4 2369.75   712.2 2371.52   791.3 2376.91
   830.9 2380.39   850.6 2382.69   870.4 2385.38   890.2 2388.49     910 2392.17
#Mann= 3 , 0 , 0
       0      .1       0   461.3    .045       0   476.3      .1       0
Bank Sta=461.3,476.3
XS Rating Curve= 0 ,0
Exp/Cntr=0.3,0.1

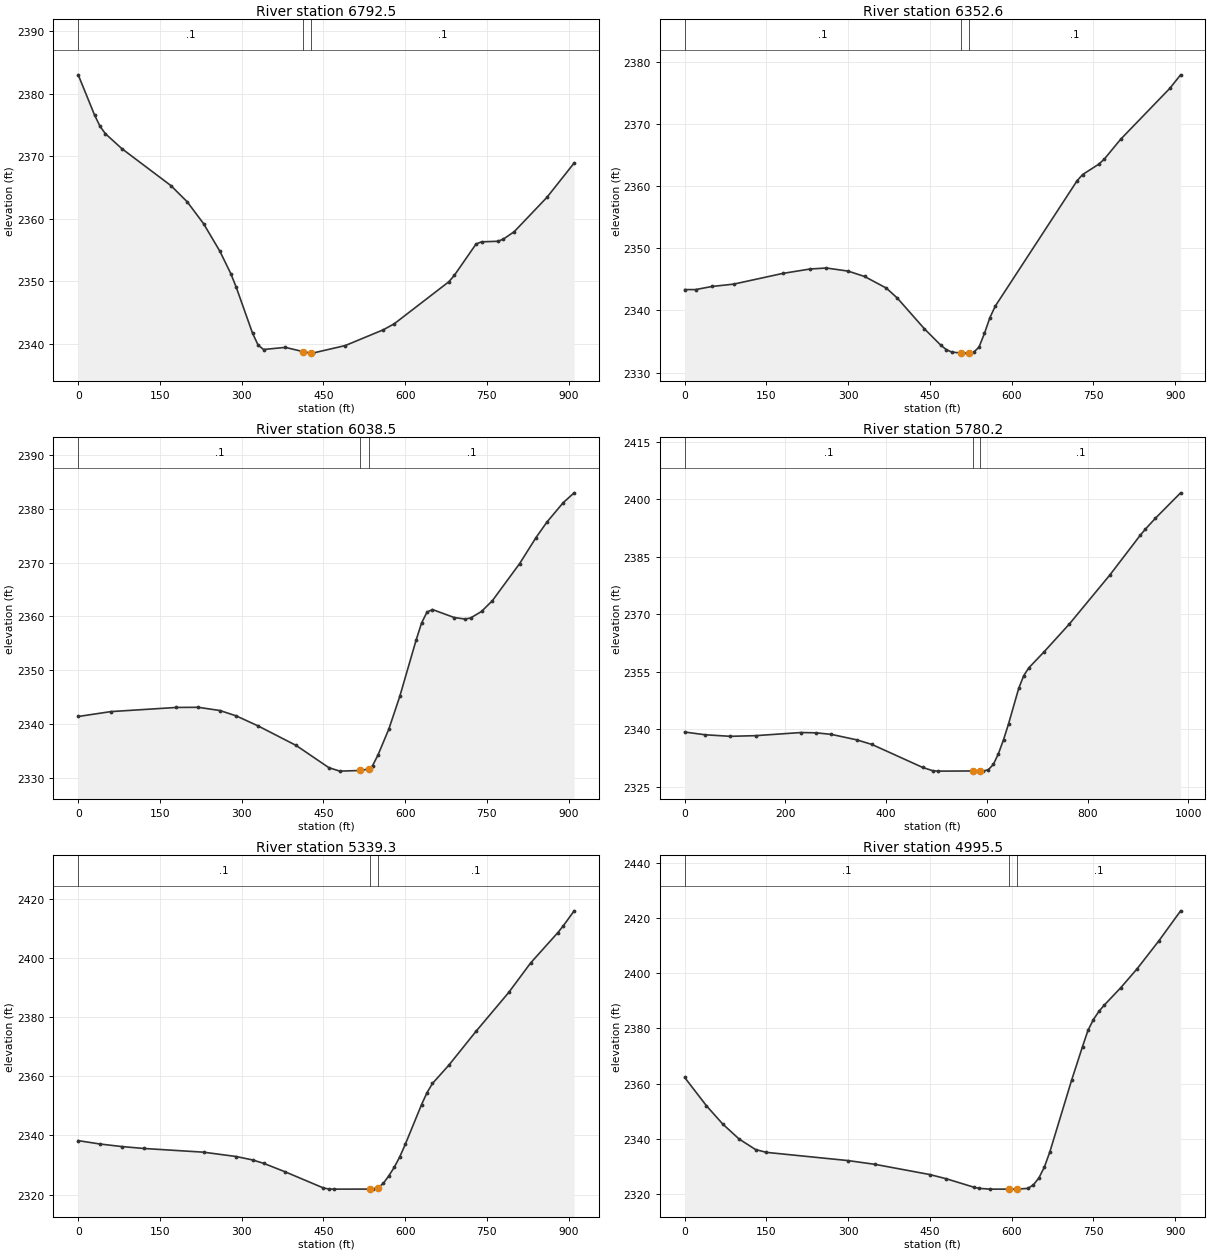
Type RM Length L Ch R = 1 ,6792.5  ,440.1,439.9,439.8
XS GIS Cut Line= 2
     2115180.941      443140.755     2115638.258      443927.496
#Sta/Elev= 30
       0 2383.05      30 2376.62      40 2374.82      50 2373.62      80 2371.25
     170 2365.34     200 2362.74     230 2359.25     260 2354.83     280 2351.25
     290 2349.07     320  2341.7     330 2339.85     340 2339.12     380 2339.46
   411.8  2338.8   426.8 2338.56     430 2338.54     490 2339.75     560 2342.28
     580 2343.24     680 2349.95     690 2350.96     730 2355.99     740 2356.34
     770 2356.43     780 2356.77     800 2357.96     860 2363.45     910 2368.95
#Mann= 3 , 0 , 0
       0      .1       0   411.8    .045       0   426.8      .1       0
Bank Sta=411.8,426.8
XS Rating Curve= 0 ,0
Exp/Cntr=0.3,0.1

Type RM Length L Ch R = 1 ,6352.6  ,303.6,314.1,324.7
XS GIS Cut Line= 2
     2114855.488      443373.311     2115312.805      444160.052
#Sta/Elev= 30
       0 2343.35      20 2343.35      50 2343.85      90 2344.23     180 2345.95
     230 2346.66     260 2346.82     300 2346.32     330 2345.46     370 2343.59
     390    2342     440 2337.03     470  2334.4     480  2333.7     490  2333.3
   507.4 2333.14     510 2333.13   522.4 2333.16     530 2333.25     540 2334.09
     550 2336.29     560 2338.83     570  2340.7     720 2360.85     730 2361.84
     760 2363.53     770 2364.34     800 2367.53     890  2375.7     910 2377.89
#Mann= 3 , 0 , 0
       0      .1       0   507.4    .045       0   522.4      .1       0
Bank Sta=507.4,522.4
XS Rating Curve= 0 ,0
Exp/Cntr=0.3,0.1

Type RM Length L Ch R = 1 ,6038.5  ,250.6,258.3,265.9
XS GIS Cut Line= 2
     2114809.429      443443.811     2114864.585      444352.138
#Sta/Elev= 30
       0 2341.37      60 2342.28     180 2343.05     220 2343.08     260 2342.48
     290 2341.48     330 2339.62     400 2335.98     460 2331.85     480 2331.21
   517.8 2331.33   532.8  2331.6     540  2332.2     550  2334.2     570 2339.04
     590  2345.1     620 2355.56     630 2358.75     640 2360.78     650 2361.26
     690 2359.77     710 2359.49     720 2359.69     740  2360.9     760 2362.91
     810 2369.81     840 2374.64     860 2377.52     890 2381.14     910 2382.96
#Mann= 3 , 0 , 0
       0      .1       0   517.8    .045       0   532.8      .1       0
Bank Sta=517.8,532.8
XS Rating Curve= 0 ,0
Exp/Cntr=0.3,0.1

Type RM Length L Ch R = 1 ,5780.2  ,427.6,441,454.4
XS GIS Cut Line= 2
     2114760.379      443380.639     2114484.745      444325.892
#Sta/Elev= 30
       0 2339.34    40.2 2338.63    90.4 2338.22   140.7 2338.39   231.1 2339.21
   261.2 2339.13   291.4 2338.72   341.6  2337.3   371.7  2336.1   472.2 2330.12
   492.3 2329.25   502.4 2329.14   572.2 2329.18   587.2 2329.16   592.8 2329.16
   602.8  2329.5   612.9 2330.91   622.9  2333.7     633 2337.32     643 2341.48
   663.1  2350.7   673.2 2354.06   683.2 2356.08   713.4 2360.24   763.6  2367.5
     844 2380.28   904.2 2390.62   914.3 2392.21   934.4 2395.08   984.6 2401.73
#Mann= 3 , 0 , 0
       0      .1       0   572.2    .045       0   587.2      .1       0
Bank Sta=572.2,587.2
XS Rating Curve= 0 ,0
Exp/Cntr=0.3,0.1

Type RM Length L Ch R = 1 ,5339.3  ,343.8,343.7,343.7
XS GIS Cut Line= 2
     2114651.317      443333.603     2113956.904      443921.728
#Sta/Elev= 30
       0 2338.24      40 2337.09      80 2336.23     120 2335.59     230 2334.33
     290 2332.86     320  2331.7     340 2330.58     380 2327.67     450 2322.23
     460 2321.88     470 2321.84   535.5 2321.85     540 2321.86   550.5 2322.34
     560 2323.82     570 2326.35     580 2329.26     590 2332.75     600 2336.93
     630 2350.42     640 2354.45     650 2357.56     680 2363.73     730  2375.2
     790 2388.34     830 2398.27     880 2408.54     890 2410.84     910 2415.92
#Mann= 3 , 0 , 0
       0      .1       0   535.5    .045       0   550.5      .1       0
Bank Sta=535.5,550.5
XS Rating Curve= 0 ,0
Exp/Cntr=0.3,0.1

Type RM Length L Ch R = 1 ,4995.5  ,569.1,569.2,569.3
XS GIS Cut Line= 2
     2114460.467      443050.158     2113766.055      443638.283
#Sta/Elev= 30
       0 2362.21      40 2351.91      70 2345.25     100 2339.82     130 2336.02
     150 2334.99     300    2332     350 2330.61     450 2326.92     480  2325.4
     530 2322.37     540 2321.91     560 2321.63   594.7 2321.63   609.7 2321.63
     630 2321.91     640 2323.22     650 2325.71     660 2329.65     670 2335.14
     710 2361.22     730 2373.44     740 2379.31     750 2383.27     760 2386.21
     770 2388.52     800 2394.79     830 2401.66     870 2411.83     910 2422.76
#Mann= 3 , 0 , 0
       0      .1       0   594.7    .045       0   609.7      .1       0
Bank Sta=594.7,609.7
XS Rating Curve= 0 ,0
Exp/Cntr=0.3,0.1

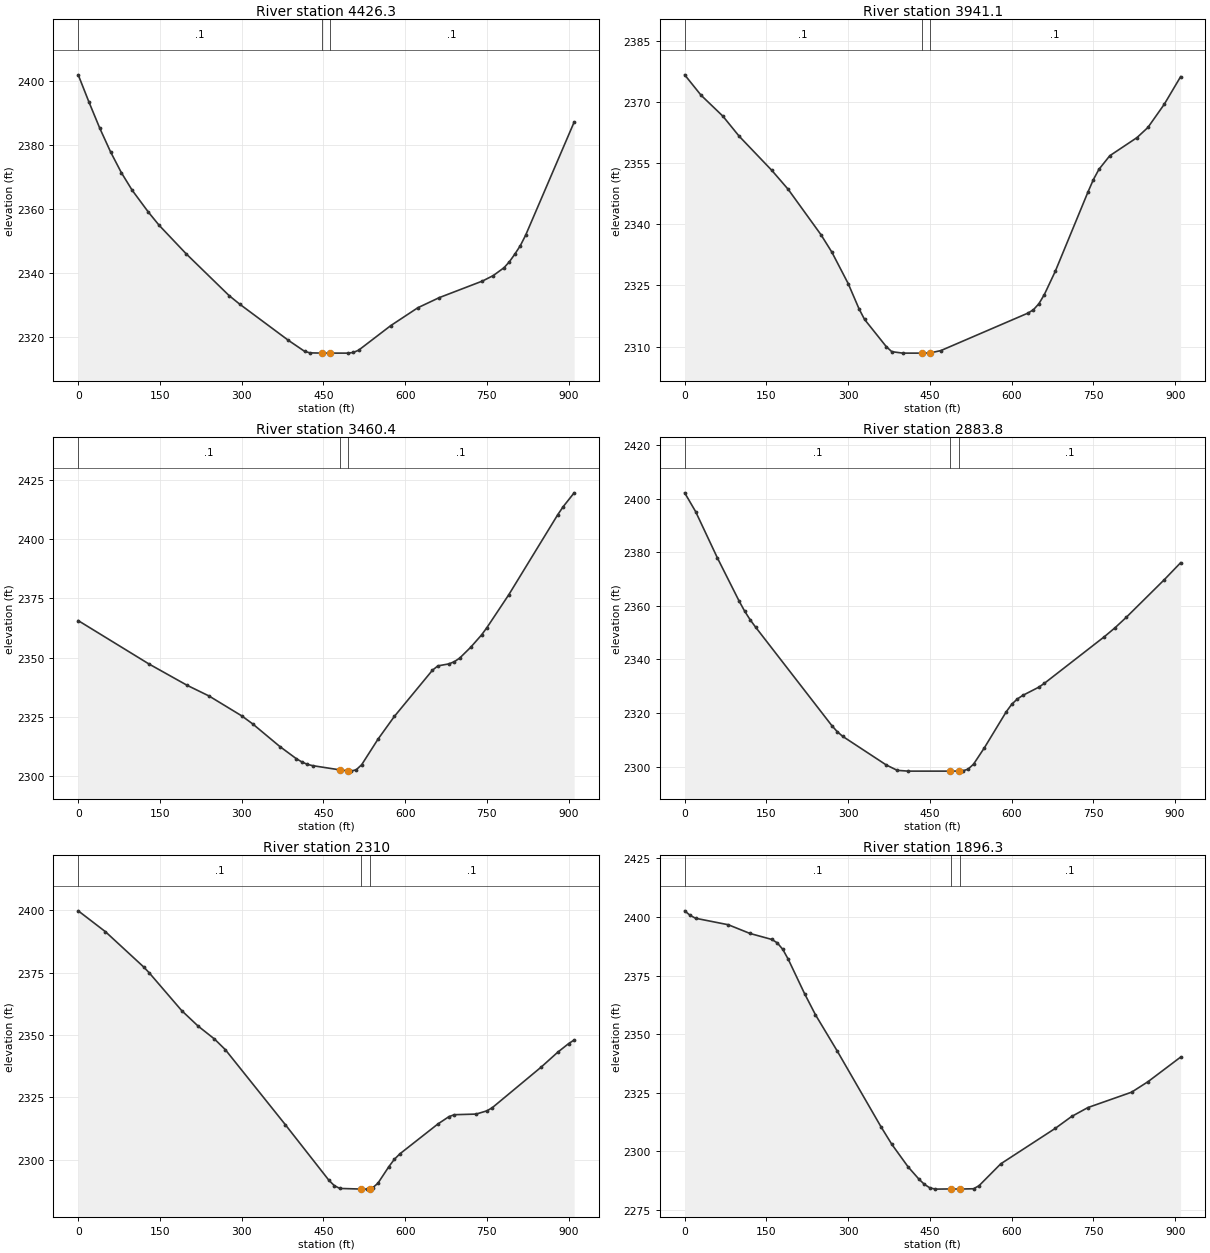
Type RM Length L Ch R = 1 ,4426.3  ,497.6,485.2,472.8
XS GIS Cut Line= 3
     2114112.803      442640.825     2113765.597      442934.888
     2113418.391       443228.95
#Sta/Elev= 30
       0 2401.95    19.8 2393.41    39.6 2385.26    59.4 2377.87    79.1 2371.41
    98.9 2365.93   128.6  2359.1   148.4 2354.97   197.8  2346.1     277 2332.97
   296.7 2330.27   385.8    2319   415.4 2315.58   425.3  2315.1   447.5 2315.03
   462.5 2315.03   494.6 2315.02   504.5 2315.22   514.4 2315.92   573.7 2323.64
   623.2  2329.2   662.7 2332.37   741.8 2337.54   761.6 2339.25   781.4 2341.71
   791.3 2343.59   801.2 2345.96   811.1 2348.55     821 2351.87     910 2387.19
#Mann= 3 , 0 , 0
       0      .1       0   447.5    .045       0   462.5      .1       0
Bank Sta=447.5,462.5
XS Rating Curve= 0 ,0
Exp/Cntr=0.3,0.1

Type RM Length L Ch R = 1 ,3941.1  ,482.3,480.7,479
XS GIS Cut Line= 2
     2113555.481      442191.213     2113267.637      443054.489
#Sta/Elev= 30
       0  2376.6      30 2371.61      70 2366.49     100 2361.56     160 2353.18
     190 2348.54     250 2337.45     270 2333.18     300 2325.47     320 2319.26
     330  2316.7     370 2310.01     380 2308.79     400 2308.43   434.9 2308.43
   449.9 2308.47     470 2309.05     630 2318.24     640 2319.07     650 2320.54
     660 2322.79     680 2328.47     740  2347.9     750 2350.95     760 2353.43
     780 2356.78     830 2361.23     850 2363.71     880 2369.39     910 2376.15
#Mann= 3 , 0 , 0
       0      .1       0   434.9    .045       0   449.9      .1       0
Bank Sta=434.9,449.9
XS Rating Curve= 0 ,0
Exp/Cntr=0.3,0.1

Type RM Length L Ch R = 1 ,3460.4  ,571.4,576.7,581.9
XS GIS Cut Line= 2
     2113067.953      442143.716     2112832.553      443023.098
#Sta/Elev= 30
       0 2365.56     130 2347.26   200.1 2338.27   240.1 2333.79   300.1 2325.42
   320.1 2322.05   370.1 2312.49   400.2 2307.39   410.2 2306.03   420.2 2305.01
   430.2 2304.43     480 2302.66     495 2302.22   500.2 2302.12   510.2 2302.68
   520.2 2304.79   550.2 2315.57   580.2 2325.15   650.2 2344.65   660.2 2346.48
   680.3 2347.31   690.3 2348.23   700.3 2349.78   720.3  2354.3   740.3 2359.51
   750.3 2362.65   790.3 2376.46   880.3 2410.23   890.3 2413.62   910.3 2419.41
#Mann= 3 , 0 , 0
       0      .1       0     480    .045       0     495      .1       0
Bank Sta=480,495
XS Rating Curve= 0 ,0
Exp/Cntr=0.3,0.1

Type RM Length L Ch R = 1 ,2883.8  ,586.8,573.7,560.7
XS GIS Cut Line= 2
     2112661.519      441923.311     2112233.085      442726.536
#Sta/Elev= 30
       0 2402.21      20 2395.24      60 2377.94     100 2361.78     110 2358.08
     120 2354.88     130 2352.12   270.1 2315.32   280.1 2313.04   290.1  2311.3
   370.1 2300.62   390.2 2298.62   410.2 2298.33   487.7 2298.33   502.7 2298.35
   510.2  2298.4   520.2 2299.08   530.2 2300.92   550.2 2307.07   590.2 2320.47
   600.2 2323.25   610.2  2325.2   620.2 2326.56   650.2 2329.69   660.2  2331.1
   770.3  2348.5   790.3 2351.91   810.3 2355.69   880.3 2369.78   910.3 2376.12
#Mann= 3 , 0 , 0
       0      .1       0   487.7    .045       0   502.7      .1       0
Bank Sta=487.7,502.7
XS Rating Curve= 0 ,0
Exp/Cntr=0.3,0.1

Type RM Length L Ch R = 1 ,2310    ,417,413.8,410.5
XS GIS Cut Line= 2
     2111828.399      441713.318     2111905.842      442620.362
#Sta/Elev= 30
       0 2399.84      50 2391.46     120 2377.35     130 2375.05   190.1 2359.77
   220.1 2353.59   250.1 2348.41   270.1 2344.12   380.1 2314.06   460.2 2291.72
   470.2 2289.56   480.2 2288.46   519.8  2288.2   530.2 2288.18   534.8  2288.4
   540.2 2288.66   550.2 2290.57   570.2  2297.2   580.2 2300.12   590.2  2302.3
   660.2 2314.32   680.3 2317.24   690.3 2318.04   730.3 2318.29   750.3  2319.6
   760.3  2320.9   850.3 2337.24   880.3 2343.14   900.3 2346.59   910.3 2348.02
#Mann= 3 , 0 , 0
       0      .1       0   519.8    .045       0   534.8      .1       0
Bank Sta=519.8,534.8
XS Rating Curve= 0 ,0
Exp/Cntr=0.3,0.1

Type RM Length L Ch R = 1 ,1896.3  ,507.5,498.9,490.3
XS GIS Cut Line= 2
      2111347.46      441771.602     2111555.479      442657.507
#Sta/Elev= 30
       0 2402.64      10  2400.7      20 2399.47      80  2396.7     120 2392.97
     160 2390.42     170 2388.95     180  2386.2     190 2381.99     220  2367.3
     240 2358.28     280 2342.79     360 2310.58     380 2303.04     410 2293.38
     430 2288.11     440 2285.91     450 2284.42     460 2283.89   489.3 2283.98
   504.3 2283.92     530 2284.05     540 2285.32     580 2294.69     680 2309.82
     710 2314.89     740 2318.71     820 2325.25     850 2329.71     910 2340.23
#Mann= 3 , 0 , 0
       0      .1       0   489.3    .045       0   504.3      .1       0
Bank Sta=489.3,504.3
XS Rating Curve= 0 ,0
Exp/Cntr=0.3,0.1