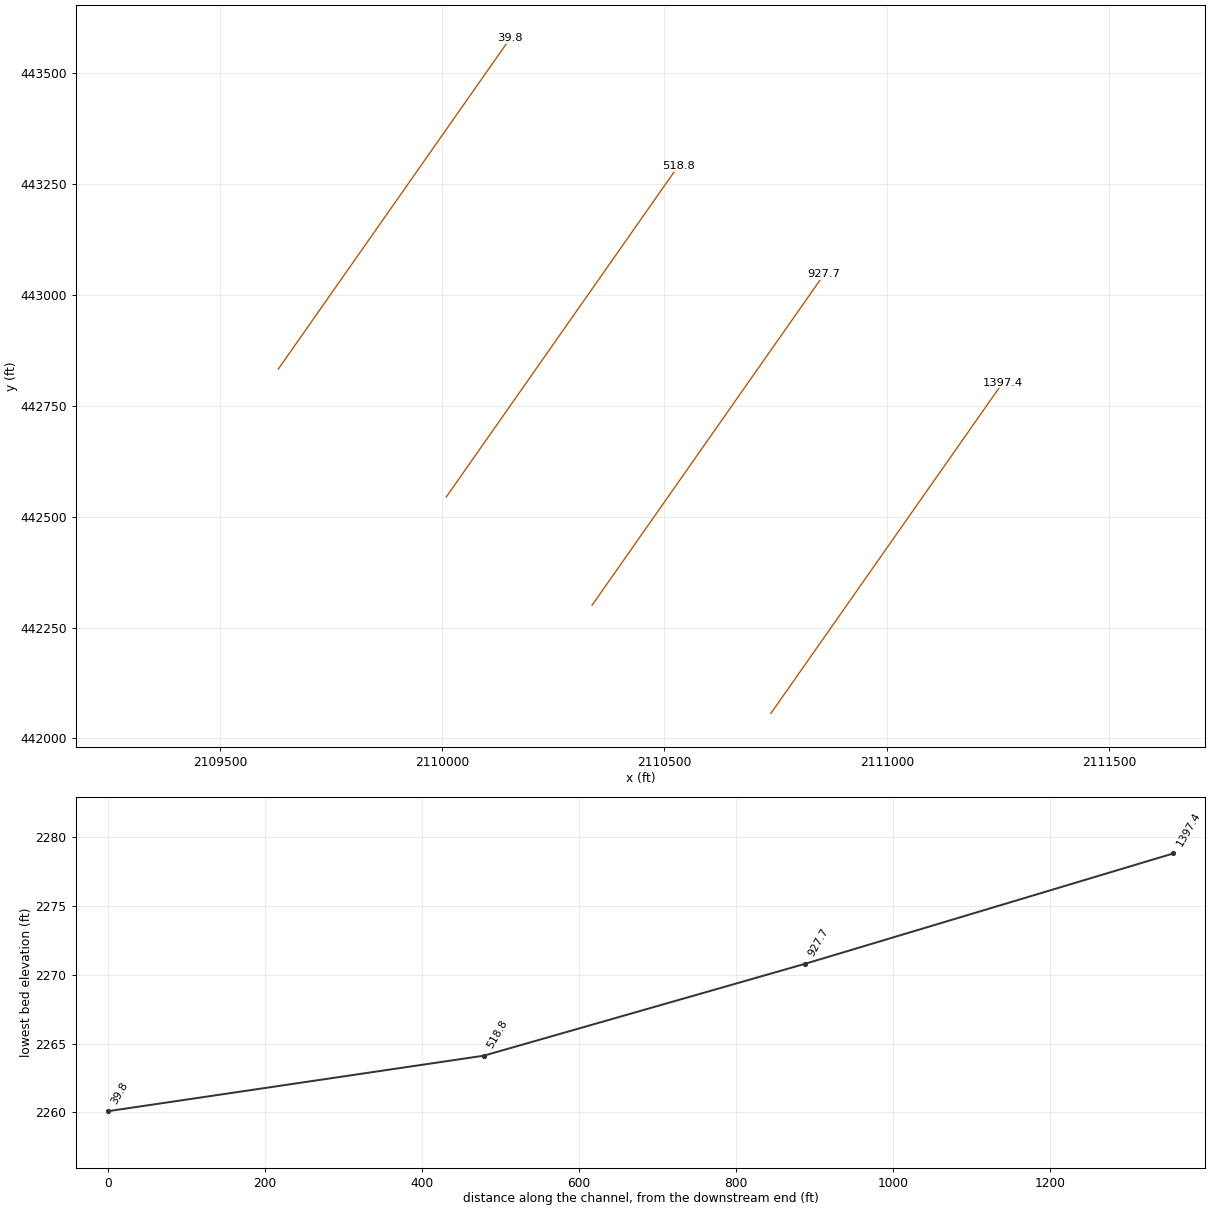
HEC-RAS study SFrkChryRv.prj: SFrkChryRv

--- SFrkChryRv.g01 (geometry) --- (continued)

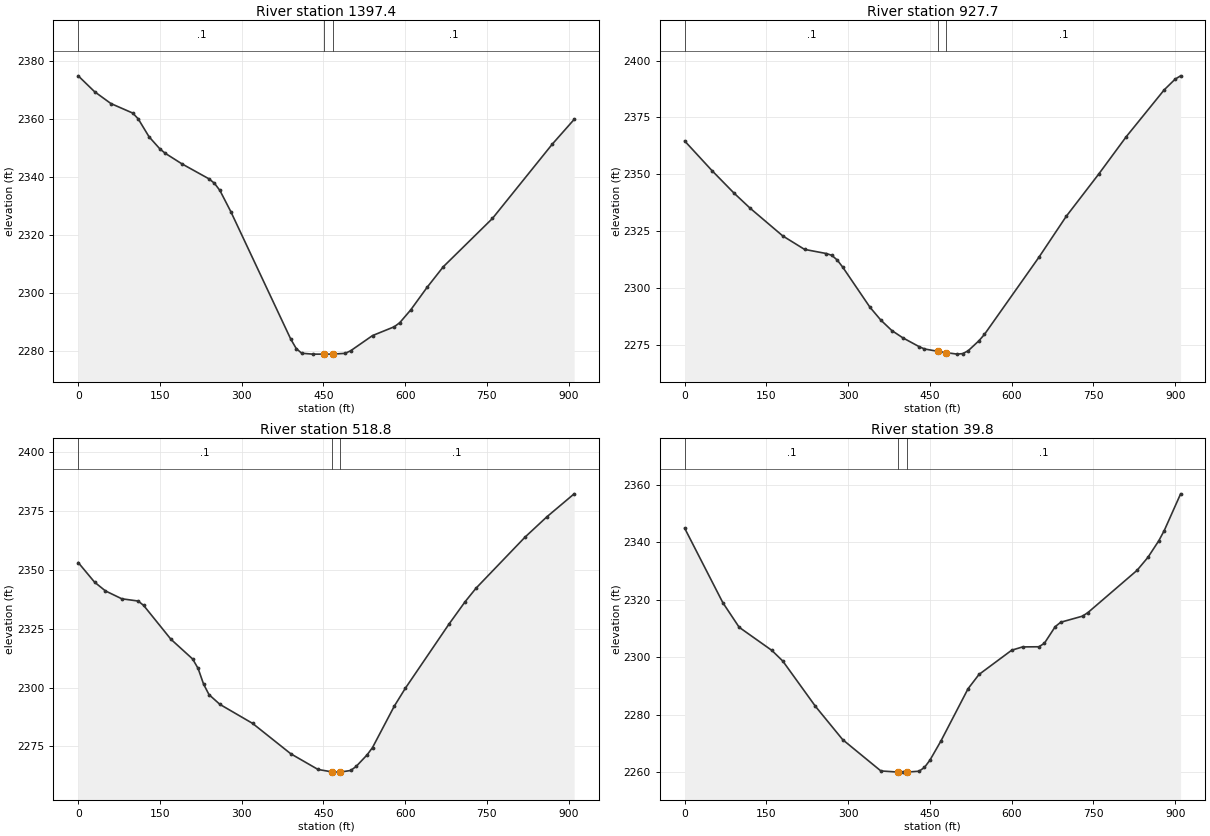
Type RM Length L Ch R = 1 ,1397.4  ,469.7,469.7,469.7
XS GIS Cut Line= 2
      2110739.35      442056.491     2111261.016      442802.121
#Sta/Elev= 30
       0 2374.85      30 2369.38      60 2365.28     100    2362     110 2360.02
     130 2353.81     150  2349.6     160 2348.08     190  2344.5     240 2339.29
     250 2337.76     260 2335.28     280 2327.98     390 2283.98     400 2280.74
     410 2279.11     430  2278.8   451.8  2278.8   466.8  2278.8     490 2279.08
     500 2279.97     540  2285.2     580 2288.25     590 2289.65     610 2294.03
     640 2301.81     670 2308.98     760 2325.61     870  2351.3     910 2359.81
#Mann= 3 , 0 , 0
       0      .1       0   451.8    .045       0   466.8      .1       0
Bank Sta=451.8,466.8
XS Rating Curve= 0 ,0
Exp/Cntr=0.3,0.1

Type RM Length L Ch R = 1 ,927.7   ,408.8,408.8,408.8
XS GIS Cut Line= 2
     2110337.043      442300.096     2110858.709      443045.726
#Sta/Elev= 30
       0 2364.61      50 2351.59      90 2341.79     120 2335.04     180 2322.81
     220 2316.88     260 2315.06     270 2314.27     280 2312.18     290 2309.07
     340 2291.41     360 2285.74     380 2281.18     400    2278     430  2274.1
     440 2273.05   465.2 2271.99   480.2 2271.43     500 2270.78     510    2271
     520 2272.22     540 2276.68     550 2279.45     650 2313.43     700  2331.4
     760 2350.13     810 2366.42     880 2387.15     900 2391.84     910 2393.29
#Mann= 3 , 0 , 0
       0      .1       0   465.2    .045       0   480.2      .1       0
Bank Sta=465.2,480.2
XS Rating Curve= 0 ,0
Exp/Cntr=0.3,0.1

Type RM Length L Ch R = 1 ,518.8   ,479.1,479,479
XS GIS Cut Line= 2
     2110009.027      442544.055     2110530.693      443289.685
#Sta/Elev= 30
       0 2353.04      30 2344.71      50 2340.99      80 2337.65     110  2336.7
     120 2334.85     170 2320.51     210  2312.1     220  2308.1     230 2301.48
     240 2296.99     260 2292.86     320 2284.79     390 2271.91     440 2265.25
   465.5 2264.23     480 2264.12   480.5 2264.13     500 2264.82     510 2266.54
     530 2271.42     540 2274.54     580 2292.13     600 2299.61     680 2326.81
     710 2336.44     730 2342.16     820 2363.84     860 2372.44     910 2382.18
#Mann= 3 , 0 , 0
       0      .1       0   465.5    .045       0   480.5      .1       0
Bank Sta=465.5,480.5
XS Rating Curve= 0 ,0
Exp/Cntr=0.3,0.1

Type RM Length L Ch R = 1 ,39.8    ,35.4,39.8,44.2
XS GIS Cut Line= 2
     2109631.235      442832.296     2110152.901      443577.927
#Sta/Elev= 30
       0 2344.82      70 2318.96     100 2310.41     160 2302.37     180 2298.68
     240 2282.93     290 2271.36     360  2260.5   392.2  2260.1     400 2260.09
   407.2  2260.1     430  2260.4     440 2261.73     450 2264.25     470 2270.84
     520 2289.07     540 2294.01     600 2302.44     620 2303.59     650 2303.64
     660 2304.85     680 2310.65     690 2312.16     730 2314.28     740 2315.53
     830 2330.18     850  2334.7     870 2340.48     880 2344.03     910 2356.77
#Mann= 3 , 0 , 0
       0      .1       0   392.2    .045       0   407.2      .1       0
Bank Sta=392.2,407.2
XS Rating Curve= 0 ,0
Exp/Cntr=0.3,0.1

Chan Stop Cuts=-1
Use User Specified Reach Order=0